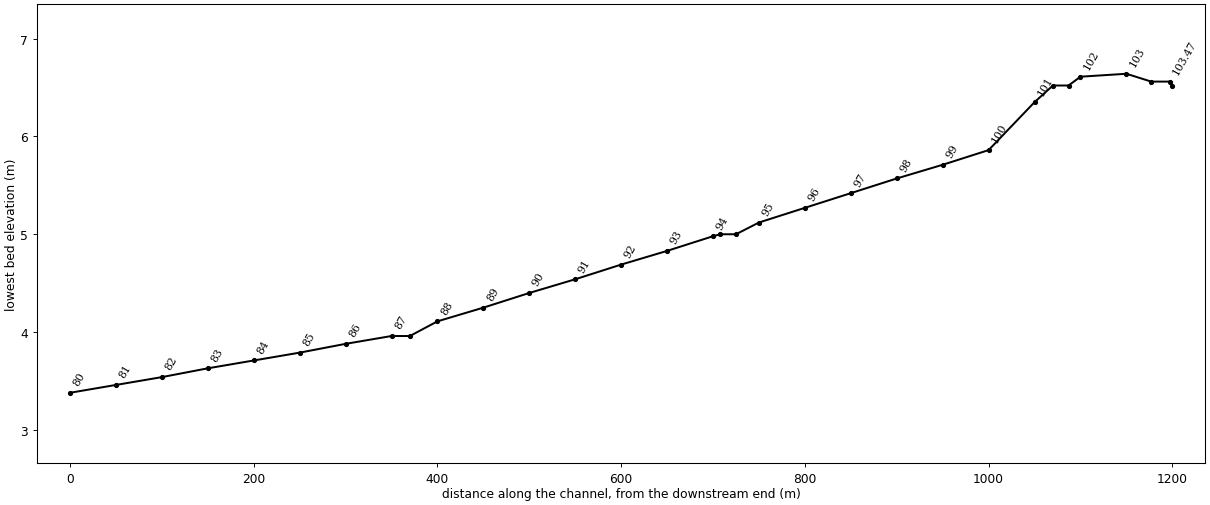
--- hj.prj (project) ---

Proj Title=Hwajung_plan
Current Plan=p03
Default Exp/Contr=0.3,0.1
SI Units
Geom File=g01
Flow File=f06
Flow File=f01
Flow File=f02
Flow File=f03
Flow File=f04
Flow File=f05
Plan File=p03
Plan File=p02
Plan File=p01
Y Axis Title=Elevation
X Axis Title(PF)=Main Channel Distance
X Axis Title(XS)=Station
BEGIN DESCRIPTION:
°³¼öÈÄ
END DESCRIPTION:
DSS Export Rating Curves= 0
DSS Export Rating Curve Sorted= 0
DSS Export Volume Flow Curves= 0
DXF OffsetX= 0
DXF OffsetY= 0
DXF ScaleX= 1
DXF ScaleY= 10

--- hj.p03 (plan) ---

Plan Title=Plan 03
Program Version=3.13
Short Identifier=Plan 03
Geom File=g01
Flow File=f06
Subcritical Flow
K Sum by GR= 0
Std Step Tol= 0.01
Critical Tol= 0.01
Num of Std Step Trials= 20
Max Error Tol= 0.3
Flow Tol Ratio= 0.001
Split Flow NTrial= 30
Split Flow Tol= 0.02
Split Flow Ratio= 0.02
Log Output Level= 0
Friction Slope Method= 1
Unsteady Friction Slope Method= 2
Unsteady Bridges Friction Slope Method= 1
Parabolic Critical Depth
Global Vel Dist= 0 , 0 , 0
Global Log Level= 0
CheckData=True
Encroach Param=-1 ,0,0, 0
Computation Interval=1HOUR
Output Interval=1HOUR
Run HTab= 0
Run UNet= 0
Run PostProcess= 0
UNET Theta= 1
UNET Theta Warmup= 1
UNET ZTol= 0.02
UNET ZSATol= 0.05
UNET MxIter= 20
UNET MaxInSteps= 0
UNET DtIC= 0
UNET DtMin= 0
UNET MaxCRTS= 20
UNET WFStab= 2
UNET SFStab= 1
UNET WFX= 1
UNET SFX= 1
UNET DSS MLevel= 4
UNET DZMax Abort= 100
UNET Convert EG Bridges=-1
UNET Use Existing IB Tables=-1
UNET Froude Reduction=False
UNET Froude Limit= 1
UNET Froude Power= 10
Instantaneous Interval=1HOUR
DSS File=dss
Write IC File= 0
Echo Input=False
Echo Output=False
Write Detailed= 0
Detailed Automatic Start=False, 10

--- hj.p01 (plan) ---

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Plan Title=Plan 01
Short Identifier=1
Geom File=g01
Flow File=f01
Supercritical Flow

--- hj.p02 (plan) ---

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Plan Title=Plan 02
Geom File=g01

--- hj.f06 (steady flow) ---

Flow Title=plan
Program Version=3.12
Number of Profiles= 14
Profile Names=96',1.58yr,10yr,20yr,30yr,50yr,80yr,100yr,200yr,plan,PF 11,PF 12,2001yr,2006yr
River Rch & RM=RIVER-1,Reach-1         ,104
     215      35      75      90     100     110     120     125     140     125
     .23     .27      49       2
River Rch & RM=RIVER-1,Reach-1         ,87
     215      50     110     135     145     160     175     180     200     180
     .23     .27     119       3
River Rch & RM=RIVER-1,Reach-1         ,69.22
     295      65     140     165     180     200     215     225     250     225
     .23     .27     178       5
River Rch & RM=RIVER-1,Reach-1         ,30.38
     385      75     160     190     205     225     245     255     285     255
     .23     .27     207       6
Boundary for River Rch & Prof#=RIVER-1,Reach-1         , 1
Up Type= 0
Dn Type= 1
Dn Known WS=2.31
Boundary for River Rch & Prof#=RIVER-1,Reach-1         , 2
Up Type= 0
Dn Type= 1
Dn Known WS=0.24
Boundary for River Rch & Prof#=RIVER-1,Reach-1         , 3
Up Type= 0
Dn Type= 1
Dn Known WS=1.24
Boundary for River Rch & Prof#=RIVER-1,Reach-1         , 4
Up Type= 0
Dn Type= 1
Dn Known WS=1.51
Boundary for River Rch & Prof#=RIVER-1,Reach-1         , 5
Up Type= 0
Dn Type= 1
Dn Known WS=1.68
Boundary for River Rch & Prof#=RIVER-1,Reach-1         , 6
Up Type= 0
Dn Type= 1
Dn Known WS=1.86
Boundary for River Rch & Prof#=RIVER-1,Reach-1         , 7
Up Type= 0
Dn Type= 1
Dn Known WS=2.02
Boundary for River Rch & Prof#=RIVER-1,Reach-1         , 8
Up Type= 0
Dn Type= 1
Dn Known WS=2.05
Boundary for River Rch & Prof#=RIVER-1,Reach-1         , 9
Up Type= 0
Dn Type= 1
Dn Known WS=2.32
Boundary for River Rch & Prof#=RIVER-1,Reach-1         , 10
Up Type= 0
Dn Type= 1
Dn Known WS=2.05
Boundary for River Rch & Prof#=RIVER-1,Reach-1         , 11
Up Type= 0
Dn Type= 1
Dn Known WS=-1
Boundary for River Rch & Prof#=RIVER-1,Reach-1         , 12
Up Type= 0
Dn Type= 1
Dn Known WS=-1
Boundary for River Rch & Prof#=RIVER-1,Reach-1         , 13
Up Type= 0
Dn Type= 1
Dn Known WS=1.68
Boundary for River Rch & Prof#=RIVER-1,Reach-1         , 14
Up Type= 0
Dn Type= 1
Dn Known WS=-0.98
DSS Import GetInterval= 0
DSS Import GetPeak= 0
DSS Import FillOption= 0

--- hj.f01 (steady flow) ---

Flow Title=Flow 01
Program Version=3.13
Number of Profiles= 1
Profile Names=plan
River Rch & RM=RIVER-1,Reach-1         ,104
     215
River Rch & RM=RIVER-1,Reach-1         ,69.22
     295
River Rch & RM=RIVER-1,Reach-1         ,27.08
     385
Boundary for River Rch & Prof#=RIVER-1,Reach-1         , 1
Up Type= 0
Dn Type= 1
Dn Known WS=2.44
DSS Import GetInterval= 0
DSS Import GetPeak= 0
DSS Import FillOption= 0

--- hj.f02 (steady flow) ---

Flow Title=Flow 02
Program Version=3.11
Number of Profiles= 1
Profile Names=PF 1
River Rch & RM=RIVER-1,Reach-1         ,104
DSS Import GetInterval= 0
DSS Import GetPeak= 0
DSS Import FillOption= 0

--- hj.f03 (steady flow) ---

Flow Title=Flow 03
Program Version=3.13
Number of Profiles= 1
Profile Names=PF 1
DSS Import GetInterval= 0
DSS Import GetPeak= 0
DSS Import FillOption= 0

--- hj.f04 (steady flow) ---

Flow Title=Flow 04
Program Version=3.13
Number of Profiles= 1
Profile Names=96'
River Rch & RM=RIVER-1,Reach-1         ,104
     215
River Rch & RM=RIVER-1,Reach-1         ,69.21
     295
River Rch & RM=RIVER-1,Reach-1         ,30.379
     385
Boundary for River Rch & Prof#=RIVER-1,Reach-1         , 1
Up Type= 3
Up Slope=0.001999
Dn Type= 1
Dn Known WS=2.31
DSS Import GetInterval= 0
DSS Import GetPeak= 0
DSS Import FillOption= 0

--- hj.f05 (steady flow) ---

Flow Title=Flow 05
Program Version=3.13
Number of Profiles= 1
Profile Names=PF 1
River Rch & RM=RIVER-1,Reach-1         ,104
     215
River Rch & RM=RIVER-1,Reach-1         ,69
     295
River Rch & RM=RIVER-1,Reach-1         ,30
     385
Boundary for River Rch & Prof#=RIVER-1,Reach-1         , 1
Up Type= 0
Dn Type= 1
Dn Known WS=2.31
DSS Import GetInterval= 0
DSS Import GetPeak= 0
DSS Import FillOption= 0

--- hj.g01 (geometry) ---

Geom Title=Geom 01
Program Version=3.12

River Reach=RIVER-1         ,Reach-1
Reach XY= 2
              .5             .95              .5             .05

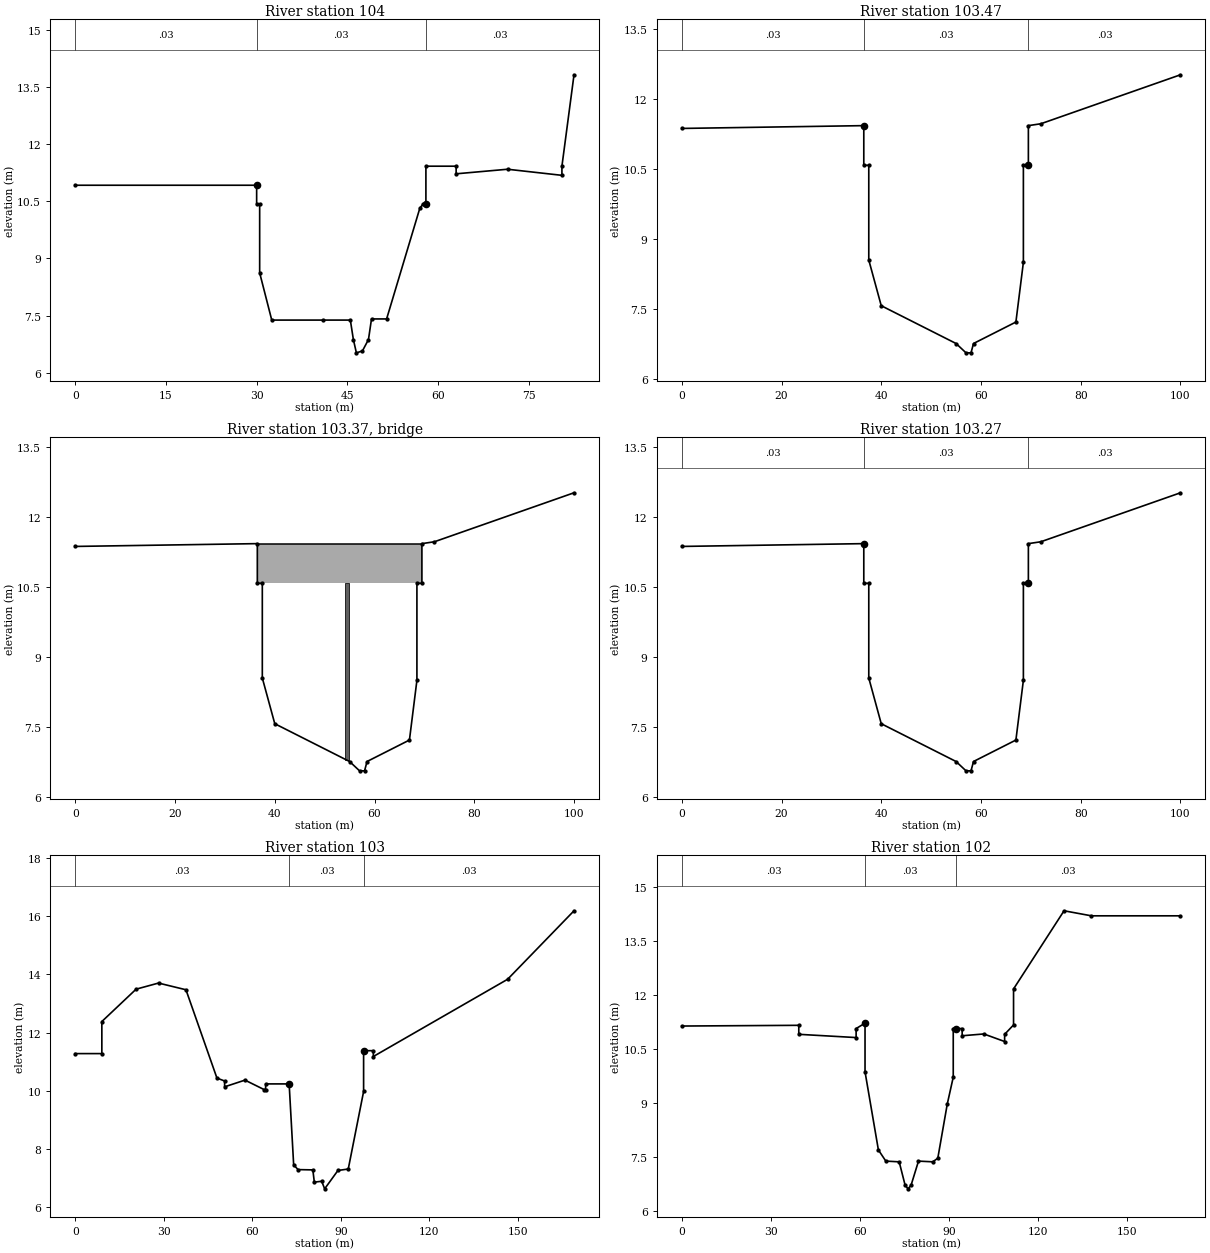
Type RM Length L Ch R = 1 ,104     ,3,3,3
#Sta/Elev= 24
       0   10.92      30   10.92      30   10.42    30.5   10.42    30.5    8.62
    32.5    7.38      41    7.38    45.5    7.38      46    6.87    46.5    6.52
    47.5    6.57    48.5    6.87      49    7.41    51.5    7.41      57   10.32
    57.5   10.42      58   10.42      58   11.42      63   11.42      63   11.22
    71.5   11.34    80.5   11.18    80.5   11.42    82.5   13.82
#Mann= 3 , 0 , 0
       0     .03       0      30     .03       0      58     .03       0
Bank Sta=30,58
Exp/Cntr=0.3,0.1

Type RM Length L Ch R = 1 ,103.47  ,20,20,20
#Sta/Elev= 17
       0   11.37    36.5   11.43    36.5   10.58    37.5   10.58    37.5    8.55
      40    7.57      55    6.76      57    6.56      58    6.56    58.5    6.76
      67    7.22    68.5     8.5    68.5   10.58    69.5   10.58    69.5   11.43
      72   11.47     100   12.52
#Mann= 3 , 0 , 0
       0     .03       0    36.5     .03       0    69.5     .03       0
Bank Sta=36.5,69.5
Exp/Cntr=0.5,0.3

Type RM Length L Ch R = 3 ,103.37  ,,,
BEGIN DESCRIPTION:
È­Á¤8±³
END DESCRIPTION:
Bridge Culvert--1,0,-1,-1, 0
Deck Dist Width WeirC Skew NumUp NumDn MinLoCord MaxHiCord MaxSubmerge Is_Ogee
0.1,19,1.44,0, 2, 2, , , 0.95, 0, 0,0,,
    36.5    69.5
   11.43   11.43
   10.58   10.58
    36.5    69.5
   11.43   11.43
   10.58   10.58
Pier Skew, UpSta & Num, DnSta & Num=  ,54.5, 2 ,54.5, 2 , 0 , 0 , 0 ,,
      .7      .7
       5      11
      .7      .7
       5      11
BR Coef=-1 , 0 , 0 ,, 0 ,,,0.8,-1,,0,
WSPro=,,,, 1 ,,,, 0 ,,,, 0 ,,,,-1 ,-1 ,-1 , 0 , 0 , 0 , 0 , 0
BC Design=,, 0 ,, 0 ,,,,,,

Type RM Length L Ch R = 1 ,103.27  ,27,27,27
#Sta/Elev= 17
       0   11.37    36.5   11.43    36.5   10.58    37.5   10.58    37.5    8.55
      40    7.57      55    6.76      57    6.56      58    6.56    58.5    6.76
      67    7.22    68.5     8.5    68.5   10.58    69.5   10.58    69.5   11.43
      72   11.47     100   12.52
#Mann= 3 , 0 , 0
       0     .03       0    36.5     .03       0    69.5     .03       0
Bank Sta=36.5,69.5
Exp/Cntr=0.5,0.3

Type RM Length L Ch R = 1 ,103     ,50,50,50
#Sta/Elev= 30
       0   11.28       9   11.28       9   12.38    20.6   13.49    28.2    13.7
    37.5   13.47      48   10.44    50.6   10.34    50.6   10.14    57.5   10.37
    64.1   10.04    64.5   10.04    64.5   10.24   72.33   10.24   72.47   10.24
      74    7.46    75.5     7.3    80.5    7.29      81    6.87    83.5     6.9
    84.5    6.64      89    7.27    92.5    7.32    97.7    9.98    97.7   11.38
      98   11.38     101   11.38     101   11.18   146.5   13.83     169   16.18
#Mann= 3 , 0 , 0
       0     .03       0   72.33     .03       0      98     .03       0
Bank Sta=72.33,98
Exp/Cntr=0.3,0.1

Type RM Length L Ch R = 1 ,102     ,13,13,13
#Sta/Elev= 30
       0   11.13    39.4   11.15    39.4    10.9    58.7   10.81    58.7   11.06
    61.7   11.21    61.7    9.86    66.2    7.69    68.7    7.38    73.2    7.36
    75.2    6.71    76.2    6.61    77.2    6.71    79.7    7.38    84.5    7.36
    86.2    7.46    89.4    8.97    91.4    9.71    91.4   11.06    92.2   11.06
    94.4   11.06    94.4   10.86   101.7   10.91   108.7    10.7   108.7    10.9
   111.7   11.16   111.7   12.16   128.7   14.33   137.9   14.19   167.9   14.19
#Mann= 3 , 0 , 0
       0     .03       0    61.7     .03       0    92.2     .03       0
Bank Sta=61.7,92.2
Exp/Cntr=0.3,0.1

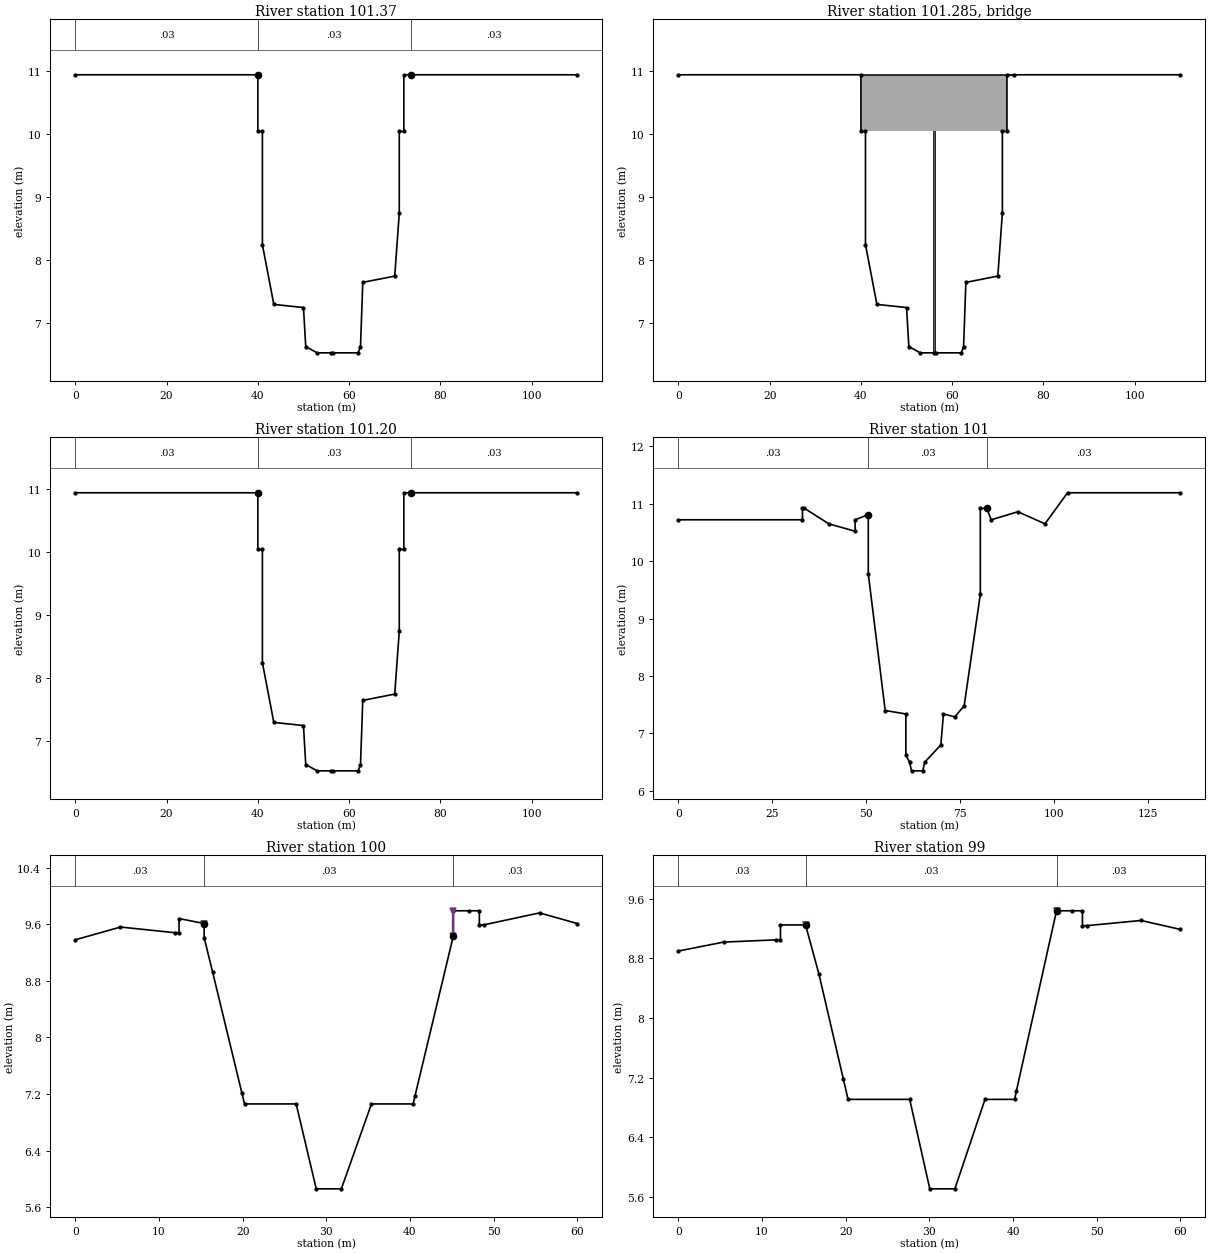
Type RM Length L Ch R = 1 ,101.37  ,17,17,17
#Sta/Elev= 21
       0   10.94      40   10.94      40   10.04      41   10.04      41    8.24
    43.5    7.29      50    7.24    50.5    6.62      53    6.52      56    6.52
    56.5    6.52      62    6.52    62.5    6.62      63    7.64      70    7.74
      71    8.74      71   10.04      72   10.04      72   10.94    73.5   10.94
     110   10.94
#Mann= 3 , 0 , 0
       0     .03       0      40     .03       0    73.5     .03       0
Bank Sta=40,73.5
Exp/Cntr=0.5,0.3

Type RM Length L Ch R = 3 ,101.285 ,,,
BEGIN DESCRIPTION:
È­Á¤7±³
END DESCRIPTION:
Bridge Culvert--1,0,-1,-1, 0
Deck Dist Width WeirC Skew NumUp NumDn MinLoCord MaxHiCord MaxSubmerge Is_Ogee
0.1,16,1.44,0, 2, 2, , , 0.95, 0, 0,0,,
      40    73.5
   10.94   10.94
   10.04   10.04
      40    73.5
   10.94   10.94
   10.04   10.04
Pier Skew, UpSta & Num, DnSta & Num=  ,56, 2 ,56, 2 , 0 , 0 , 0 ,,
      .6      .6
       5      11
      .6      .6
       5      11
BR Coef=-1 , 0 , 0 ,, 0 ,,,0.8,-1,,0,
WSPro=,,,, 1 ,,,, 0 ,,,, 0 ,,,,-1 ,-1 ,-1 , 0 , 0 , 0 , 0 , 0
BC Design=,, 0 ,, 0 ,,,,,,

Type RM Length L Ch R = 1 ,101.20  ,20,20,20
#Sta/Elev= 21
       0   10.94      40   10.94      40   10.04      41   10.04      41    8.24
    43.5    7.29      50    7.24    50.5    6.62      53    6.52      56    6.52
    56.5    6.52      62    6.52    62.5    6.62      63    7.64      70    7.74
      71    8.74      71   10.04      72   10.04      72   10.94    73.5   10.94
     110   10.94
#Mann= 3 , 0 , 0
       0     .03       0      40     .03       0    73.5     .03       0
Bank Sta=40,73.5
Exp/Cntr=0.5,0.3

Type RM Length L Ch R = 1 ,101     ,50,50,50
#Sta/Elev= 28
       0   10.72      33   10.72      33   10.92    33.5   10.92      40   10.65
      47   10.52      47   10.72    50.5   10.81    50.5    9.78      55     7.4
    60.5    7.34    60.5    6.62    61.5     6.5      62    6.35      65    6.35
    65.5     6.5    69.8     6.8    70.5    7.34    73.5    7.29      76    7.48
    80.3    9.42    80.3   10.92      82   10.92    83.2   10.72    90.3   10.86
    97.5   10.65   103.5   11.19   133.5   11.19
#Mann= 3 , 0 , 0
       0     .03       0    50.5     .03       0      82     .03       0
Bank Sta=50.5,82
Exp/Cntr=0.3,0.1

Type RM Length L Ch R = 1 ,100     ,50,50,50
#Sta/Elev= 24
       0    9.38     5.4    9.56    11.9    9.48    12.4    9.48    12.4    9.68
    15.4    9.61    15.4    9.41    16.4    8.93    19.9    7.22   20.23    7.06
    26.4    7.06    28.8    5.86    31.8    5.86    35.4    7.06   40.38    7.06
    40.6    7.17    45.2    9.44    45.2    9.79    47.1    9.79    48.3    9.79
    48.3    9.59    48.8    9.59    55.5    9.76      60    9.61
#Mann= 3 , 0 , 0
       0     .03       0    15.4     .03       0    45.2     .03       0
Levee=-1,15.4,9.61,-1,45.2,9.79,,
Bank Sta=15.4,45.2
Exp/Cntr=0.3,0.1

Type RM Length L Ch R = 1 ,99      ,50,50,50
#Sta/Elev= 22
       0     8.9     5.4    9.02    11.7    9.05    12.2    9.05    12.2    9.25
    15.2    9.25    16.8    8.59    19.7    7.19   20.28    6.91   27.65    6.91
   30.05    5.71   33.05    5.71   36.65    6.91   40.19    6.91    40.4    7.02
    45.2    9.44    47.1    9.44    48.3    9.44    48.3    9.24    48.8    9.24
    55.3    9.31      60    9.19
#Mann= 3 , 0 , 0
       0     .03       0    15.2     .03       0    45.2     .03       0
Levee=-1,15.2,9.25,-1,45.2,9.44,,
Bank Sta=15.2,45.2
Exp/Cntr=0.3,0.1

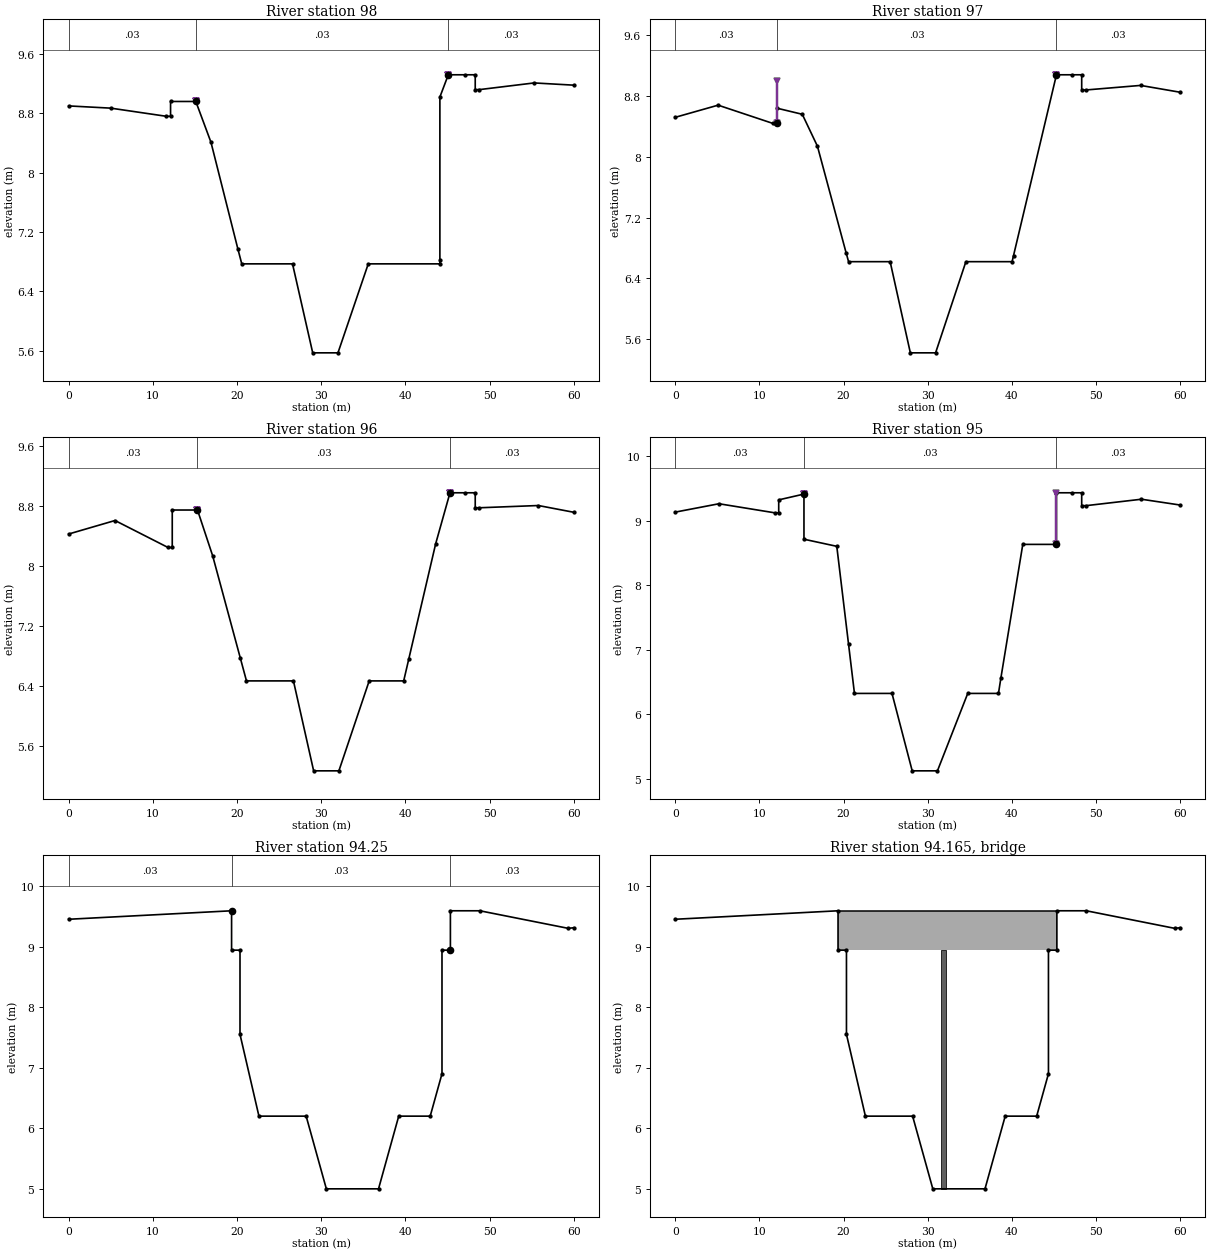
Type RM Length L Ch R = 1 ,98      ,50,50,50
#Sta/Elev= 23
       0     8.9       5    8.87    11.6    8.76    12.1    8.76    12.1    8.96
    15.1    8.96    16.9    8.41    20.1    6.97   20.56    6.77   26.59    6.77
   28.99    5.57   31.99    5.57   35.59    6.77    44.1    6.77    44.1    6.82
    44.1    9.02    45.1    9.32    47.1    9.32    48.3    9.32    48.3    9.12
    48.8    9.12    55.3    9.21      60    9.18
#Mann= 3 , 0 , 0
       0     .03       0    15.1     .03       0    45.1     .03       0
Levee=-1,15.1,8.96,-1,45.1,9.32,,
Bank Sta=15.1,45.1
Exp/Cntr=0.3,0.1

Type RM Length L Ch R = 1 ,97      ,50,50,50
#Sta/Elev= 22
       0    8.52     5.1    8.68    11.6    8.44    12.1    8.44    12.1    8.64
    15.1    8.56    16.9    8.14    20.3    6.74    20.6    6.62   25.54    6.62
   27.94    5.42   30.94    5.42   34.54    6.62   40.03    6.62    40.2     6.7
    45.3    9.08    47.1    9.08    48.3    9.08    48.3    8.88    48.8    8.88
    55.3    8.94      60    8.85
#Mann= 3 , 0 , 0
       0     .03       0    12.1     .03       0    45.3     .03       0
Levee=-1,12.1,9,-1,45.3,9.08,,
Bank Sta=12.1,45.3
Exp/Cntr=0.3,0.1

Type RM Length L Ch R = 1 ,96      ,50,50,50
#Sta/Elev= 23
       0    8.43     5.5    8.61    11.8    8.25    12.3    8.25    12.3    8.75
    15.3    8.75    17.1    8.14    20.4    6.77   21.12    6.47    26.7    6.47
    29.1    5.27    32.1    5.27    35.7    6.47    39.8    6.47    40.4    6.76
    43.6     8.3    45.3    8.98    47.1    8.98    48.3    8.98    48.3    8.78
    48.8    8.78    55.8    8.81      60    8.72
#Mann= 3 , 0 , 0
       0     .03       0    15.3     .03       0    45.3     .03       0
Levee=-1,15.3,8.75,-1,45.3,8.98,,
Bank Sta=15.3,45.3
Exp/Cntr=0.3,0.1

Type RM Length L Ch R = 1 ,95      ,25,25,25
#Sta/Elev= 25
       0    9.13     5.2    9.26    11.8    9.12    12.3    9.12    12.3    9.32
    15.3    9.41    15.3    8.71    19.2     8.6    20.6    7.08    21.3    6.32
   25.76    6.32   28.16    5.12   31.16    5.12   34.76    6.32   38.41    6.32
    38.7    6.56    41.3    8.63    45.3    8.63    45.3    9.43    47.1    9.43
    48.3    9.43    48.3    9.23    48.8    9.23    55.4    9.33      60    9.24
#Mann= 3 , 0 , 0
       0     .03       0    15.3     .03       0    45.3     .03       0
Levee=-1,15.3,9.41,-1,45.3,9.43,,
Bank Sta=15.3,45.3
Exp/Cntr=0.3,0.1

Type RM Length L Ch R = 1 ,94.25   ,17,17,17
#Sta/Elev= 18
       0    9.45   19.35    9.59   19.35    8.94   20.35    8.94   20.35    7.55
    22.6     6.2   28.21     6.2   30.61       5   36.81       5   39.21     6.2
   42.95     6.2   44.35     6.9   44.35    8.94   45.35    8.94   45.35    9.59
   48.85    9.59   59.35     9.3      60    9.31
#Mann= 3 , 0 , 0
       0     .03       0   19.35     .03       0   45.35     .03       0
Bank Sta=19.35,45.35
Exp/Cntr=0.5,0.3

Type RM Length L Ch R = 3 ,94.165  ,,,
BEGIN DESCRIPTION:
È­Á¤6±³
END DESCRIPTION:
Bridge Culvert--1,0,-1,-1, 0
Deck Dist Width WeirC Skew NumUp NumDn MinLoCord MaxHiCord MaxSubmerge Is_Ogee
0.1,15,1.44,0, 2, 2, , , 0.95, 0, 0,0,,
   19.35   45.35
    9.59    9.59
    8.94    8.94
   19.35   45.35
    9.59    9.59
    8.94    8.94
Pier Skew, UpSta & Num, DnSta & Num=  ,31.87, 2 ,31.87, 2 , 0 , 0 , 0 ,,
      .6      .6
       5      10
      .6      .6
       5      10
BR Coef=-1 , 0 , 0 ,, 0 ,,,0.8,-1,,0,
WSPro=,,,, 1 ,,,, 0 ,,,, 0 ,,,,-1 ,-1 ,-1 , 0 , 0 , 0 , 0 , 0
BC Design=,, 0 ,, 0 ,,,,,,

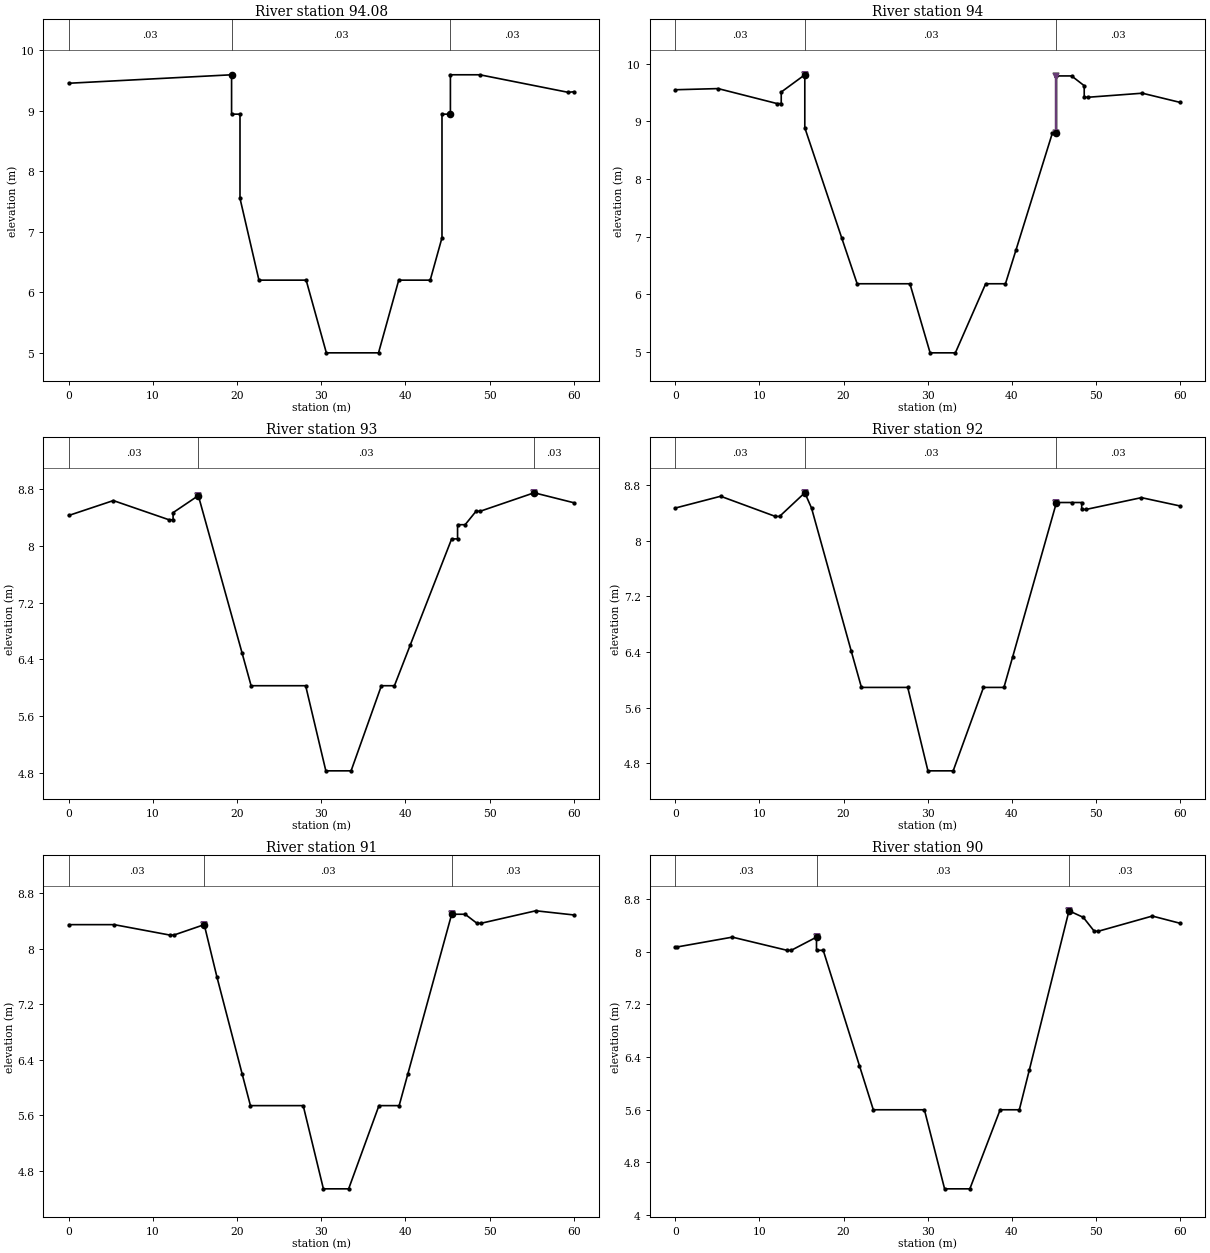
Type RM Length L Ch R = 1 ,94.08   ,8,8,8
#Sta/Elev= 18
       0    9.45   19.35    9.59   19.35    8.94   20.35    8.94   20.35    7.55
    22.6     6.2   28.21     6.2   30.61       5   36.81       5   39.21     6.2
   42.95     6.2   44.35     6.9   44.35    8.94   45.35    8.94   45.35    9.59
   48.85    9.59   59.35     9.3      60    9.31
#Mann= 3 , 0 , 0
       0     .03       0   19.35     .03       0   45.35     .03       0
Bank Sta=19.35,45.35
Exp/Cntr=0.5,0.3

Type RM Length L Ch R = 1 ,94      ,50,50,50
#Sta/Elev= 24
       0    9.55     5.1    9.57    12.1    9.31    12.6    9.31    12.6    9.51
    15.4    9.81    15.4    8.89    19.8    6.97   21.62    6.18   27.89    6.18
   30.29    4.98   33.29    4.98   36.89    6.18   39.24    6.18    40.5    6.77
    44.8    8.79    45.3    8.79    45.3    9.79    47.1    9.79    48.6    9.62
    48.6    9.42    49.1    9.42    55.5    9.49      60    9.33
#Mann= 3 , 0 , 0
       0     .03       0    15.4     .03       0    45.3     .03       0
Levee=-1,15.4,9.81,-1,45.3,9.79,,
Bank Sta=15.4,45.3
Exp/Cntr=0.3,0.1

Type RM Length L Ch R = 1 ,93      ,50,50,50
#Sta/Elev= 22
       0    8.43     5.3    8.64    11.9    8.37    12.4    8.37    12.4    8.47
    15.4    8.71    20.6    6.49   21.67    6.03   28.15    6.03   30.55    4.83
   33.55    4.83   37.15    6.03    38.7    6.03    40.6    6.61    45.5     8.1
    46.2     8.1    46.2     8.3    47.1     8.3    48.4    8.49    48.9    8.49
    55.3    8.75      60    8.61
#Mann= 3 , 0 , 0
       0     .03       0    15.4     .03       0    55.3     .03       0
Levee=-1,15.4,8.71,-1,55.3,8.75,,
Bank Sta=15.4,55.3
Exp/Cntr=0.3,0.1

Type RM Length L Ch R = 1 ,92      ,50,50,50
#Sta/Elev= 21
       0    8.47     5.4    8.64    11.9    8.35    12.4    8.35    15.4    8.69
    16.2    8.47    20.9    6.42   22.13    5.89   27.63    5.89   30.03    4.69
   33.03    4.69   36.63    5.89   39.06    5.89    40.1    6.33    45.3    8.55
    47.1    8.55    48.3    8.55    48.3    8.45    48.8    8.45    55.4    8.62
      60     8.5
#Mann= 3 , 0 , 0
       0     .03       0    15.4     .03       0    45.3     .03       0
Levee=-1,15.4,8.69,-1,45.3,8.55,,
Bank Sta=15.4,45.3
Exp/Cntr=0.3,0.1

Type RM Length L Ch R = 1 ,91      ,50,50,50
#Sta/Elev= 20
       0    8.35     5.4    8.35      12     8.2    12.5     8.2    16.1    8.35
    17.6     7.6    20.6     6.2   21.59    5.74   27.86    5.74   30.26    4.54
   33.26    4.54   36.86    5.74   39.26    5.74    40.3     6.2    45.5     8.5
    47.1     8.5    48.5    8.37      49    8.37    55.5    8.55      60    8.49
#Mann= 3 , 0 , 0
       0     .03       0    16.1     .03       0    45.5     .03       0
Levee=-1,16.1,8.35,-1,45.5,8.5,,
Bank Sta=16.1,45.5
Exp/Cntr=0.3,0.1

Type RM Length L Ch R = 1 ,90      ,50,50,50
#Sta/Elev= 22
       0    8.07     .19    8.07    6.79    8.22   13.29    8.02   13.79    8.02
   16.79    8.22   16.79    8.02   17.59    8.02   21.89    6.27   23.54     5.6
   29.61     5.6   32.01     4.4   35.01     4.4   38.61     5.6   40.89     5.6
   42.09    6.21   46.79    8.62   48.49    8.52   49.79    8.31   50.29    8.31
   56.69    8.54      60    8.43
#Mann= 3 , 0 , 0
       0     .03       0   16.79     .03       0   46.79     .03       0
Levee=-1,16.79,8.22,-1,46.79,8.62,,
Bank Sta=16.79,46.79
Exp/Cntr=0.3,0.1

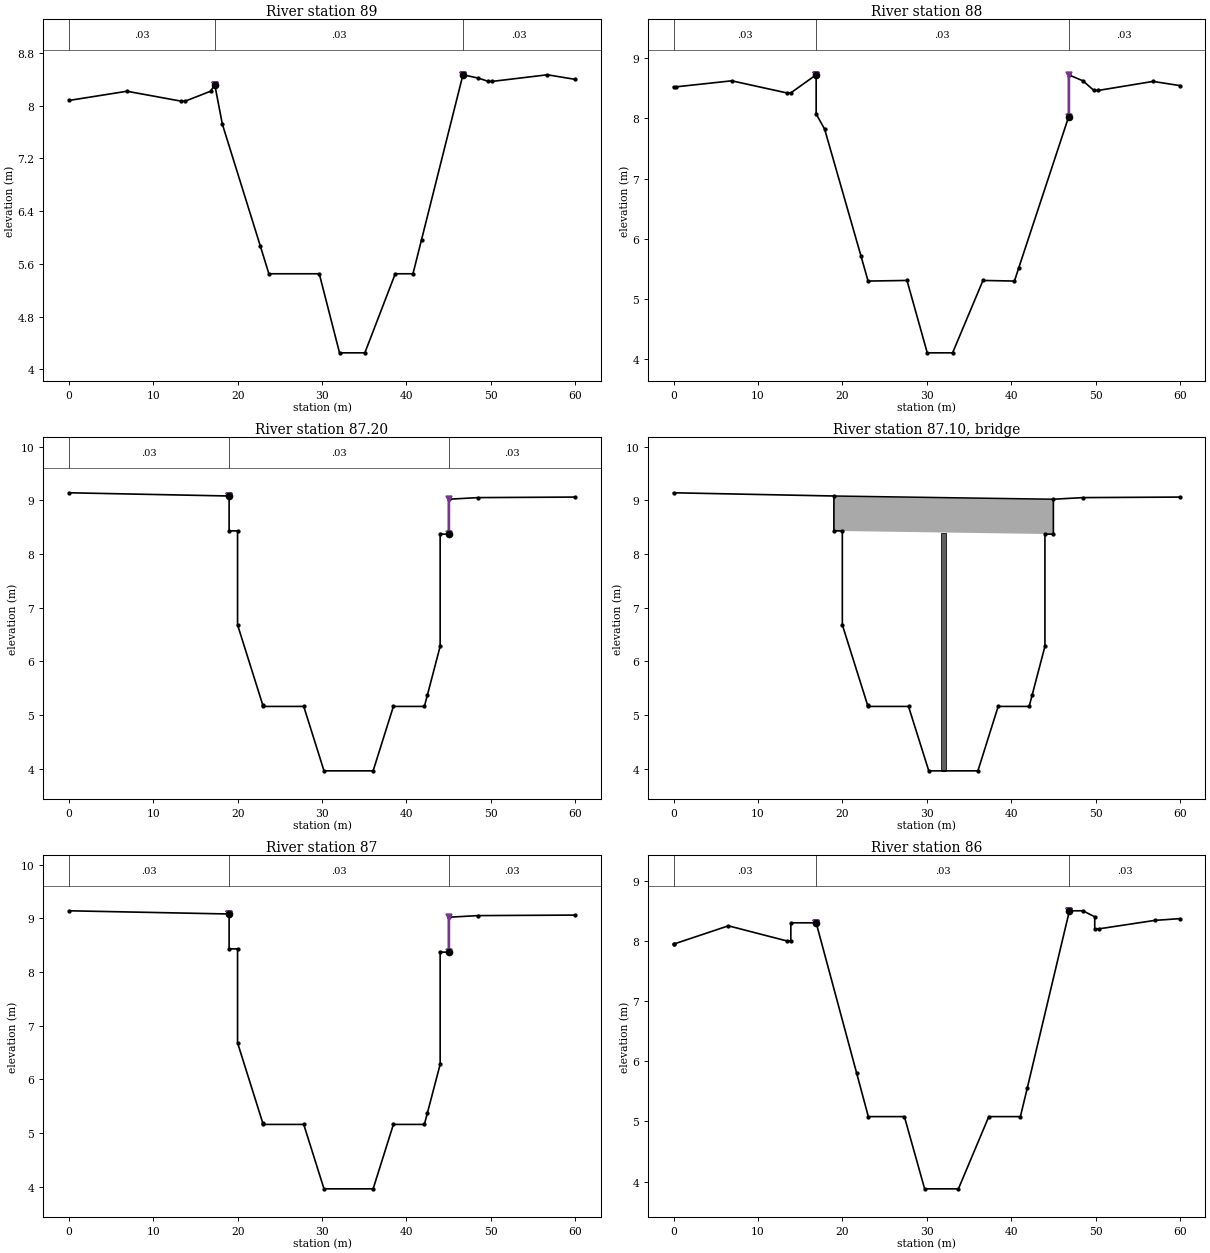
Type RM Length L Ch R = 1 ,89      ,50,50,50
#Sta/Elev= 21
       0    8.08    6.89    8.22   13.29    8.07   13.79    8.07   16.79    8.22
   17.29    8.32   18.19    7.72   22.69    5.87    23.7    5.45   29.67    5.45
   32.07    4.25   35.07    4.25   38.67    5.45   40.77    5.45   41.79    5.97
   46.69    8.47   48.49    8.42   49.69    8.37   50.19    8.37   56.69    8.47
      60     8.4
#Mann= 3 , 0 , 0
       0     .03       0   17.29     .03       0   46.69     .03       0
Levee=-1,17.29,8.32,-1,46.69,8.47,,
Bank Sta=17.29,46.69
Exp/Cntr=0.3,0.1

Type RM Length L Ch R = 1 ,88      ,30,30,30
#Sta/Elev= 23
       0    8.52     .29    8.52    6.89    8.62   13.39    8.42   13.89    8.42
   16.89    8.72   16.89    8.07   17.89    7.82   22.19    5.72   23.04     5.3
   27.65    5.31   30.05    4.11   33.05    4.11   36.65    5.31   40.38     5.3
   40.89    5.52   46.79    8.02   46.79    8.72   48.49    8.62   49.79    8.46
   50.29    8.46   56.79    8.61      60    8.54
#Mann= 3 , 0 , 0
       0     .03       0   16.89     .03       0   46.79     .03       0
Levee=-1,16.89,8.72,-1,46.79,8.72,,
Bank Sta=16.89,46.79
Exp/Cntr=0.3,0.1

Type RM Length L Ch R = 1 ,87.20   ,20,20,20
#Sta/Elev= 19
       0    9.14   18.99    9.08   18.99    8.43   19.99    8.43   19.99    6.68
   22.99    5.18   23.03    5.16   27.83    5.16   30.23    3.96   36.05    3.96
   38.45    5.16   42.12    5.16   42.49    5.38   43.99    6.28   43.99    8.37
   44.99    8.37   44.99    9.02   48.49    9.05      60    9.06
#Mann= 3 , 0 , 0
       0     .03       0   18.99     .03       0   44.99     .03       0
Levee=-1,18.99,9.08,-1,44.99,9.02,,
Bank Sta=18.99,44.99
Exp/Cntr=0.5,0.3

Type RM Length L Ch R = 3 ,87.10   ,,,
BEGIN DESCRIPTION:
È­Á¤5±³
END DESCRIPTION:
Bridge Culvert--1,0,-1,-1, 0
Deck Dist Width WeirC Skew NumUp NumDn MinLoCord MaxHiCord MaxSubmerge Is_Ogee
0.1,19,1.44,0, 2, 2, , , 0.95, 0, 0,0,,
   18.99   44.99
    9.08    9.02
    8.43    8.37
   18.99   44.99
    9.08    9.02
    8.43    8.37
Pier Skew, UpSta & Num, DnSta & Num=  ,32, 2 ,32, 2 , 0 , 0 , 0 ,,
      .6      .6
       4     9.5
      .6      .6
       4     9.5
BR Coef=-1 , 0 , 0 ,, 0 ,,,0.8,-1,,0,
WSPro=,,,, 1 ,,,, 0 ,,,, 0 ,,,,-1 ,-1 ,-1 , 0 , 0 , 0 , 0 , 0
BC Design=,, 0 ,, 0 ,,,,,,

Type RM Length L Ch R = 1 ,87      ,50,50,50
#Sta/Elev= 19
       0    9.14   18.99    9.08   18.99    8.43   19.99    8.43   19.99    6.68
   22.99    5.18   23.03    5.16   27.83    5.16   30.23    3.96   36.05    3.96
   38.45    5.16   42.12    5.16   42.49    5.38   43.99    6.28   43.99    8.37
   44.99    8.37   44.99    9.02   48.49    9.05      60    9.06
#Mann= 3 , 0 , 0
       0     .03       0   18.99     .03       0   44.99     .03       0
Levee=-1,18.99,9.08,-1,44.99,9.02,,
Bank Sta=18.99,44.99
Exp/Cntr=0.5,0.3

Type RM Length L Ch R = 1 ,86      ,50,50,50
#Sta/Elev= 22
       0    7.95     .09    7.95    6.49    8.25   13.39       8   13.89       8
   13.89     8.3   16.89     8.3   21.69     5.8   23.07    5.08   27.34    5.08
   29.74    3.88   33.74    3.88   37.34    5.08   41.08    5.08   41.89    5.55
   46.89     8.5   48.49     8.5   49.89     8.4   49.89     8.2   50.39     8.2
   56.99    8.34      60    8.37
#Mann= 3 , 0 , 0
       0     .03       0   16.89     .03       0   46.89     .03       0
Levee=-1,16.89,8.3,-1,46.89,8.5,,
Bank Sta=16.89,46.89
Exp/Cntr=0.3,0.1

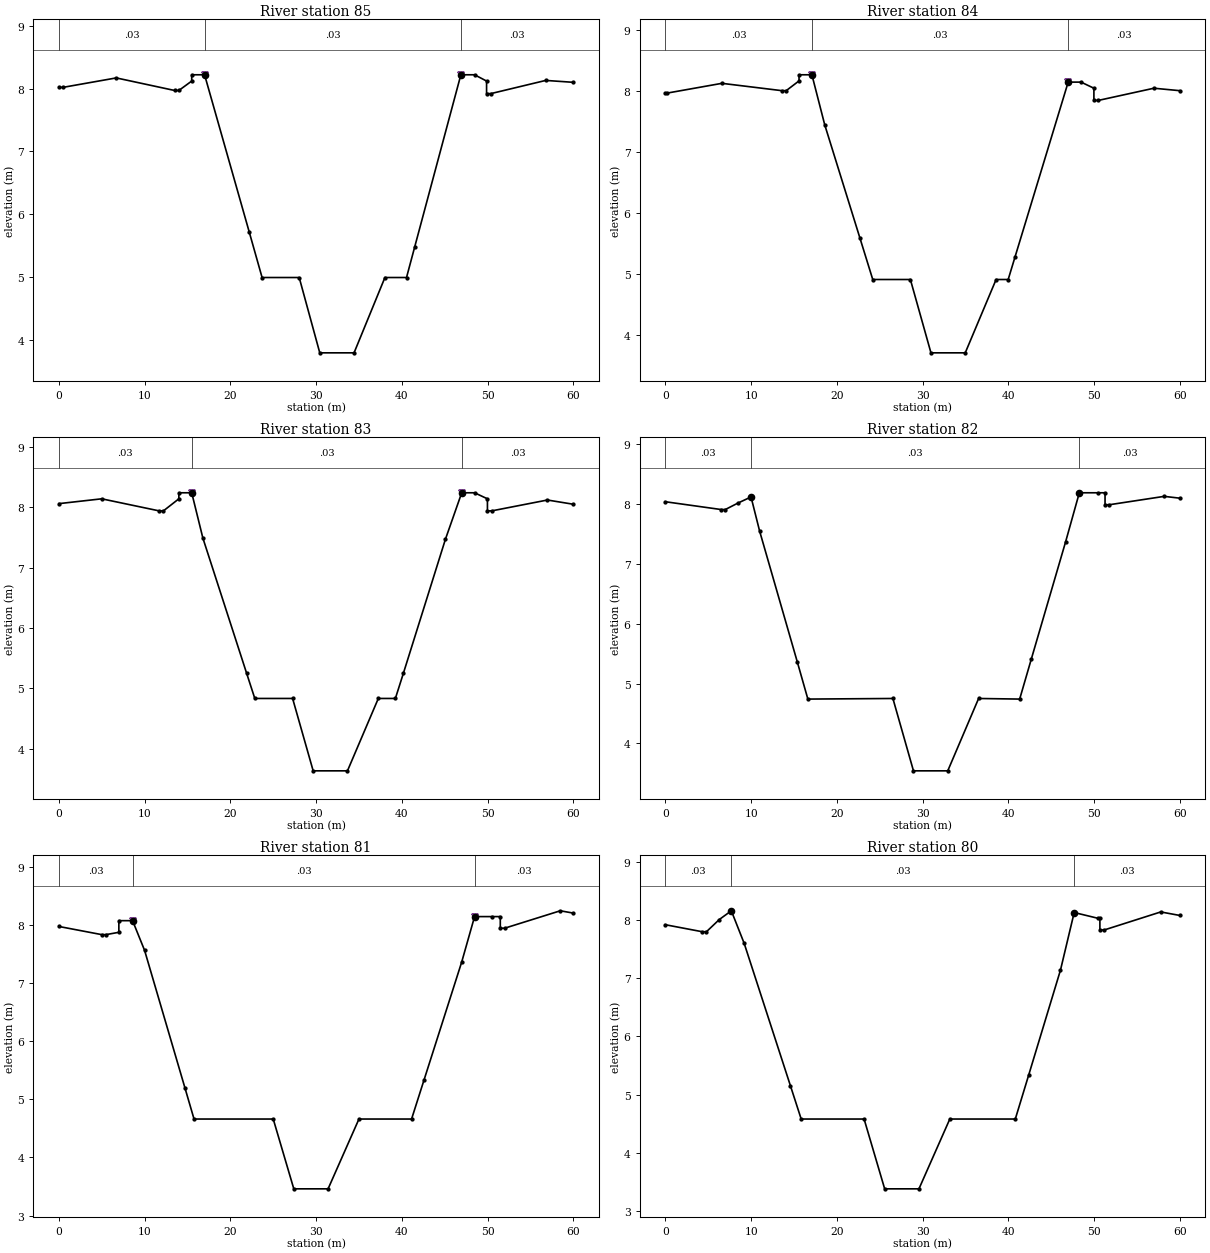
Type RM Length L Ch R = 1 ,85      ,50,50,50
#Sta/Elev= 23
       0    8.02     .49    8.02    6.69    8.17   13.49    7.97   13.99    7.97
   15.49    8.12   15.49    8.22   16.99    8.22   22.19    5.72    23.7    4.99
   28.03    4.99   30.43    3.79   34.43    3.79   38.03    4.99   40.55    4.99
   41.49    5.47   46.89    8.22   48.49    8.22   49.89    8.12   49.89    7.92
   50.39    7.92   56.79    8.13      60     8.1
#Mann= 3 , 0 , 0
       0     .03       0   16.99     .03       0   46.89     .03       0
Levee=-1,16.99,8.22,-1,46.89,8.22,,
Bank Sta=16.99,46.89
Exp/Cntr=0.3,0.1

Type RM Length L Ch R = 1 ,84      ,50,50,50
#Sta/Elev= 24
       0    7.96     .19    7.96    6.59    8.12   13.59       8   14.09       8
   15.59    8.16   15.59    8.26   17.09    8.26   18.59    7.44   22.69    5.59
   24.19    4.91   28.58    4.91   30.98    3.71   34.98    3.71   38.58    4.91
   39.99    4.91   40.79    5.28   46.99    8.14   48.49    8.14   49.99    8.04
   49.99    7.84   50.49    7.84   56.99    8.04      60       8
#Mann= 3 , 0 , 0
       0     .03       0   17.09     .03       0   46.99     .03       0
Levee=-1,17.09,8.26,-1,46.99,8.14,,
Bank Sta=17.09,46.99
Exp/Cntr=0.3,0.1

Type RM Length L Ch R = 1 ,83      ,50,50,50
#Sta/Elev= 24
       0    8.06    4.99    8.14   11.69    7.94   12.19    7.94   13.99    8.14
   13.99    8.24   15.49    8.24   16.79    7.49   21.89    5.25   22.85    4.83
   27.26    4.83   29.66    3.63   33.66    3.63   37.26    4.83   39.25    4.83
   40.19    5.25   45.09    7.47   46.99    8.24   48.49    8.24   49.99    8.14
   49.99    7.94   50.49    7.94   56.99    8.12      60    8.05
#Mann= 3 , 0 , 0
       0     .03       0   15.49     .03       0   46.99     .03       0
Levee=-1,15.49,8.24,-1,46.99,8.24,,
Bank Sta=15.49,46.99
Exp/Cntr=0.3,0.1

Type RM Length L Ch R = 1 ,82      ,50,50,50
#Sta/Elev= 22
       0    8.04    6.49    7.91    6.99    7.91    8.49    8.02    9.99    8.12
   10.99    7.55   15.39    5.36   16.62    4.74   26.54    4.75   28.94    3.54
   32.94    3.54   36.54    4.75   41.33    4.74   42.69    5.41   46.69    7.37
   48.29    8.19   50.49    8.19   51.29    8.19   51.29    7.99   51.79    7.99
   58.19    8.13      60     8.1
#Mann= 3 , 0 , 0
       0     .03       0    9.99     .03       0   48.29     .03       0
Bank Sta=9.99,48.29
Exp/Cntr=0.3,0.1

Type RM Length L Ch R = 1 ,81      ,50,50,50
#Sta/Elev= 23
       0    7.97    4.99    7.83    5.49    7.83    6.99    7.87    6.99    8.07
    8.59    8.07    9.99    7.56   14.69     5.2   15.76    4.66      25    4.66
    27.4    3.46    31.4    3.46      35    4.66   41.14    4.66   42.59    5.33
   46.99    7.36   48.49    8.14   50.49    8.14   51.49    8.14   51.49    7.94
   51.99    7.94   58.49    8.24      60     8.2
#Mann= 3 , 0 , 0
       0     .03       0    8.59     .03       0   48.49     .03       0
Levee=-1,8.59,8.07,-1,48.49,8.14,,
Bank Sta=8.59,48.49
Exp/Cntr=0.3,0.1

Type RM Length L Ch R = 1 ,80      ,50,50,50
#Sta/Elev= 22
       0    7.92    4.29     7.8    4.79     7.8    6.29    8.01    7.69    8.16
    9.19     7.6   14.59    5.15   15.84    4.58   23.18    4.58   25.58    3.38
   29.58    3.38   33.18    4.58   40.82    4.58   42.39    5.34   46.09    7.14
   47.69    8.13   50.49    8.03   50.69    8.03   50.69    7.83   51.19    7.83
   57.79    8.14      60    8.08
#Mann= 3 , 0 , 0
       0     .03       0    7.69     .03       0   47.69     .03       0
Bank Sta=7.69,47.69
Exp/Cntr=0.3,0.1