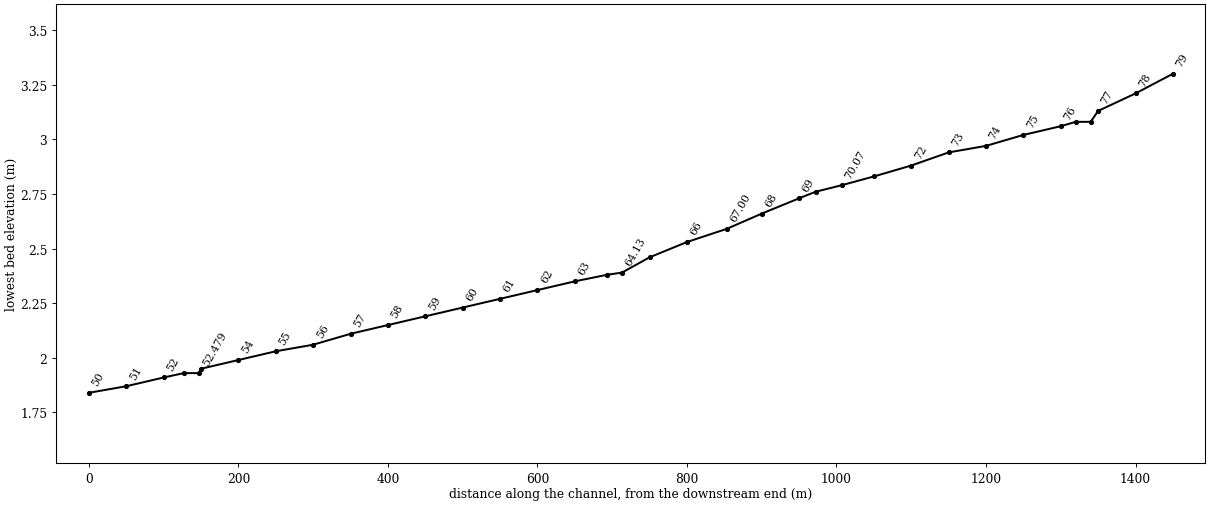
HEC-RAS study hj.prj: Hwajung_plan

--- hj.g01 (geometry) --- (continued)

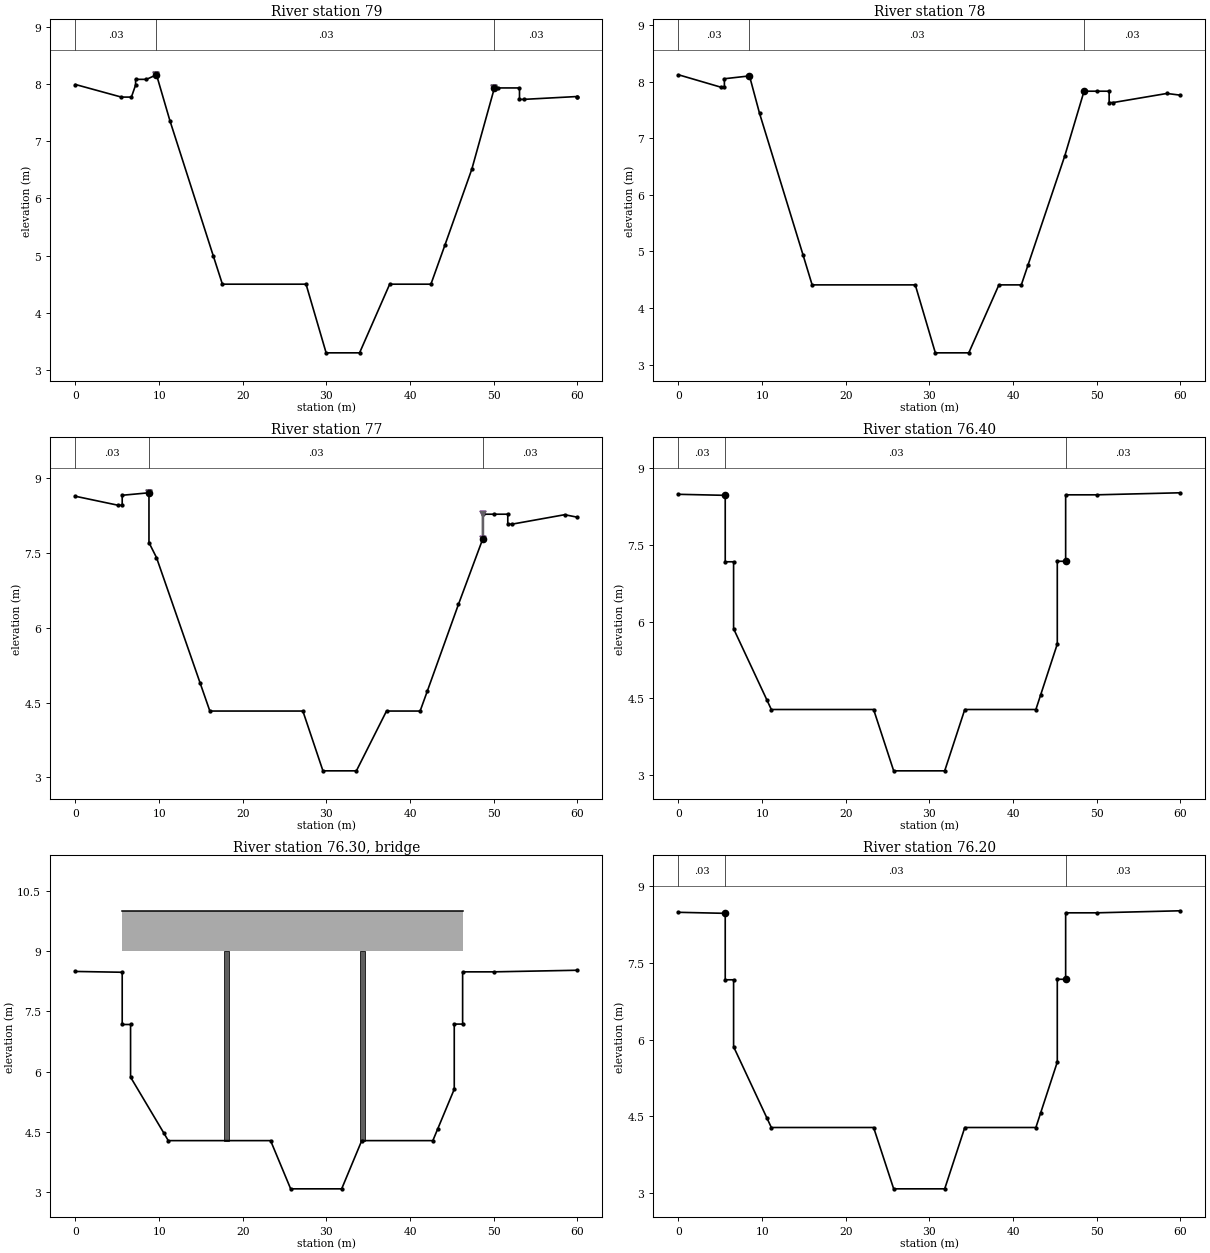
Type RM Length L Ch R = 1 ,79      ,50,50,50
#Sta/Elev= 24
       0    7.99    5.49    7.77    6.69    7.77    7.19    7.98    7.19    8.08
    8.49    8.08    9.69    8.16   11.29    7.36   16.49    4.99   17.57     4.5
   27.57     4.5   29.97     3.3   33.97     3.3   37.57     4.5    42.5     4.5
   44.19    5.19   47.39    6.51   50.09    7.93   50.49    7.93   53.09    7.93
   53.09    7.73   53.59    7.73   59.99    7.78      60    7.78
#Mann= 3 , 0 , 0
       0     .03       0    9.69     .03       0   50.09     .03       0
Levee=-1,9.69,8.16,-1,50.09,7.93,,
Bank Sta=9.69,50.09
Exp/Cntr=0.3,0.1

Type RM Length L Ch R = 1 ,78      ,50,50,50
#Sta/Elev= 22
       0    8.12    5.09     7.9    5.49     7.9    5.49    8.05    8.49     8.1
    9.69    7.44   14.89    4.94   15.98    4.41   28.31    4.41   30.71    3.21
   34.71    3.21   38.31    4.41   40.99    4.41   41.79    4.76   46.19    6.69
   48.49    7.83   49.99    7.83   51.49    7.83   51.49    7.63   51.99    7.63
   58.39    7.79      60    7.76
#Mann= 3 , 0 , 0
       0     .03       0    8.49     .03       0   48.49     .03       0
Bank Sta=8.49,48.49
Exp/Cntr=0.3,0.1

Type RM Length L Ch R = 1 ,77      ,10,10,10
#Sta/Elev= 24
       0    8.64    5.09    8.46    5.59    8.46    5.59    8.66    8.79    8.71
    8.79    7.71    9.69    7.41   14.89     4.9   16.07    4.33   27.19    4.33
   29.59    3.13   33.59    3.13   37.19    4.33   41.21    4.33   42.09    4.74
   45.79    6.47   48.69    7.78   48.69    8.28   49.99    8.28   51.69    8.28
   51.69    8.08   52.19    8.08   58.49    8.27      60    8.22
#Mann= 3 , 0 , 0
       0     .03       0    8.79     .03       0   48.69     .03       0
Levee=-1,8.79,8.71,-1,48.69,8.28,,
Bank Sta=8.79,48.69
Exp/Cntr=0.3,0.1

Type RM Length L Ch R = 1 ,76.40   ,20,20,20
#Sta/Elev= 19
       0    8.49    5.59    8.47    5.59    7.17    6.59    7.17    6.59    5.86
   10.59    4.46    11.1    4.28   23.33    4.28   25.73    3.08   31.83    3.08
   34.23    4.28   42.73    4.28   43.29    4.56   45.29    5.56   45.29    7.18
   46.29    7.18   46.29    8.48   49.99    8.48      60    8.52
#Mann= 3 , 0 , 0
       0     .03       0    5.59     .03       0   46.29     .03       0
Bank Sta=5.59,46.29
Exp/Cntr=0.5,0.3

Type RM Length L Ch R = 3 ,76.30   ,,,
BEGIN DESCRIPTION:
È­Á¤4±³(°³·®)
END DESCRIPTION:
Bridge Culvert--1,0,-1,-1, 0
Deck Dist Width WeirC Skew NumUp NumDn MinLoCord MaxHiCord MaxSubmerge Is_Ogee
0.1,19,1.44,0, 2, 2, , , 0.95, 0, 0,0,,
    5.59   46.29
      10      10
       9       9
    5.59   46.29
      10      10
       9       9
Pier Skew, UpSta & Num, DnSta & Num=  ,18.1, 2 ,18.1, 2 , 0 , 0 , 0 ,,
      .6      .6
     3.5       9
      .6      .6
     3.5       9
Pier Skew, UpSta & Num, DnSta & Num=  ,34.31, 2 ,34.31, 2 , 0 , 0 , 0 ,,
      .6      .6
     3.5       9
      .6      .6
     3.5       9
BR Coef=-1 , 0 , 0 ,, 0 ,,,0.8,-1,,0,
WSPro=,,,, 1 ,,,, 0 ,,,, 0 ,,,,-1 ,-1 ,-1 , 0 , 0 , 0 , 0 , 0
BC Design=,, 0 ,, 0 ,,,,,,

Type RM Length L Ch R = 1 ,76.20   ,20,20,20
#Sta/Elev= 19
       0    8.49    5.59    8.47    5.59    7.17    6.59    7.17    6.59    5.86
   10.59    4.46    11.1    4.28   23.33    4.28   25.73    3.08   31.83    3.08
   34.23    4.28   42.73    4.28   43.29    4.56   45.29    5.56   45.29    7.18
   46.29    7.18   46.29    8.48   49.99    8.48      60    8.52
#Mann= 3 , 0 , 0
       0     .03       0    5.59     .03       0   46.29     .03       0
Bank Sta=5.59,46.29
Exp/Cntr=0.5,0.3

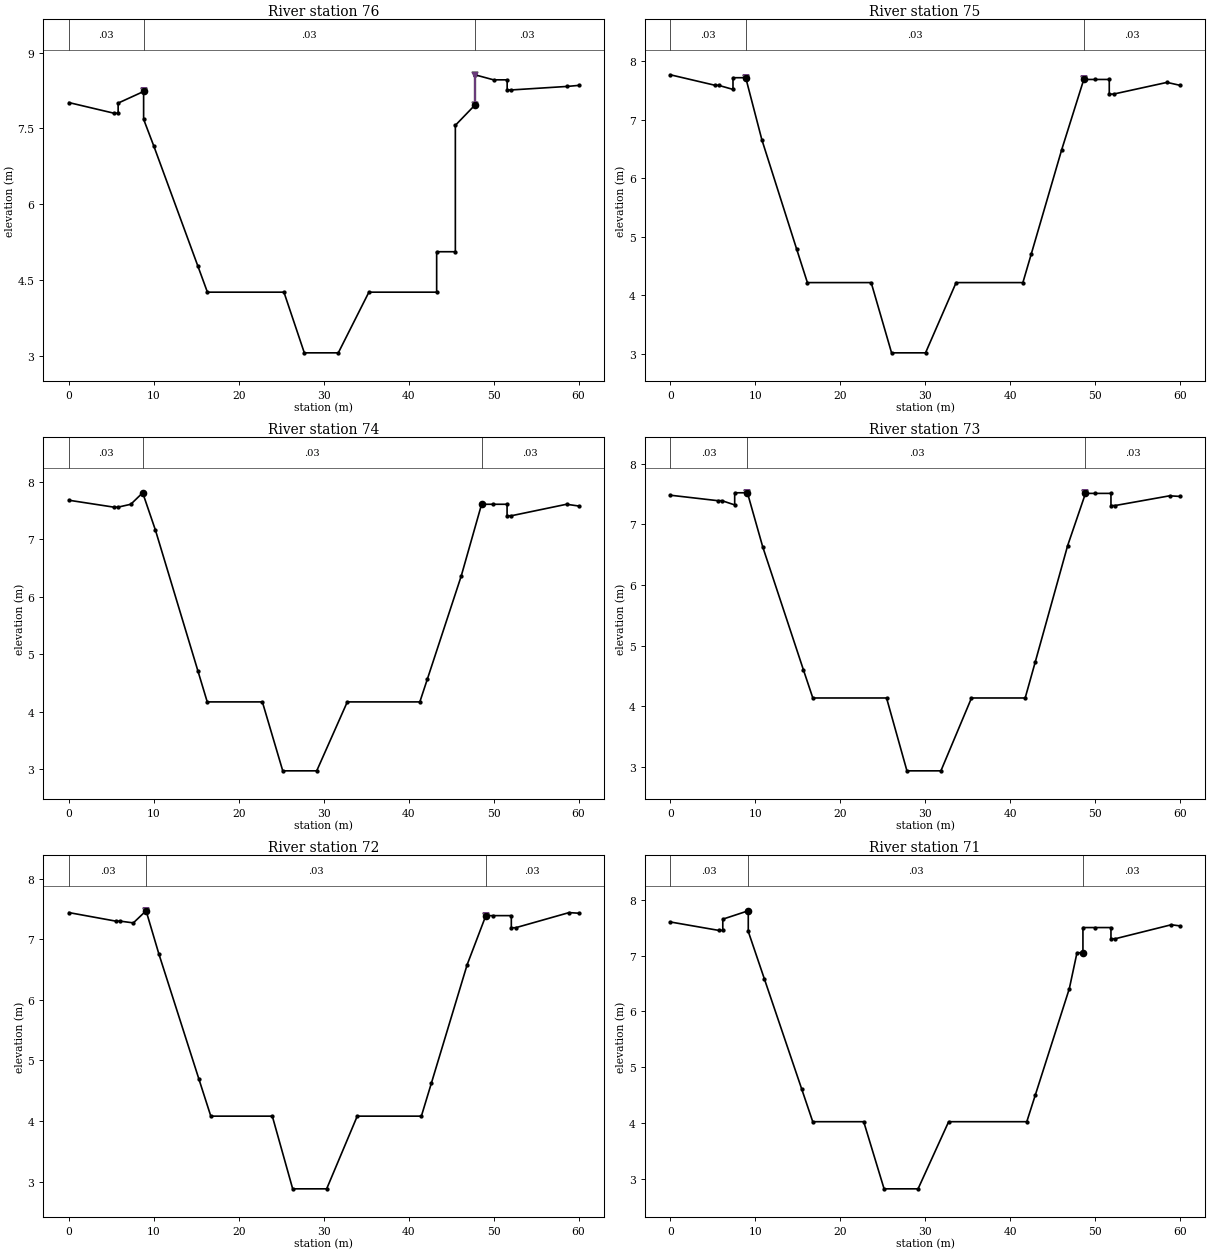
Type RM Length L Ch R = 1 ,76      ,50,50,50
#Sta/Elev= 25
       0    8.01    5.29     7.8    5.79     7.8    5.79       8    8.79    8.23
    8.79    7.68    9.99    7.15   15.19    4.77    16.3    4.26   25.31    4.26
   27.71    3.06   31.71    3.06   35.31    4.26   43.29    4.26   43.29    5.06
   45.49    5.06   45.49    7.56   47.79    7.96   47.79    8.56   49.99    8.46
   51.59    8.46   51.59    8.26   52.09    8.26   58.69    8.33      60    8.35
#Mann= 3 , 0 , 0
       0     .03       0    8.79     .03       0   47.79     .03       0
Levee=-1,8.79,8.23,-1,47.79,8.56,,
Bank Sta=8.79,47.79
Exp/Cntr=0.3,0.1

Type RM Length L Ch R = 1 ,75      ,50,50,50
#Sta/Elev= 23
       0    7.77    5.28    7.59    5.68    7.59    7.38    7.52    7.38    7.72
    8.88    7.72   10.78    6.66   14.88    4.79   16.14    4.22   23.65    4.22
   26.05    3.02   30.05    3.02   33.65    4.22   41.51    4.22   42.48     4.7
   46.08    6.49   48.68    7.69   49.98    7.69   51.68    7.69   51.68    7.44
   52.18    7.44   58.48    7.64      60    7.59
#Mann= 3 , 0 , 0
       0     .03       0    8.88     .03       0   48.68     .03       0
Levee=-1,8.88,7.72,-1,48.68,7.69,,
Bank Sta=8.88,48.68
Exp/Cntr=0.3,0.1

Type RM Length L Ch R = 1 ,74      ,50,50,50
#Sta/Elev= 22
       0    7.68    5.28    7.56    5.78    7.56    7.28    7.61    8.68    7.81
   10.18    7.16   15.18    4.71   16.28    4.17   22.77    4.17   25.17    2.97
   29.17    2.97   32.77    4.17   41.31    4.17   42.18    4.56   46.18    6.36
   48.58    7.61   49.98    7.61   51.58    7.61   51.58    7.41   52.08    7.41
   58.58    7.61      60    7.58
#Mann= 3 , 0 , 0
       0     .03       0    8.68     .03       0   48.58     .03       0
Bank Sta=8.68,48.58
Exp/Cntr=0.3,0.1

Type RM Length L Ch R = 1 ,73      ,50,50,50
#Sta/Elev= 23
       0    7.48    5.58    7.39    6.08    7.39    7.58    7.32    7.58    7.52
    9.08    7.52   10.88    6.63   15.68     4.6   16.78    4.14   25.46    4.14
   27.86    2.94   31.86    2.94   35.46    4.14   41.78    4.14   42.98    4.74
   46.78    6.65   48.88    7.51   49.98    7.51   51.88    7.51   51.88    7.31
   52.38    7.31   58.78    7.47      60    7.46
#Mann= 3 , 0 , 0
       0     .03       0    9.08     .03       0   48.88     .03       0
Levee=-1,9.08,7.52,-1,48.88,7.51,,
Bank Sta=9.08,48.88
Exp/Cntr=0.3,0.1

Type RM Length L Ch R = 1 ,72      ,50,50,50
#Sta/Elev= 22
       0    7.44    5.48     7.3    5.98     7.3    7.58    7.27    9.08    7.47
   10.58    6.76   15.28     4.7    16.7    4.08   23.94    4.08   26.34    2.88
   30.34    2.88   33.94    4.08   41.49    4.08   42.68    4.63   46.88    6.58
   49.08    7.39   49.98    7.39   52.08    7.39   52.08    7.19   52.58    7.19
   58.88    7.44      60    7.43
#Mann= 3 , 0 , 0
       0     .03       0    9.08     .03       0   49.08     .03       0
Levee=-1,9.08,7.47,-1,49.08,7.39,,
Bank Sta=9.08,49.08
Exp/Cntr=0.3,0.1

Type RM Length L Ch R = 1 ,71      ,43,43,43
#Sta/Elev= 25
       0     7.6    5.68    7.45    6.18    7.45    6.18    7.65    9.18     7.8
    9.18    7.43   11.08    6.58   15.48    4.61   16.77    4.03   22.77    4.03
   25.17    2.83   29.17    2.83   32.77    4.03   41.97    4.03   42.98    4.51
   46.98    6.41   47.88    7.05   48.58    7.05   48.58     7.5   49.98     7.5
   51.88     7.5   51.88     7.3   52.38     7.3   58.98    7.55      60    7.53
#Mann= 3 , 0 , 0
       0     .03       0    9.18     .03       0   48.58     .03       0
Bank Sta=9.18,48.58
Exp/Cntr=0.3,0.1

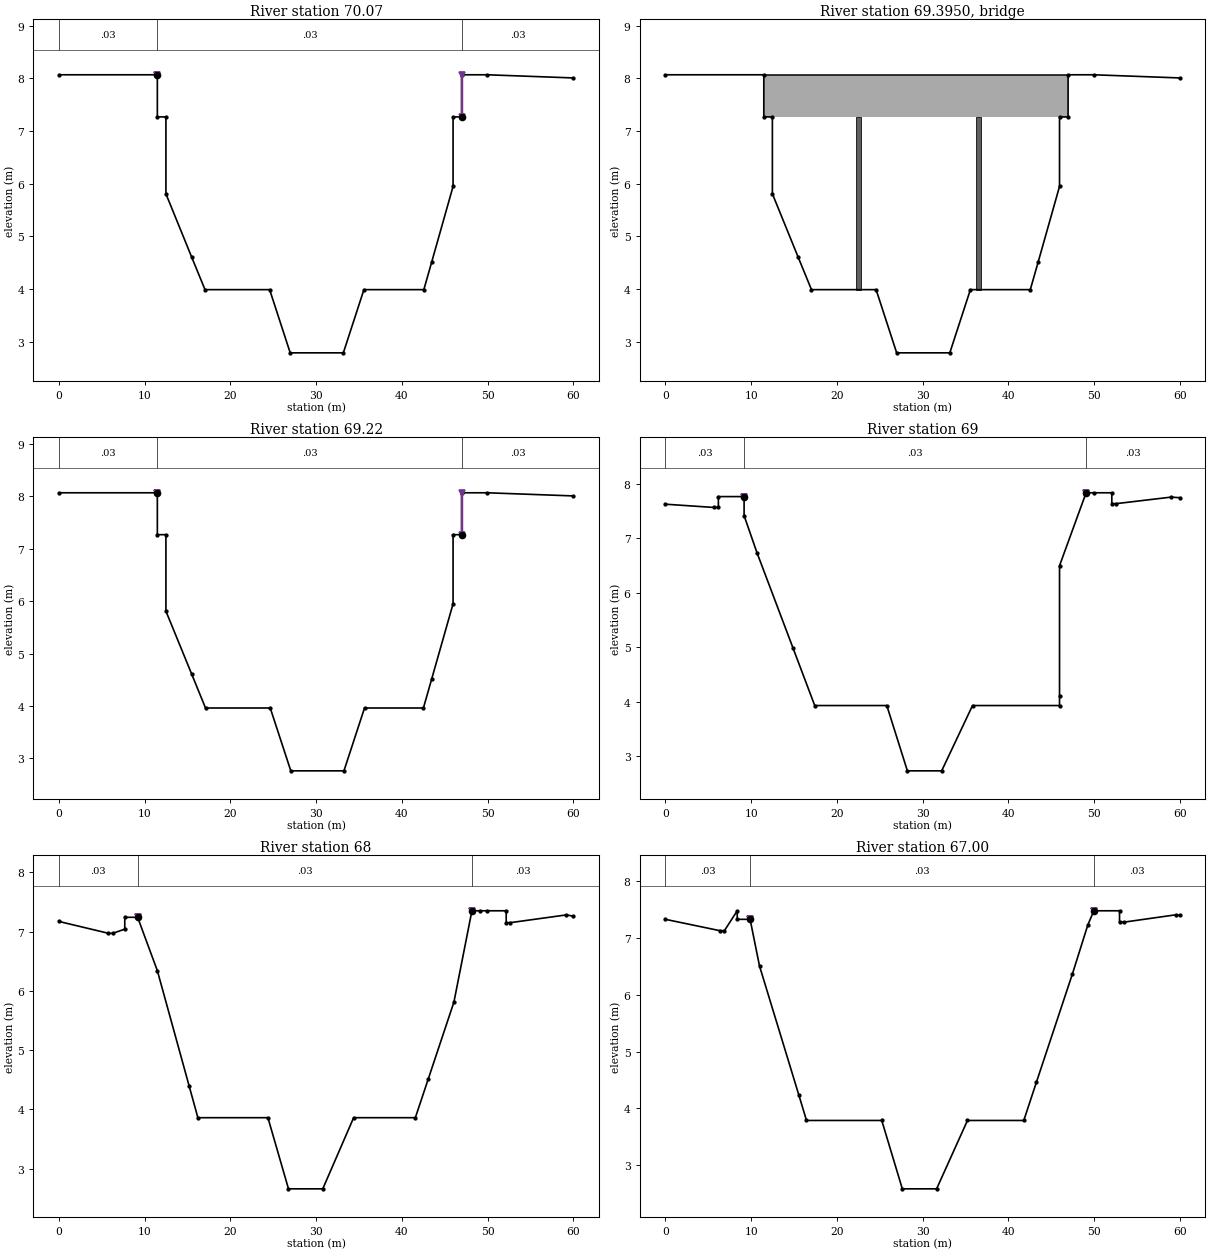
Type RM Length L Ch R = 1 ,70.07   ,35,35,35
#Sta/Elev= 19
       0    8.07   11.48    8.07   11.48    7.27   12.48    7.27   12.48    5.81
   15.48    4.61   17.04    3.99   24.58    3.99   26.98    2.79   33.18    2.79
   35.58    3.99   42.57    3.99   43.48    4.51   45.98    5.95   45.98    7.27
   46.98    7.27   46.98    8.07   49.98    8.07      60    8.01
#Mann= 3 , 0 , 0
       0     .03       0   11.48     .03       0   46.98     .03       0
Levee=-1,11.48,8.07,-1,46.98,8.07,,
Bank Sta=11.48,46.98
Exp/Cntr=0.5,0.3

Type RM Length L Ch R = 3 ,69.3950 ,,,
BEGIN DESCRIPTION:
È­Á¤3±³
END DESCRIPTION:
Bridge Culvert--1,0,-1,-1, 0
Deck Dist Width WeirC Skew NumUp NumDn MinLoCord MaxHiCord MaxSubmerge Is_Ogee
0.1,34,1.44,0, 2, 2, , , 0.95, 0, 0,0,,
   11.48   46.98
    8.07    8.07
    7.27    7.27
   11.48   46.98
    8.07    8.07
    7.27    7.27
Pier Skew, UpSta & Num, DnSta & Num=  ,22.48, 2 ,22.48, 2 , 0 , 0 , 0 ,,
      .6      .6
     3.5       8
      .6      .6
     3.5       8
Pier Skew, UpSta & Num, DnSta & Num=  ,36.5, 2 ,36.5, 2 , 0 , 0 , 0 ,,
      .6      .6
     3.5       8
      .6      .6
     3.5       8
BR Coef=-1 , 0 , 0 ,, 0 ,,,0.8,-1,,0,
WSPro=,,,, 1 ,,,, 0 ,,,, 0 ,,,,-1 ,-1 ,-1 , 0 , 0 , 0 , 0 , 0
BC Design=,, 0 ,, 0 ,,,,,,

Type RM Length L Ch R = 1 ,69.22   ,22,22,22
#Sta/Elev= 19
       0    8.07   11.48    8.07   11.48    7.27   12.48    7.27   12.48    5.81
   15.48    4.61    17.1    3.96   24.65    3.96   27.05    2.76   33.25    2.76
   35.65    3.96   42.52    3.96   43.48    4.51   45.98    5.95   45.98    7.27
   46.98    7.27   46.98    8.07   49.98    8.07      60    8.01
#Mann= 3 , 0 , 0
       0     .03       0   11.48     .03       0   46.98     .03       0
Levee=-1,11.48,8.07,-1,46.98,8.07,,
Bank Sta=11.48,46.98
Exp/Cntr=0.5,0.3

Type RM Length L Ch R = 1 ,69      ,50,50,50
#Sta/Elev= 23
       0    7.63    5.68    7.57    6.18    7.57    6.18    7.77    9.18    7.77
    9.18    7.42   10.68    6.74   14.88    4.99   17.42    3.93   25.83    3.93
   28.23    2.73   32.23    2.73   35.83    3.93   45.98    3.93   45.98     4.1
   45.98     6.5   49.08    7.84   49.98    7.84   52.08    7.84   52.08    7.64
   52.58    7.64   58.98    7.76      60    7.75
#Mann= 3 , 0 , 0
       0     .03       0    9.18     .03       0   49.08     .03       0
Levee=-1,9.18,7.77,-1,49.08,7.84,,
Bank Sta=9.18,49.08
Exp/Cntr=0.3,0.1

Type RM Length L Ch R = 1 ,68      ,47,47,47
#Sta/Elev= 24
       0    7.17    5.78    6.97    6.28    6.97    7.68    7.04    7.68    7.24
    9.18    7.24   11.48    6.34   15.18     4.4   16.21    3.86   24.38    3.86
   26.78    2.66   30.78    2.66   34.38    3.86   41.58    3.86   43.08    4.51
   46.08    5.81   48.18    7.35   49.18    7.35   49.98    7.35   52.18    7.35
   52.18    7.15   52.68    7.15   59.18    7.28      60    7.26
#Mann= 3 , 0 , 0
       0     .03       0    9.18     .03       0   48.18     .03       0
Levee=-1,9.18,7.24,-1,48.18,7.35,,
Bank Sta=9.18,48.18
Exp/Cntr=0.3,0.1

Type RM Length L Ch R = 1 ,67.00   ,53,53,53
#Sta/Elev= 23
       0    7.32    6.38    7.12    6.88    7.12    8.38    7.47    8.38    7.32
    9.88    7.32   10.98     6.5   15.58    4.23   16.46    3.79   25.24    3.79
   27.64    2.59   31.64    2.59   35.24    3.79   41.81    3.79   43.28    4.46
   47.48    6.36   49.28    7.22   49.98    7.47   52.98    7.47   52.98    7.27
   53.48    7.27   59.58     7.4      60    7.39
#Mann= 3 , 0 , 0
       0     .03       0    9.88     .03       0   49.98     .03       0
Levee=-1,9.88,7.32,-1,49.98,7.47,,
Bank Sta=9.88,49.98
Exp/Cntr=0.5,0.3

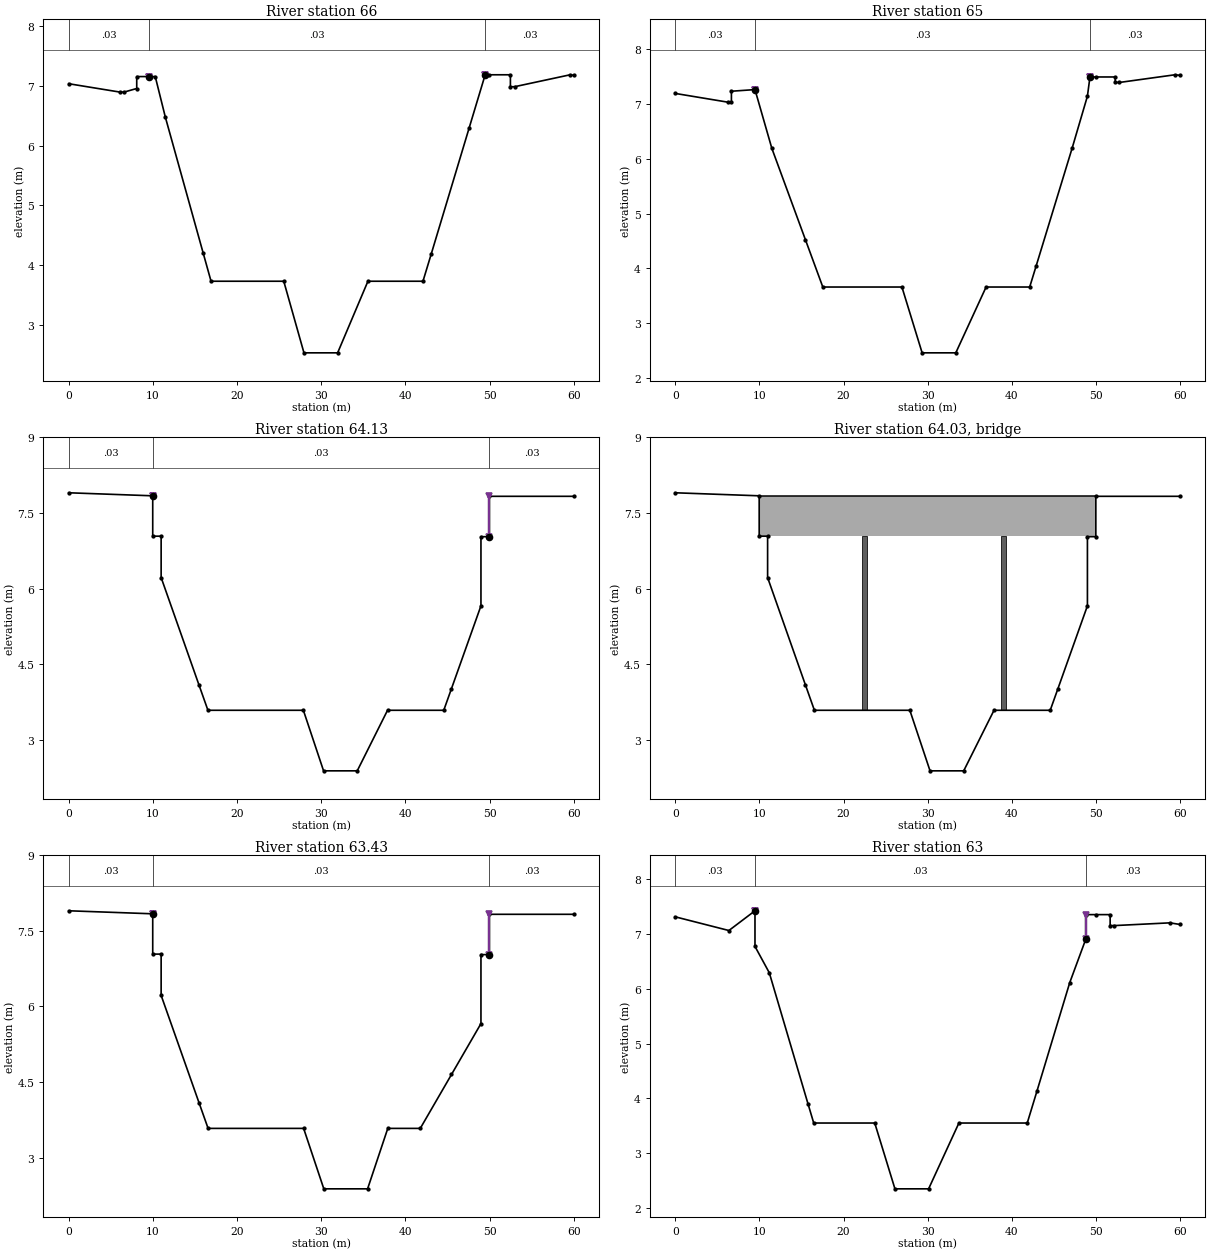
Type RM Length L Ch R = 1 ,66      ,50,50,50
#Sta/Elev= 24
       0    7.04    6.08     6.9    6.58     6.9    8.08    6.96    8.08    7.16
    9.58    7.16   10.28    7.16   11.48    6.48   15.98     4.2   16.91    3.73
   25.55    3.73   27.95    2.53   31.95    2.53   35.55    3.73   42.09    3.73
   43.08    4.19   47.58     6.3   49.48    7.19   49.98    7.19   52.48    7.19
   52.48    6.99   52.98    6.99   59.58    7.19      60    7.18
#Mann= 3 , 0 , 0
       0     .03       0    9.58     .03       0   49.48     .03       0
Levee=-1,9.58,7.16,-1,49.48,7.19,,
Bank Sta=9.58,49.48
Exp/Cntr=0.3,0.1

Type RM Length L Ch R = 1 ,65      ,37,37,37
#Sta/Elev= 23
       0    7.19    6.28    7.03    6.68    7.03    6.68    7.23    9.48    7.26
   11.48    6.19   15.48    4.52   17.54    3.66   26.94    3.66   29.34    2.46
   33.34    2.46   36.94    3.66   42.12    3.66   42.88    4.04   47.18     6.2
   48.98    7.14   49.28    7.49   49.98    7.49   52.28    7.49   52.28    7.39
   52.78    7.39   59.38    7.53      60    7.52
#Mann= 3 , 0 , 0
       0     .03       0    9.48     .03       0   49.28     .03       0
Levee=-1,9.48,7.26,-1,49.28,7.49,,
Bank Sta=9.48,49.28
Exp/Cntr=0.3,0.1

Type RM Length L Ch R = 1 ,64.13   ,20,20,20
#Sta/Elev= 18
       0     7.9    9.98    7.84    9.98    7.04   10.98    7.04   10.98    6.22
   15.48    4.09   16.54    3.59   27.88    3.59   30.28    2.39   34.28    2.39
   37.88    3.59   44.56    3.59   45.48    4.02   48.98    5.66   48.98    7.03
   49.98    7.03   49.98    7.83      60    7.83
#Mann= 3 , 0 , 0
       0     .03       0    9.98     .03       0   49.98     .03       0
Levee=-1,9.98,7.84,-1,49.98,7.83,,
Bank Sta=9.98,49.98
Exp/Cntr=0.5,0.3

Type RM Length L Ch R = 3 ,64.03   ,,,
BEGIN DESCRIPTION:
È­Á¤2±³
END DESCRIPTION:
Bridge Culvert--1,0,-1,-1, 0
Deck Dist Width WeirC Skew NumUp NumDn MinLoCord MaxHiCord MaxSubmerge Is_Ogee
0.1,19,1.44,0, 2, 2, , , 0.95, 0, 0,0,,
    9.98   49.98
    7.84    7.84
    7.04    7.04
    9.98   49.98
    7.84    7.84
    7.04    7.04
Pier Skew, UpSta & Num, DnSta & Num=  ,22.48, 2 ,22.48, 2 , 0 , 0 , 0 ,,
      .6      .6
       3     8.7
      .6      .6
       3     8.7
Pier Skew, UpSta & Num, DnSta & Num=  ,39, 2 ,39, 2 , 0 , 0 , 0 ,,
      .6      .6
       3     8.7
      .6      .6
       3     8.7
BR Coef=-1 , 0 , 0 ,, 0 ,,,0.8,-1,,0,
WSPro=,,,, 1 ,,,, 0 ,,,, 0 ,,,,-1 ,-1 ,-1 , 0 , 0 , 0 , 0 , 0
BC Design=,, 0 ,, 0 ,,,,,,

Type RM Length L Ch R = 1 ,63.43   ,43,43,43
#Sta/Elev= 18
       0     7.9    9.98    7.84    9.98    7.04   10.98    7.04   10.98    6.22
   15.48    4.09   16.56    3.58   27.91    3.58   30.31    2.38   35.51    2.38
   37.91    3.58   41.77    3.58   45.48    4.65   48.98    5.66   48.98    7.03
   49.98    7.03   49.98    7.83      60    7.83
#Mann= 3 , 0 , 0
       0     .03       0    9.98     .03       0   49.98     .03       0
Levee=-1,9.98,7.84,-1,49.98,7.83,,
Bank Sta=9.98,49.98
Exp/Cntr=0.5,0.3

Type RM Length L Ch R = 1 ,63      ,50,50,50
#Sta/Elev= 22
       0    7.31    6.38    7.06    9.48    7.42    9.48    6.77   11.18    6.29
   15.78     3.9   16.46    3.55   23.71    3.55   26.11    2.35   30.11    2.35
   33.71    3.55   41.83    3.55   42.98    4.13   46.88    6.11   48.78     6.9
   48.78    7.35   49.98    7.35   51.68    7.35   51.68    7.15   52.18    7.15
   58.78     7.2      60    7.17
#Mann= 3 , 0 , 0
       0     .03       0    9.48     .03       0   48.78     .03       0
Levee=-1,9.48,7.42,-1,48.78,7.35,,
Bank Sta=9.48,48.78
Exp/Cntr=0.3,0.1

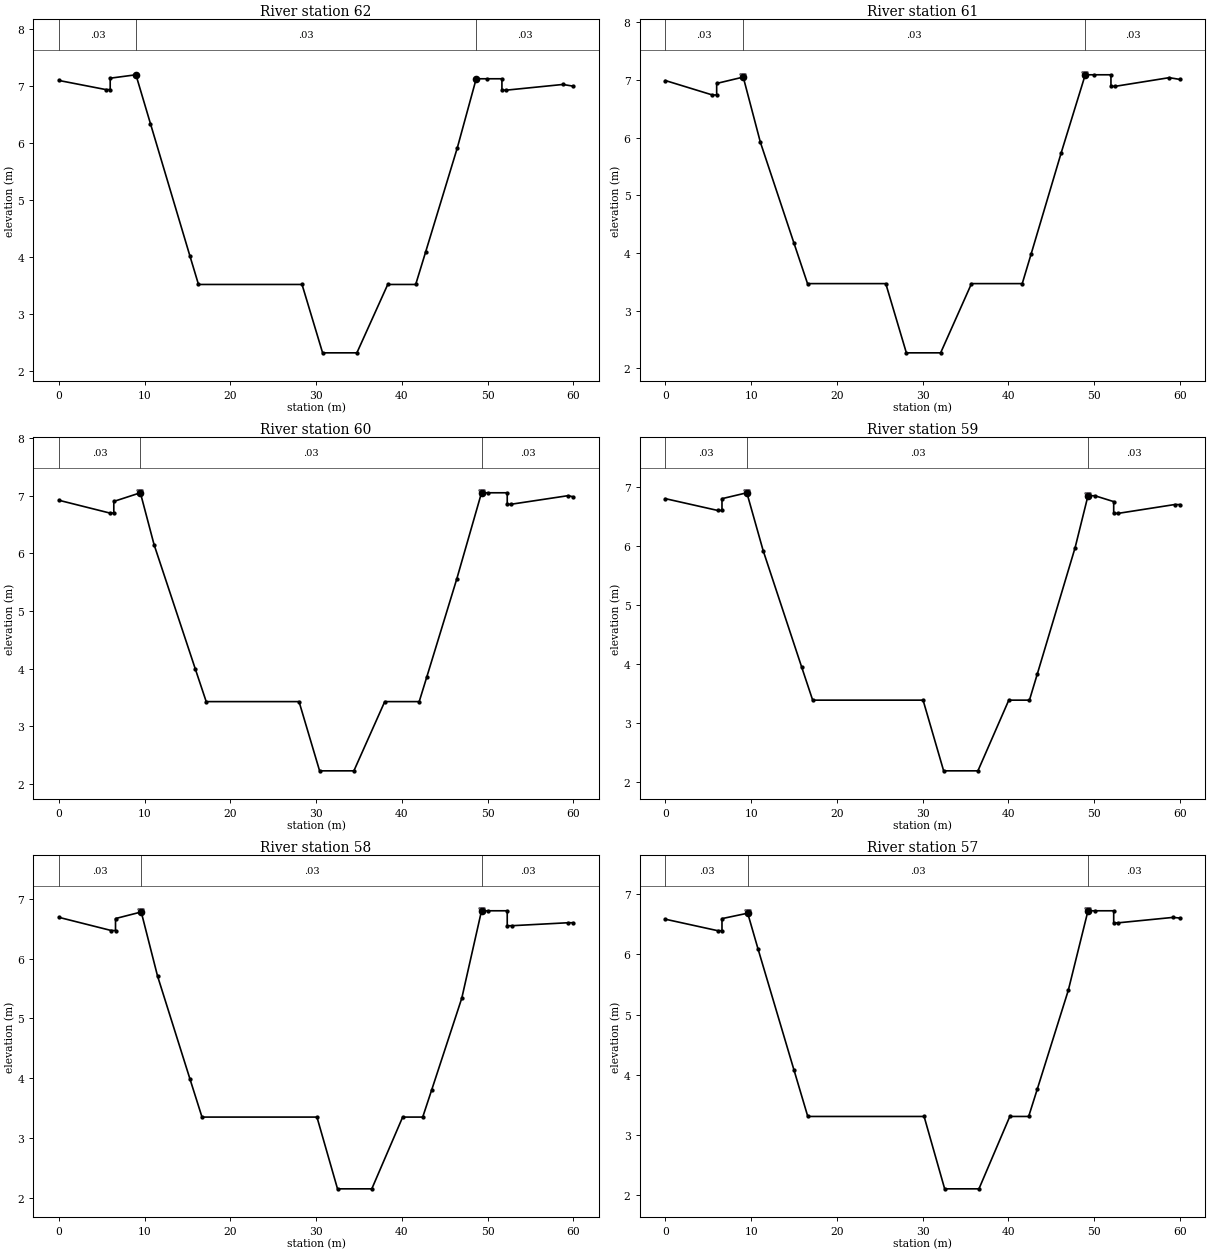
Type RM Length L Ch R = 1 ,62      ,50,50,50
#Sta/Elev= 22
       0    7.09    5.48    6.93    5.98    6.93    5.98    7.13    8.98    7.19
   10.68    6.33   15.28    4.01   16.28    3.51   28.36    3.51   30.76    2.31
   34.76    2.31   38.36    3.51   41.62    3.51   42.78    4.08   46.48    5.91
   48.68    7.12   49.98    7.12   51.68    7.12   51.68    6.92   52.18    6.92
   58.78    7.02      60    6.99
#Mann= 3 , 0 , 0
       0     .03       0    8.98     .03       0   48.68     .03       0
Bank Sta=8.98,48.68
Exp/Cntr=0.3,0.1

Type RM Length L Ch R = 1 ,61      ,50,50,50
#Sta/Elev= 22
       0    6.99    5.48    6.74    5.98    6.74    5.98    6.94    9.08    7.05
   11.08    5.92   14.98    4.18   16.58    3.47   25.71    3.47   28.11    2.27
   32.11    2.27   35.71    3.47   41.63    3.47   42.68    3.99   46.18    5.74
   48.98    7.09   49.98    7.09   51.98    7.09   51.98    6.89   52.48    6.89
   58.78    7.04      60    7.01
#Mann= 3 , 0 , 0
       0     .03       0    9.08     .03       0   48.98     .03       0
Levee=-1,9.08,7.05,-1,48.98,7.09,,
Bank Sta=9.08,48.98
Exp/Cntr=0.3,0.1

Type RM Length L Ch R = 1 ,60      ,50,50,50
#Sta/Elev= 22
       0    6.92     5.9     6.7     6.4     6.7     6.4     6.9     9.5    7.05
    11.1    6.15    15.9       4   17.18    3.43   28.01    3.43   30.41    2.23
   34.41    2.23   38.01    3.43   42.03    3.43    42.9    3.85    46.4    5.55
    49.3    7.05    50.1    7.05    52.3    7.05    52.3    6.85    52.7    6.85
    59.4       7      60    6.98
#Mann= 3 , 0 , 0
       0     .03       0     9.5     .03       0    49.3     .03       0
Levee=-1,9.5,7.05,-1,49.3,7.05,,
Bank Sta=9.5,49.3
Exp/Cntr=0.3,0.1

Type RM Length L Ch R = 1 ,59      ,50,50,50
#Sta/Elev= 22
       0    6.81     6.1    6.61     6.6    6.61     6.6    6.81     9.5    6.91
    11.4    5.93    15.9    3.95   17.18    3.39   30.06    3.39   32.46    2.19
   36.46    2.19   40.06    3.39   42.47    3.39    43.4    3.84    47.8    5.98
    49.3    6.86    50.1    6.86    52.3    6.76    52.3    6.56    52.8    6.56
    59.4    6.71      60    6.71
#Mann= 3 , 0 , 0
       0     .03       0     9.5     .03       0    49.3     .03       0
Levee=-1,9.5,6.91,-1,49.3,6.86,,
Bank Sta=9.5,49.3
Exp/Cntr=0.3,0.1

Type RM Length L Ch R = 1 ,58      ,50,50,50
#Sta/Elev= 22
       0    6.69     6.1    6.47     6.6    6.47     6.6    6.67     9.6    6.78
    11.5    5.71    15.3    3.98   16.69    3.35    30.1    3.35    32.5    2.15
    36.5    2.15    40.1    3.35   42.44    3.35    43.5    3.81      47    5.34
    49.3     6.8    50.1     6.8    52.3     6.8    52.3    6.55    52.8    6.55
    59.4     6.6      60     6.6
#Mann= 3 , 0 , 0
       0     .03       0     9.6     .03       0    49.3     .03       0
Levee=-1,9.6,6.78,-1,49.3,6.8,,
Bank Sta=9.6,49.3
Exp/Cntr=0.3,0.1

Type RM Length L Ch R = 1 ,57      ,50,50,50
#Sta/Elev= 22
       0    6.58     6.1    6.39     6.6    6.39     6.6    6.59     9.6    6.68
    10.8    6.09      15    4.08   16.61    3.31   30.18    3.31   32.58    2.11
   36.58    2.11   40.18    3.31   42.38    3.31    43.4    3.77      47     5.4
    49.3    6.72    50.1    6.72    52.3    6.72    52.3    6.52    52.8    6.52
    59.2    6.61      60     6.6
#Mann= 3 , 0 , 0
       0     .03       0     9.6     .03       0    49.3     .03       0
Levee=-1,9.6,6.68,-1,49.3,6.72,,
Bank Sta=9.6,49.3
Exp/Cntr=0.3,0.1

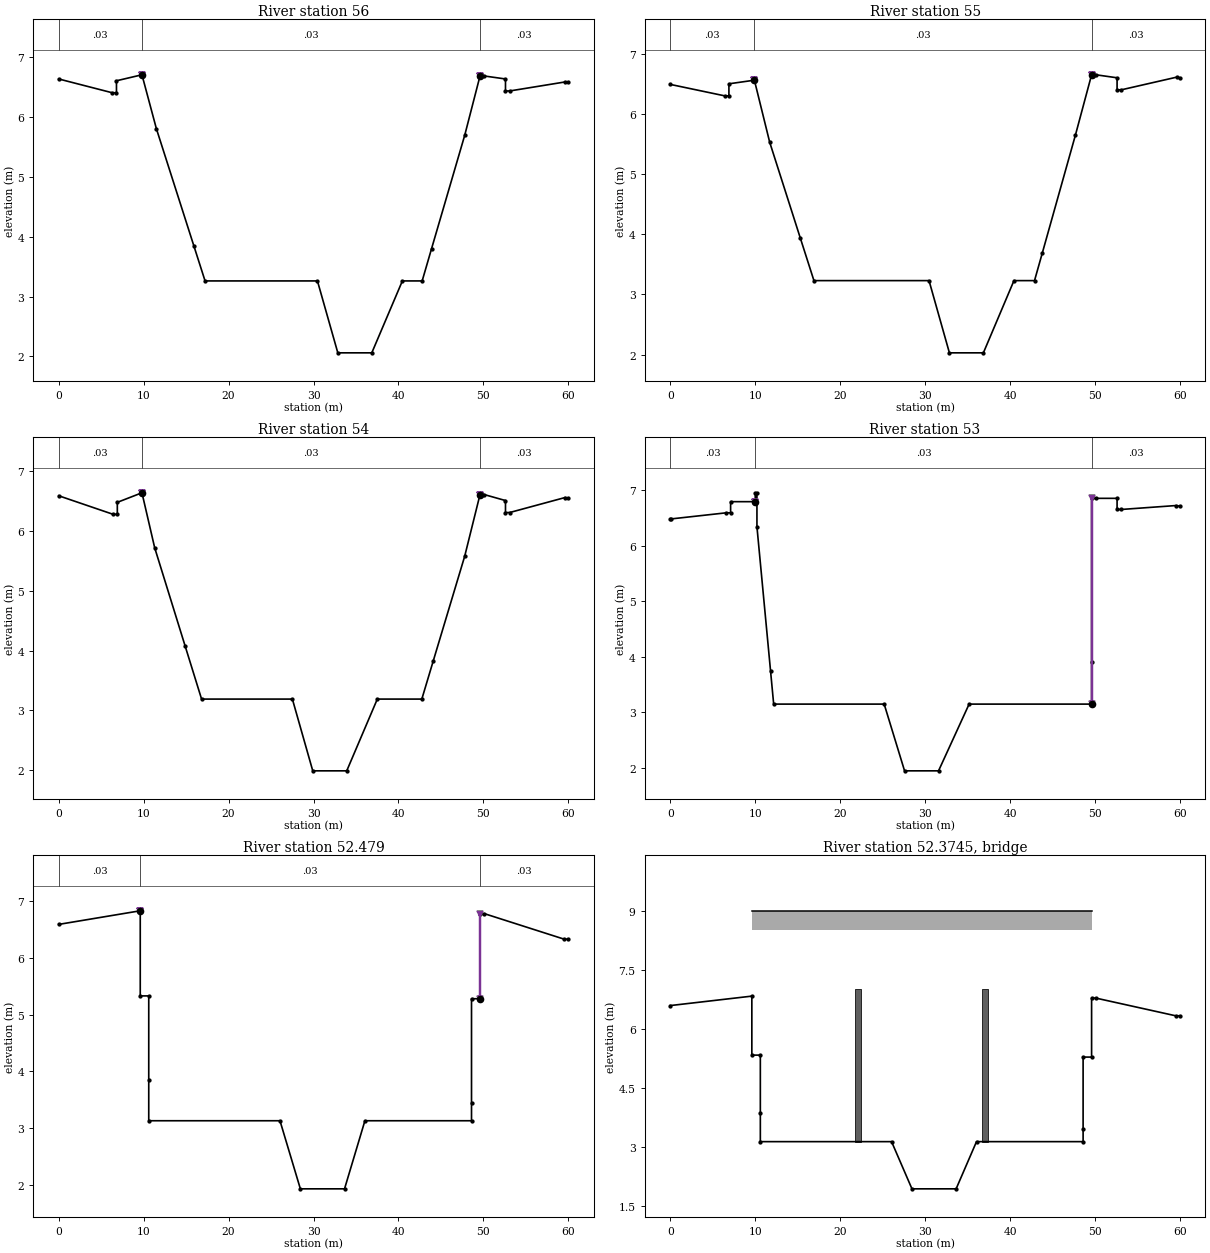
Type RM Length L Ch R = 1 ,56      ,50,50,50
#Sta/Elev= 22
       0    6.63     6.3     6.4     6.8     6.4     6.8     6.6     9.8     6.7
    11.5     5.8    15.9    3.85   17.23    3.26   30.46    3.26   32.86    2.06
   36.86    2.06   40.46    3.26   42.79    3.26    43.9     3.8    47.8    5.69
    49.6    6.68    50.1    6.68    52.6    6.63    52.6    6.43    53.1    6.43
    59.6    6.58      60    6.58
#Mann= 3 , 0 , 0
       0     .03       0     9.8     .03       0    49.6     .03       0
Levee=-1,9.8,6.7,-1,49.6,6.68,,
Bank Sta=9.8,49.6
Exp/Cntr=0.3,0.1

Type RM Length L Ch R = 1 ,55      ,50,50,50
#Sta/Elev= 22
       0    6.49     6.4     6.3     6.9     6.3     6.9     6.5     9.9    6.56
    11.7    5.53    15.3    3.94   16.91    3.23   30.46    3.23   32.86    2.03
   36.86    2.03   40.46    3.23   42.88    3.23    43.8    3.69    47.7    5.65
    49.6    6.65    50.1    6.65    52.6     6.6    52.6     6.4    53.1     6.4
    59.6    6.61      60     6.6
#Mann= 3 , 0 , 0
       0     .03       0     9.9     .03       0    49.6     .03       0
Levee=-1,9.9,6.56,-1,49.6,6.65,,
Bank Sta=9.9,49.6
Exp/Cntr=0.3,0.1

Type RM Length L Ch R = 1 ,54      ,50,50,50
#Sta/Elev= 22
       0    6.59     6.4    6.28     6.9    6.28     6.9    6.48     9.8    6.64
    11.3    5.72    14.9    4.07   16.82    3.19   27.51    3.19   29.91    1.99
   33.91    1.99   37.51    3.19   42.75    3.19    44.1    3.83    47.8    5.58
    49.6    6.61    50.1    6.61    52.6    6.51    52.6    6.31    53.1    6.31
    59.6    6.56      60    6.55
#Mann= 3 , 0 , 0
       0     .03       0     9.8     .03       0    49.6     .03       0
Levee=-1,9.8,6.64,-1,49.6,6.61,,
Bank Sta=9.8,49.6
Exp/Cntr=0.3,0.1

Type RM Length L Ch R = 1 ,53      ,2.1,2.1,2.1
#Sta/Elev= 24
       0    6.48      .1    6.48     6.6    6.59     7.1    6.59     7.1    6.79
      10    6.79      10    6.95    10.2    6.95    10.2    6.34    11.8    3.75
   12.17    3.15   25.18    3.15   27.58    1.95   31.58    1.95   35.18    3.15
    49.6    3.15    49.6     3.9    49.6    6.85    50.1    6.85    52.6    6.85
    52.6    6.65    53.1    6.65    59.5    6.72      60    6.71
#Mann= 3 , 0 , 0
       0     .03       0      10     .03       0    49.6     .03       0
Levee=-1,10,6.79,-1,49.6,6.85,,
Bank Sta=10,49.6
Exp/Cntr=0.3,0.1

Type RM Length L Ch R = 1 ,52.479  ,20.9,20.9,20.9
#Sta/Elev= 18
       0    6.59     9.6    6.83     9.6    5.33    10.6    5.33    10.6    3.85
    10.6    3.13   26.05    3.13   28.45    1.93   33.65    1.93   36.05    3.13
    48.6    3.13    48.6    3.45    48.6    5.28    49.6    5.28    49.6    6.78
    50.1    6.78    59.5    6.33      60    6.33
#Mann= 3 , 0 , 0
       0     .03       0     9.6     .03       0    49.6     .03       0
Levee=-1,9.6,6.83,-1,49.6,6.78,,
Bank Sta=9.6,49.6
Exp/Cntr=0.5,0.3

Type RM Length L Ch R = 3 ,52.3745 ,,,
BEGIN DESCRIPTION:
È­¶û±³(°³·®)
END DESCRIPTION:
Bridge Culvert--1,0,-1,-1, 0
Deck Dist Width WeirC Skew NumUp NumDn MinLoCord MaxHiCord MaxSubmerge Is_Ogee
0.1,20,1.44,0, 2, 2, , , 0.95, 0, 0,0,,
     9.6    49.6
       9       9
     8.5     8.5
     9.6    49.6
       9       9
     8.5     8.5
Pier Skew, UpSta & Num, DnSta & Num=  ,22.1, 2 ,22.1, 2 , 0 , 0 , 0 ,,
      .7      .7
       2       7
      .7      .7
       2       7
Pier Skew, UpSta & Num, DnSta & Num=  ,37, 2 ,37, 2 , 0 , 0 , 0 ,,
      .7      .7
       2       7
      .7      .7
       2       7
BR Coef=-1 , 0 , 0 ,, 0 ,,,0.8,-1,,0,
WSPro=,,,, 1 ,,,, 0 ,,,, 0 ,,,,-1 ,-1 ,-1 , 0 , 0 , 0 , 0 , 0
BC Design=,, 0 ,, 0 ,,,,,,

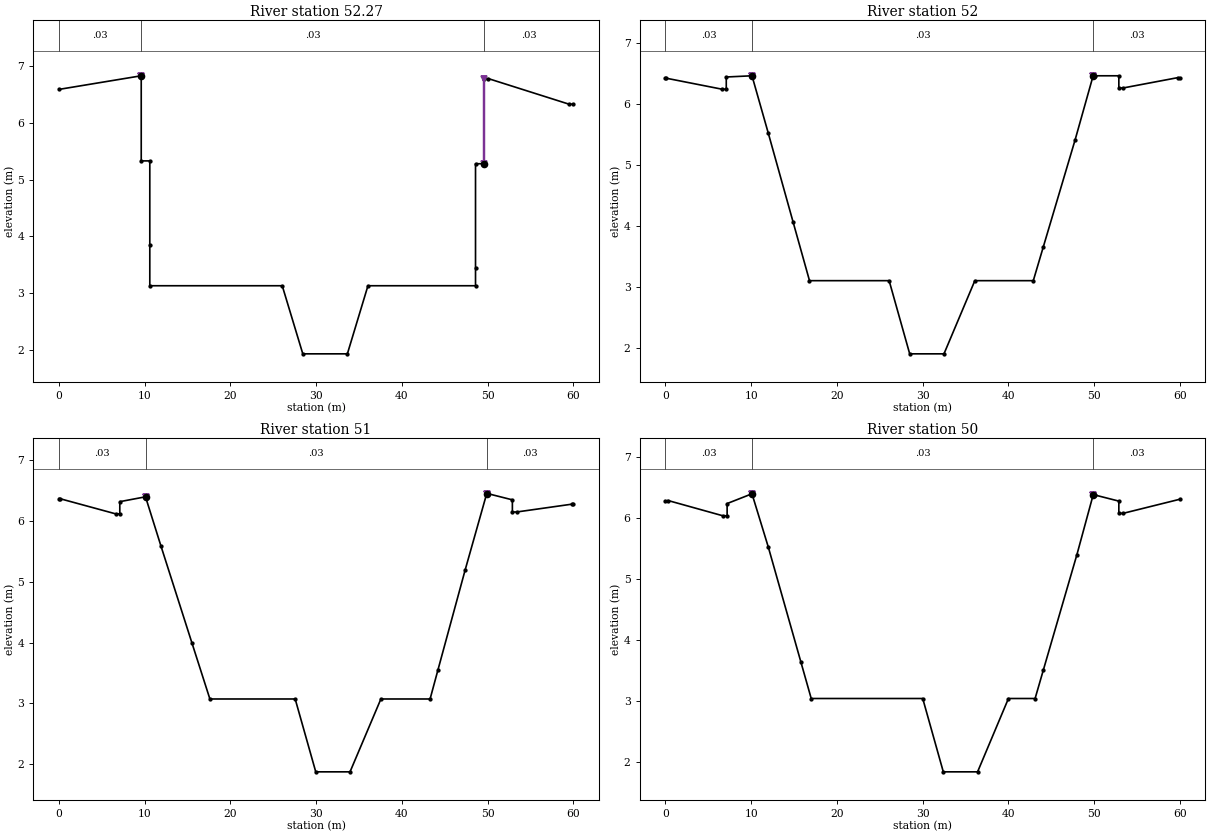
Type RM Length L Ch R = 1 ,52.27   ,27,27,27
#Sta/Elev= 18
       0    6.59     9.6    6.83     9.6    5.33    10.6    5.33    10.6    3.85
    10.6    3.13   26.05    3.13   28.45    1.93   33.65    1.93   36.05    3.13
    48.6    3.13    48.6    3.45    48.6    5.28    49.6    5.28    49.6    6.78
    50.1    6.78    59.5    6.33      60    6.33
#Mann= 3 , 0 , 0
       0     .03       0     9.6     .03       0    49.6     .03       0
Levee=-1,9.6,6.83,-1,49.6,6.78,,
Bank Sta=9.6,49.6
Exp/Cntr=0.5,0.3

Type RM Length L Ch R = 1 ,52      ,50,50,50
#Sta/Elev= 23
       0    6.43      .1    6.43     6.6    6.25     7.1    6.25     7.1    6.45
    10.1    6.47      12    5.53    14.9    4.07   16.81    3.11    26.1    3.11
    28.5    1.91    32.5    1.91    36.1    3.11   42.92    3.11    44.1    3.67
    47.8    5.42    49.9    6.47    50.1    6.47    52.9    6.47    52.9    6.27
    53.4    6.27    59.8    6.44      60    6.43
#Mann= 3 , 0 , 0
       0     .03       0    10.1     .03       0    49.9     .03       0
Levee=-1,10.1,6.47,-1,49.9,6.47,,
Bank Sta=10.1,49.9
Exp/Cntr=0.3,0.1

Type RM Length L Ch R = 1 ,51      ,50,50,50
#Sta/Elev= 23
       0    6.37      .1    6.37     6.6    6.12     7.1    6.12     7.1    6.32
    10.1     6.4    11.9    5.59    15.5       4   17.61    3.07   27.56    3.07
   29.96    1.87   33.96    1.87   37.56    3.07    43.3    3.07    44.2    3.54
    47.4     5.2    49.9    6.45    50.1    6.45    52.9    6.35    52.9    6.15
    53.4    6.15    59.9    6.28      60    6.28
#Mann= 3 , 0 , 0
       0     .03       0    10.1     .03       0    49.9     .03       0
Levee=-1,10.1,6.4,-1,49.9,6.45,,
Bank Sta=10.1,49.9
Exp/Cntr=0.3,0.1

Type RM Length L Ch R = 1 ,50      ,50,50,50
#Sta/Elev= 22
       0    6.27      .3    6.28     6.7    6.03     7.2    6.03     7.2    6.23
    10.1    6.39      12    5.52    15.8    3.64   17.01    3.04   30.02    3.04
   32.42    1.84   36.42    1.84   40.02    3.04   43.13    3.04    44.1    3.51
      48    5.39    49.9    6.37    50.1    6.37    52.9    6.27    52.9    6.07
    53.4    6.07      60     6.3
#Mann= 3 , 0 , 0
       0     .03       0    10.1     .03       0    49.9     .03       0
Levee=-1,10.1,6.39,-1,49.9,6.37,,
Bank Sta=10.1,49.9
Exp/Cntr=0.3,0.1