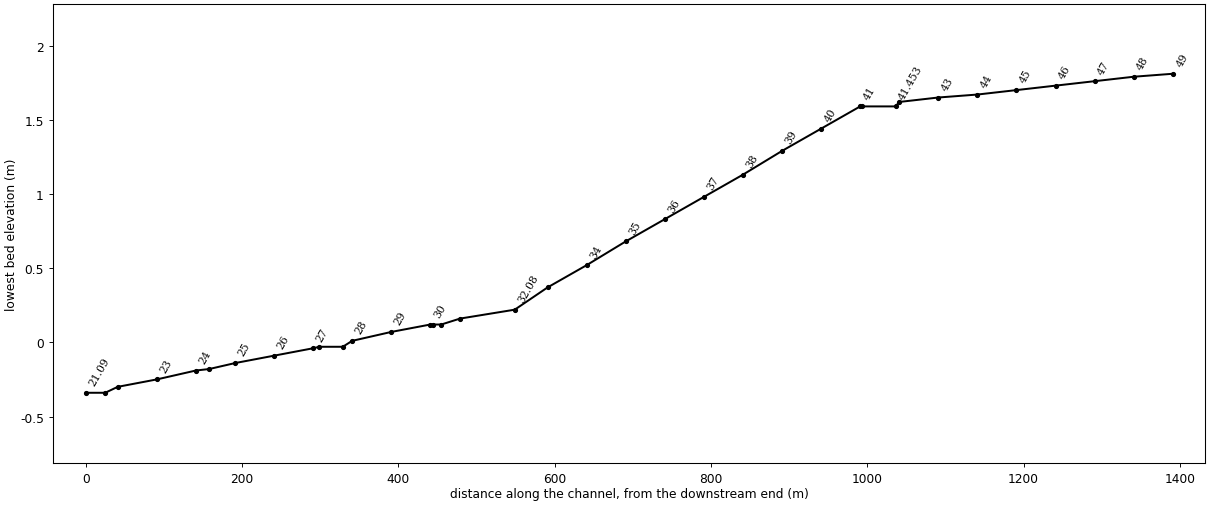
HEC-RAS study hj.prj: Hwajung_plan

--- hj.g01 (geometry) --- (continued)

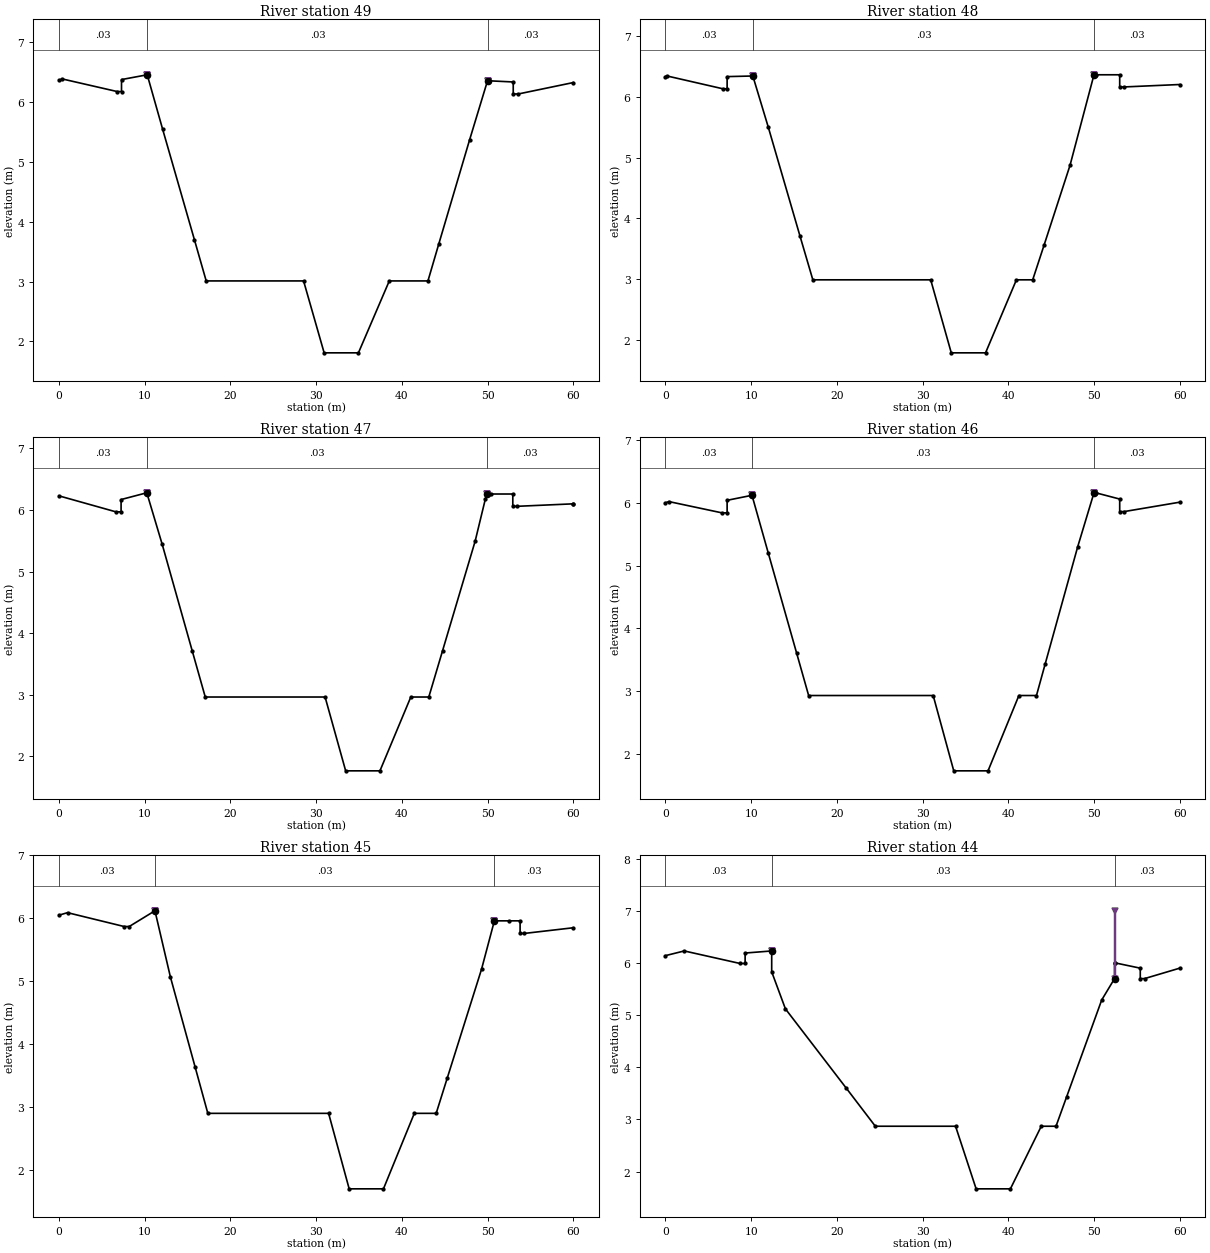
Type RM Length L Ch R = 1 ,49      ,50,50,50
#Sta/Elev= 22
       0    6.36      .4    6.38     6.8    6.17     7.3    6.17     7.3    6.37
    10.3    6.45    12.1    5.54    15.8     3.7   17.18    3.01   28.54    3.01
   30.94    1.81   34.94    1.81   38.54    3.01   43.05    3.01    44.3    3.62
    47.9    5.36      50    6.35    50.1    6.35      53    6.33      53    6.13
    53.6    6.13      60    6.32
#Mann= 3 , 0 , 0
       0     .03       0    10.3     .03       0      50     .03       0
Levee=-1,10.3,6.45,-1,50,6.35,,
Bank Sta=10.3,50
Exp/Cntr=0.3,0.1

Type RM Length L Ch R = 1 ,48      ,50,50,50
#Sta/Elev= 22
       0    6.33      .2    6.34     6.7    6.13     7.2    6.13     7.2    6.33
    10.2    6.34      12     5.5    15.7    3.71    17.2    2.99   30.95    2.99
   33.35    1.79   37.35    1.79   40.95    2.99   42.85    2.99    44.2    3.57
    47.2    4.87      50    6.36    50.2    6.36      53    6.36      53    6.16
    53.5    6.16      60     6.2
#Mann= 3 , 0 , 0
       0     .03       0    10.2     .03       0      50     .03       0
Levee=-1,10.2,6.34,-1,50,6.36,,
Bank Sta=10.2,50
Exp/Cntr=0.3,0.1

Type RM Length L Ch R = 1 ,47      ,50,50,50
#Sta/Elev= 23
       0    6.23    6.65    5.97    7.25    5.97    7.25    6.17   10.25    6.28
   12.05    5.44   15.55    3.71   17.07    2.96   31.05    2.96   33.45    1.76
   37.45    1.76   41.05    2.96   43.15    2.96   44.75    3.71   48.55    5.49
   49.75    6.18   49.95    6.26   50.45    6.26   52.95    6.26   52.95    6.06
   53.45    6.06   59.95     6.1      60     6.1
#Mann= 3 , 0 , 0
       0     .03       0   10.25     .03       0   49.95     .03       0
Levee=-1,10.25,6.28,-1,49.95,6.26,,
Bank Sta=10.25,49.95
Exp/Cntr=0.3,0.1

Type RM Length L Ch R = 1 ,46      ,50,50,50
#Sta/Elev= 22
       0       6      .4    6.02     6.6    5.84     7.2    5.84     7.2    6.04
    10.1    6.12      12     5.2    15.3    3.61   16.71    2.93   31.24    2.93
   33.64    1.73   37.64    1.73   41.24    2.93   43.29    2.93    44.3    3.43
    48.1     5.3      50    6.16    50.2    6.16      53    6.06      53    5.86
    53.5    5.86      60    6.01
#Mann= 3 , 0 , 0
       0     .03       0    10.1     .03       0      50     .03       0
Levee=-1,10.1,6.12,-1,50,6.16,,
Bank Sta=10.1,50
Exp/Cntr=0.3,0.1

Type RM Length L Ch R = 1 ,45      ,50,50,50
#Sta/Elev= 21
       0    6.05       1    6.09     7.6    5.87     8.2    5.87    11.2    6.12
      13    5.07    15.9    3.63   17.37     2.9   31.46     2.9   33.86     1.7
   37.86     1.7   41.46     2.9   44.01     2.9    45.3    3.46    49.3    5.19
    50.8    5.96    52.5    5.96    53.8    5.96    53.8    5.76    54.3    5.76
      60    5.85
#Mann= 3 , 0 , 0
       0     .03       0    11.2     .03       0    50.8     .03       0
Levee=-1,11.2,6.12,-1,50.8,5.96,,
Bank Sta=11.2,50.8
Exp/Cntr=0.3,0.1

Type RM Length L Ch R = 1 ,44      ,50,50,50
#Sta/Elev= 24
       0    6.14     2.2    6.23     8.7    5.99     9.3    5.99     9.3    6.19
    12.4    6.23    12.4    5.83      14    5.12    21.1     3.6   24.49    2.87
   33.85    2.87   36.25    1.67   40.25    1.67   43.85    2.87   45.57    2.87
    46.8    3.43    50.9    5.29    52.4     5.7    52.4       6    52.5       6
    55.4     5.9    55.4     5.7    55.9     5.7      60     5.9
#Mann= 3 , 0 , 0
       0     .03       0    12.4     .03       0    52.4     .03       0
Levee=-1,12.4,6.23,-1,52.4,7,,
Bank Sta=12.4,52.4
Exp/Cntr=0.3,0.1

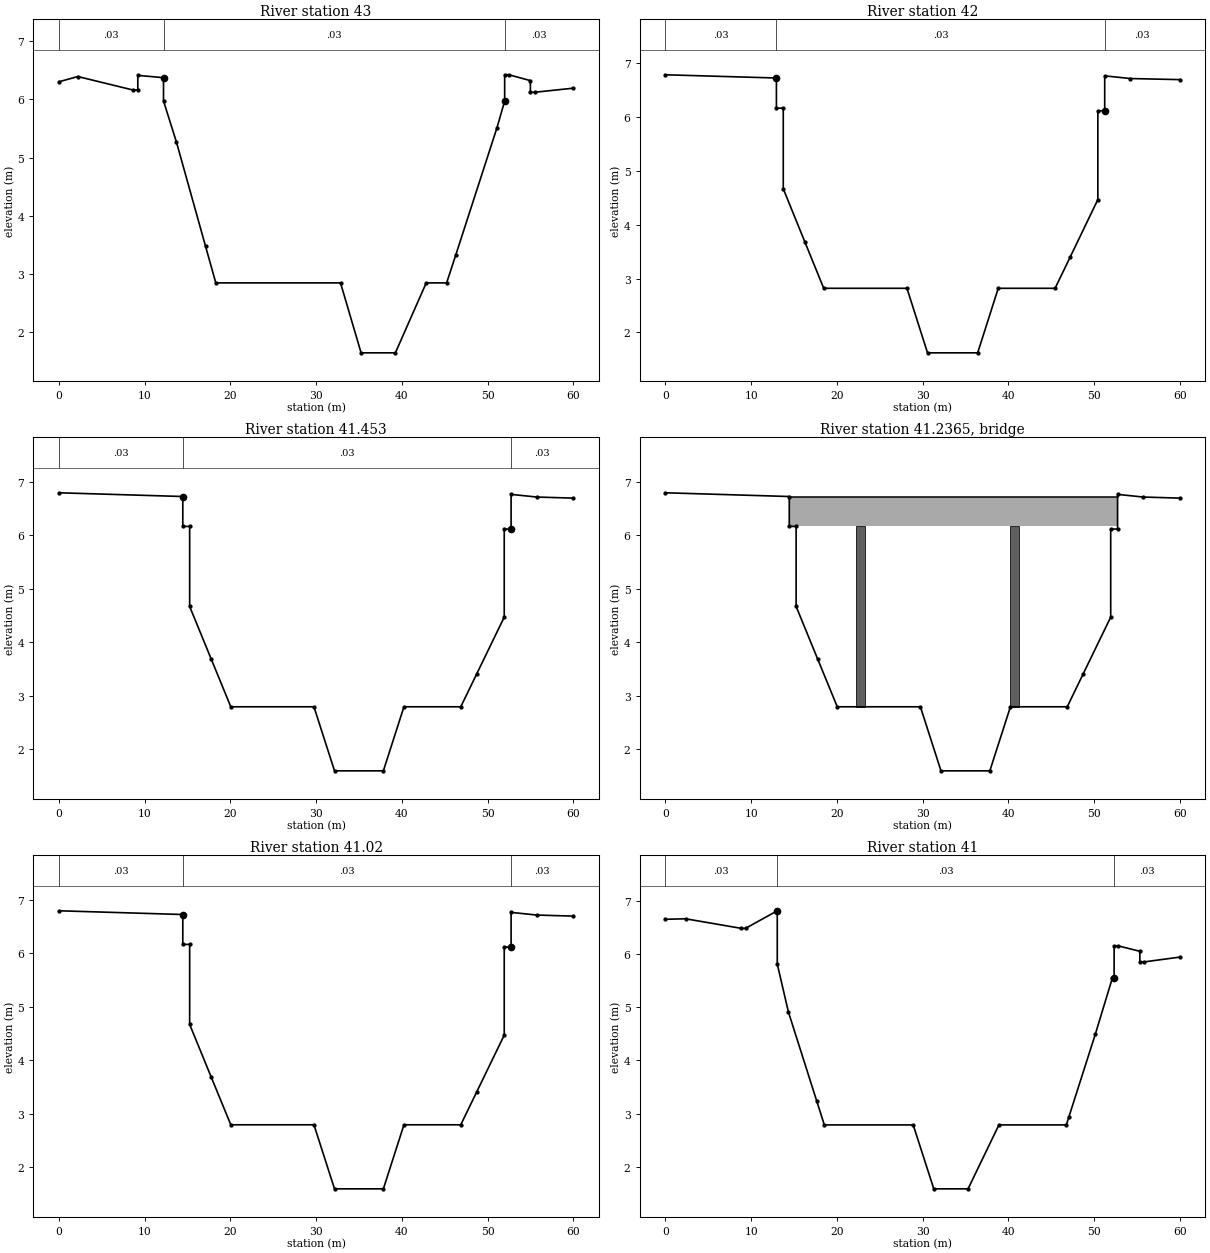
Type RM Length L Ch R = 1 ,43      ,50,50,50
#Sta/Elev= 24
       0     6.3     2.2    6.39     8.6    6.16     9.2    6.16     9.2    6.41
    12.2    6.37    12.2    5.97    13.7    5.27    17.1    3.48    18.3    2.85
   32.85    2.85   35.25    1.65   39.25    1.65   42.85    2.85   45.23    2.85
    46.3    3.33    51.1    5.51      52    5.97      52    6.42    52.5    6.42
      55    6.32      55    6.12    55.5    6.12      60    6.19
#Mann= 3 , 0 , 0
       0     .03       0    12.2     .03       0      52     .03       0
Bank Sta=12.2,52
Exp/Cntr=0.3,0.1

Type RM Length L Ch R = 1 ,42      ,4.7,4.7,4.7
#Sta/Elev= 19
       0    6.79   12.95    6.73   12.95    6.17   13.75    6.17   13.75    4.67
   16.25    3.69   18.47    2.82   28.18    2.82   30.58    1.62   36.43    1.62
   38.83    2.82   45.46    2.82   47.25    3.41   50.45    4.47   50.45    6.12
   51.25    6.12   51.25    6.77   54.25    6.72      60     6.7
#Mann= 3 , 0 , 0
       0     .03       0   12.95     .03       0   51.25     .03       0
Bank Sta=12.95,51.25
Exp/Cntr=0.3,0.1

Type RM Length L Ch R = 1 ,41.453  ,43.3,43.3,43.3
#Sta/Elev= 19
       0     6.8   14.45    6.73   14.45    6.17   15.25    6.17   15.25    4.67
   17.75    3.69   20.05    2.79   29.75    2.79   32.15    1.59   37.85    1.59
   40.25    2.79   46.88    2.79   48.75    3.41   51.95    4.47   51.95    6.12
   52.75    6.12   52.75    6.77   55.75    6.72      60     6.7
#Mann= 3 , 0 , 0
       0     .03       0   14.45     .03       0   52.75     .03       0
Bank Sta=14.45,52.75
Exp/Cntr=0.5,0.3

Type RM Length L Ch R = 3 ,41.2365 ,,,
BEGIN DESCRIPTION:
È­Á¤1±³
END DESCRIPTION:
Bridge Culvert--1,0,-1,-1, 0
Deck Dist Width WeirC Skew NumUp NumDn MinLoCord MaxHiCord MaxSubmerge Is_Ogee
0.1,43,1.44,0, 2, 2, , , 0.95, 0, 0,0,,
   14.45   52.75
    6.73    6.73
    6.17    6.17
   14.45   52.75
    6.73    6.73
    6.17    6.17
Pier Skew, UpSta & Num, DnSta & Num=  ,22.75, 2 ,22.75, 2 , 0 , 0 , 0 ,,
       1       1
       2       7
       1       1
       2       7
Pier Skew, UpSta & Num, DnSta & Num=  ,40.75, 2 ,40.75, 2 , 0 , 0 , 0 ,,
       1       1
       2       7
       1       1
       2       7
BR Coef=-1 , 0 , 0 ,, 0 ,,,0.8,-1,,0,
WSPro=,,,, 1 ,,,, 0 ,,,, 0 ,,,,-1 ,-1 ,-1 , 0 , 0 , 0 , 0 , 0
BC Design=,, 0 ,, 0 ,,,,,,

Type RM Length L Ch R = 1 ,41.02   ,2,2,2
#Sta/Elev= 19
       0     6.8   14.45    6.73   14.45    6.17   15.25    6.17   15.25    4.67
   17.75    3.69   20.05    2.79   29.75    2.79   32.15    1.59   37.85    1.59
   40.25    2.79   46.88    2.79   48.75    3.41   51.95    4.47   51.95    6.12
   52.75    6.12   52.75    6.77   55.75    6.72      60     6.7
#Mann= 3 , 0 , 0
       0     .03       0   14.45     .03       0   52.75     .03       0
Bank Sta=14.45,52.75
Exp/Cntr=0.5,0.3

Type RM Length L Ch R = 1 ,41      ,50,50,50
#Sta/Elev= 24
       0    6.65    2.35    6.66    8.85    6.48    9.35    6.48   13.05    6.81
   13.05    5.81   14.35    4.91   17.65    3.24   18.54    2.79   28.91    2.79
   31.31    1.59   35.31    1.59   38.91    2.79   46.77    2.79   47.05    2.93
   50.15    4.49   52.15    5.55   52.35    5.55   52.35    6.15   52.85    6.15
   55.35    6.05   55.35    5.85   55.85    5.85      60    5.94
#Mann= 3 , 0 , 0
       0     .03       0   13.05     .03       0   52.35     .03       0
Bank Sta=13.05,52.35
Exp/Cntr=0.3,0.1

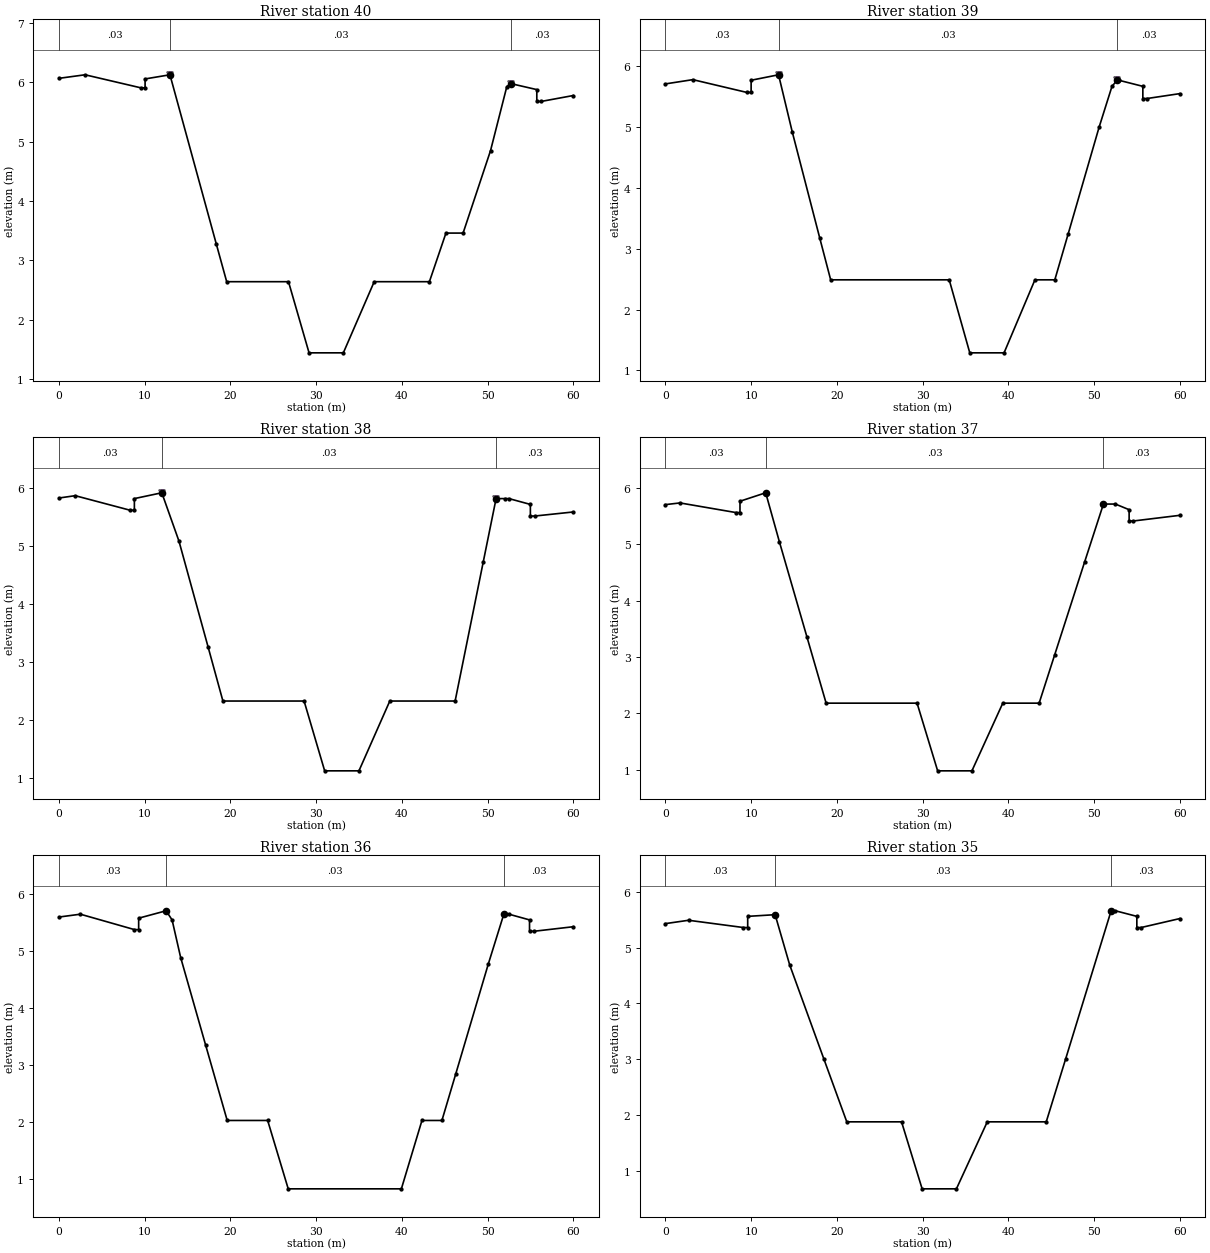
Type RM Length L Ch R = 1 ,40      ,50,50,50
#Sta/Elev= 22
       0    6.07    3.05    6.13    9.55    5.91   10.05    5.91   10.05    6.06
   12.95    6.13   18.35    3.28   19.57    2.64   26.78    2.64   29.18    1.44
   33.18    1.44   36.78    2.64   43.22    2.64   45.15    3.46   47.15    3.46
   50.35    4.85   52.25    5.93   52.75    5.98   55.75    5.88   55.75    5.68
   56.25    5.68      60    5.78
#Mann= 3 , 0 , 0
       0     .03       0   12.95     .03       0   52.75     .03       0
Levee=-1,12.95,6.13,-1,52.75,5.98,,
Bank Sta=12.95,52.75
Exp/Cntr=0.3,0.1

Type RM Length L Ch R = 1 ,39      ,50,50,50
#Sta/Elev= 23
       0    5.71     3.2    5.78     9.5    5.57      10    5.57      10    5.77
    13.2    5.86    14.8    4.92      18    3.18   19.28    2.49   33.11    2.49
   35.51    1.29   39.51    1.29   43.11    2.49   45.43    2.49      47    3.25
    50.6       5    52.1    5.67    52.7    5.77    52.9    5.77    55.7    5.67
    55.7    5.47    56.2    5.47      60    5.55
#Mann= 3 , 0 , 0
       0     .03       0    13.2     .03       0    52.7     .03       0
Levee=-1,13.2,5.86,-1,52.7,5.77,,
Bank Sta=13.2,52.7
Exp/Cntr=0.3,0.1

Type RM Length L Ch R = 1 ,38      ,50,50,50
#Sta/Elev= 22
       0    5.82     1.9    5.86     8.3    5.61     8.8    5.61     8.8    5.81
      12    5.91      14    5.08    17.4    3.26   19.13    2.33    28.6    2.33
      31    1.13      35    1.13    38.6    2.33   46.22    2.33    49.5    4.72
      51    5.81      52    5.81    52.5    5.81      55    5.71      55    5.51
    55.5    5.51      60    5.58
#Mann= 3 , 0 , 0
       0     .03       0      12     .03       0      51     .03       0
Levee=-1,12,5.91,-1,51,5.81,,
Bank Sta=12,51
Exp/Cntr=0.3,0.1

Type RM Length L Ch R = 1 ,37      ,50,50,50
#Sta/Elev= 22
       0     5.7     1.7    5.73     8.2    5.56     8.7    5.56     8.7    5.76
    11.7    5.91    13.3    5.04    16.5    3.36   18.75    2.18   29.36    2.18
   31.76     .98   35.76     .98   39.36    2.18    43.6    2.18    45.4    3.03
    48.9    4.68    51.1    5.71    52.5    5.71    54.1    5.61    54.1    5.41
    54.6    5.41      60    5.51
#Mann= 3 , 0 , 0
       0     .03       0    11.7     .03       0    51.1     .03       0
Bank Sta=11.7,51.1
Exp/Cntr=0.3,0.1

Type RM Length L Ch R = 1 ,36      ,50,50,50
#Sta/Elev= 23
       0     5.6     2.5    5.65     8.8    5.38     9.3    5.38     9.3    5.58
    12.5    5.71    13.2    5.55    14.2    4.89    17.1    3.36   19.63    2.03
   24.35    2.03   26.75     .83   39.95     .83   42.35    2.03   44.68    2.03
    46.3    2.85    50.1    4.78    51.9    5.65    52.5    5.65    54.9    5.55
    54.9    5.35    55.4    5.35      60    5.43
#Mann= 3 , 0 , 0
       0     .03       0    12.5     .03       0    51.9     .03       0
Bank Sta=12.5,51.9
Exp/Cntr=0.3,0.1

Type RM Length L Ch R = 1 ,35      ,50,50,50
#Sta/Elev= 21
       0    5.43     2.7    5.49     9.1    5.36     9.6    5.36     9.6    5.56
    12.8    5.59    14.5    4.69    18.5       3   21.16    1.88   27.55    1.88
   29.95     .68   33.95     .68   37.55    1.88   44.43    1.88    46.7    3.01
      52    5.66    52.5    5.66      55    5.56      55    5.36    55.5    5.36
      60    5.52
#Mann= 3 , 0 , 0
       0     .03       0    12.8     .03       0      52     .03       0
Bank Sta=12.8,52
Exp/Cntr=0.3,0.1

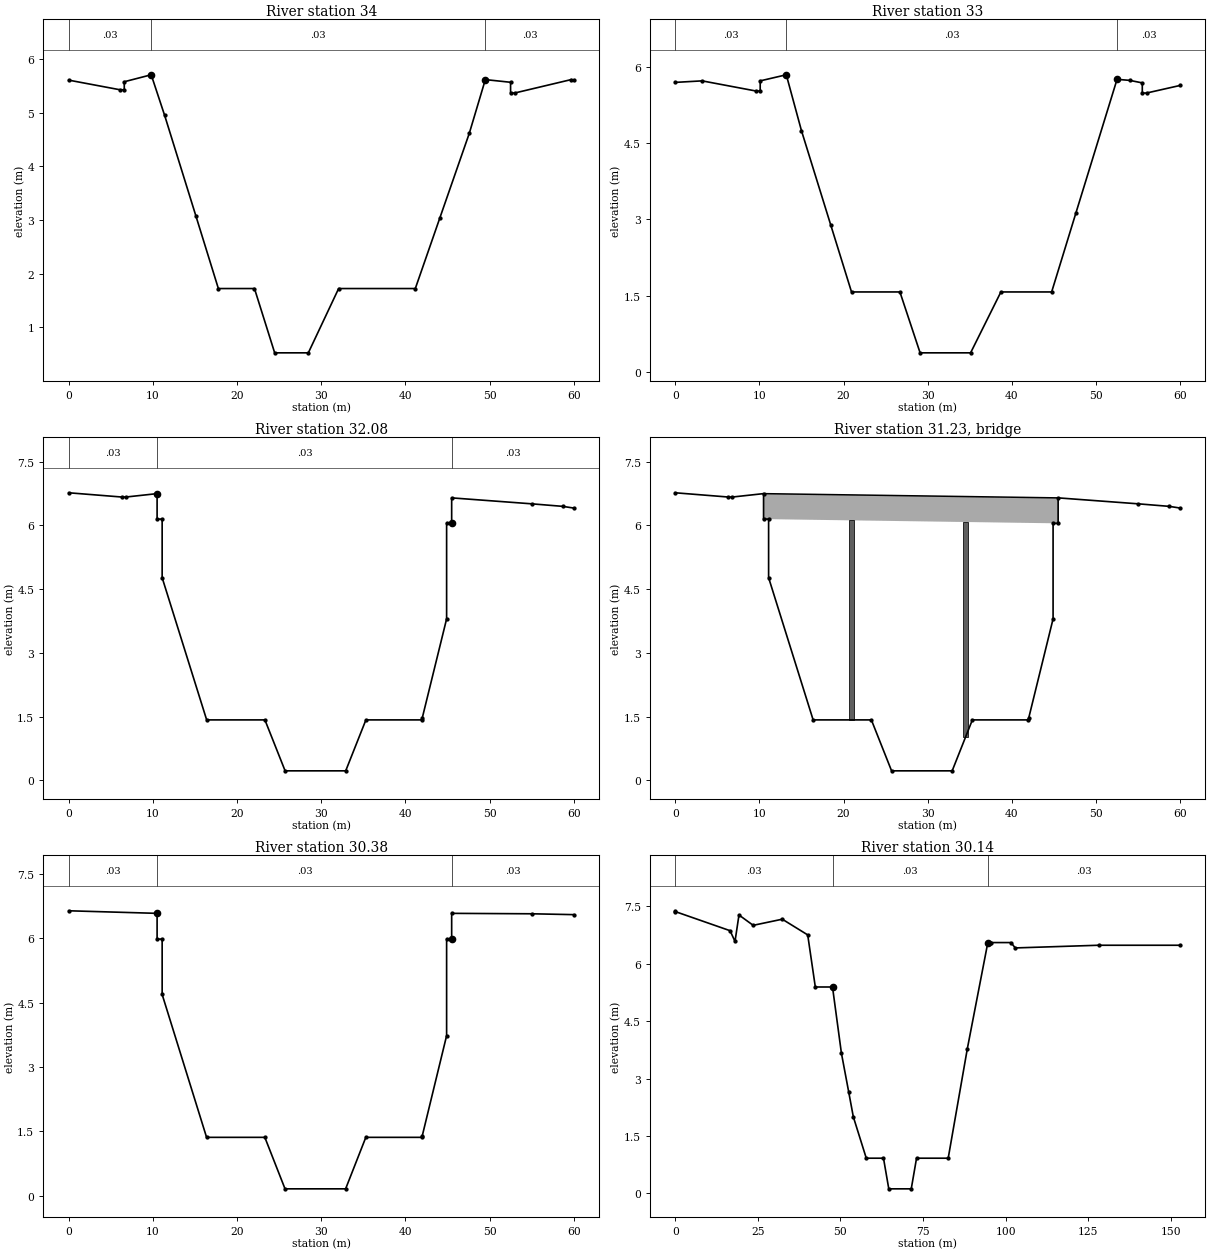
Type RM Length L Ch R = 1 ,34      ,50,50,50
#Sta/Elev= 21
       0    5.61     6.1    5.43     6.6    5.43     6.6    5.58     9.8    5.71
    11.4    4.95    15.1    3.08   17.78    1.72   22.07    1.72   24.47     .52
   28.47     .52   32.07    1.72   41.18    1.72    44.1    3.04    47.6    4.62
    49.5    5.62    52.5    5.57    52.5    5.37      53    5.37    59.7    5.62
      60    5.61
#Mann= 3 , 0 , 0
       0     .03       0     9.8     .03       0    49.5     .03       0
Bank Sta=9.8,49.5
Exp/Cntr=0.3,0.1

Type RM Length L Ch R = 1 ,33      ,42,42,42
#Sta/Elev= 21
       0     5.7     3.2    5.73     9.6    5.53    10.1    5.53    10.1    5.73
    13.2    5.85      15    4.75    18.5    2.88   20.95    1.57    26.7    1.57
    29.1     .37    35.1     .37    38.7    1.57   44.73    1.57    47.6    3.12
    52.5    5.76      54    5.74    55.5    5.69    55.5    5.49      56    5.49
      60    5.64
#Mann= 3 , 0 , 0
       0     .03       0    13.2     .03       0    52.5     .03       0
Bank Sta=13.2,52.5
Exp/Cntr=0.3,0.1

Type RM Length L Ch R = 1 ,32.08   ,70,70,70
#Sta/Elev= 21
       0    6.77     6.3    6.67     6.8    6.67    10.5    6.75    10.5    6.15
    11.1    6.15    11.1    4.77   16.39    1.42   23.31    1.42   25.71     .22
   32.91     .22   35.31    1.42   41.95    1.42      42    1.46    44.9     3.8
    44.9    6.05    45.5    6.05    45.5    6.65      55    6.51    58.7    6.45
      60    6.41
#Mann= 3 , 0 , 0
       0     .03       0    10.5     .03       0    45.5     .03       0
Bank Sta=10.5,45.5
Exp/Cntr=0.3,0.1

Type RM Length L Ch R = 3 ,31.23   ,,,
BEGIN DESCRIPTION:
È­Á¤±³
END DESCRIPTION:
Bridge Culvert--1,0,-1,-1, 0
Deck Dist Width WeirC Skew NumUp NumDn MinLoCord MaxHiCord MaxSubmerge Is_Ogee
0.1,69,1.44,0, 2, 2, , , 0.95, 0, 0,0,,
    10.5    45.5
    6.75    6.65
    6.15    6.05
    10.5    45.5
    6.58    6.58
    5.98    5.98
Pier Skew, UpSta & Num, DnSta & Num=  ,21, 2 ,21, 2 , 0 , 0 , 0 ,,
      .6      .6
       0       7
      .6      .6
       0       7
Pier Skew, UpSta & Num, DnSta & Num=  ,34.5, 2 ,34.5, 2 , 0 , 0 , 0 ,,
      .6      .6
       0       7
      .6      .6
       0       7
BR Coef=-1 , 0 , 0 ,, 0 ,,,0.8,-1,,0,
WSPro=,,,, 1 ,,,, 0 ,,,, 0 ,,,,-1 ,-1 ,-1 , 0 , 0 , 0 , 0 , 0
BC Design=,, 0 ,, 0 ,,,,,,

Type RM Length L Ch R = 1 ,30.38   ,24,24,24
#Sta/Elev= 18
       0    6.64    10.5    6.58    10.5    5.98    11.1    5.98    11.1    4.69
   16.38    1.36    23.3    1.36    25.7     .16    32.9     .16    35.3    1.36
   41.96    1.36      42    1.39    44.9    3.73    44.9    5.98    45.5    5.98
    45.5    6.58      55    6.57      60    6.55
#Mann= 3 , 0 , 0
       0     .03       0    10.5     .03       0    45.5     .03       0
Bank Sta=10.5,45.5
Exp/Cntr=0.5,0.3

Type RM Length L Ch R = 1 ,30.14   ,11,11,11
#Sta/Elev= 26
       0    7.38       0    7.36    16.6    6.86    18.1    6.58    19.3    7.27
    23.6       7    32.4    7.16    40.1    6.75    42.4    5.39    47.6    5.39
    50.3    3.66    52.5    2.65    53.9       2   57.82     .92   63.03     .92
   64.63     .12   71.43     .12   73.03     .92   82.61     .92    88.4    3.78
    94.6    6.55    95.6    6.55   101.6    6.55   102.9    6.41   128.1    6.48
   152.8    6.48
#Mann= 3 , 0 , 0
       0     .03       0    47.6     .03       0    94.6     .03       0
Bank Sta=47.6,94.6
Exp/Cntr=0.5,0.3

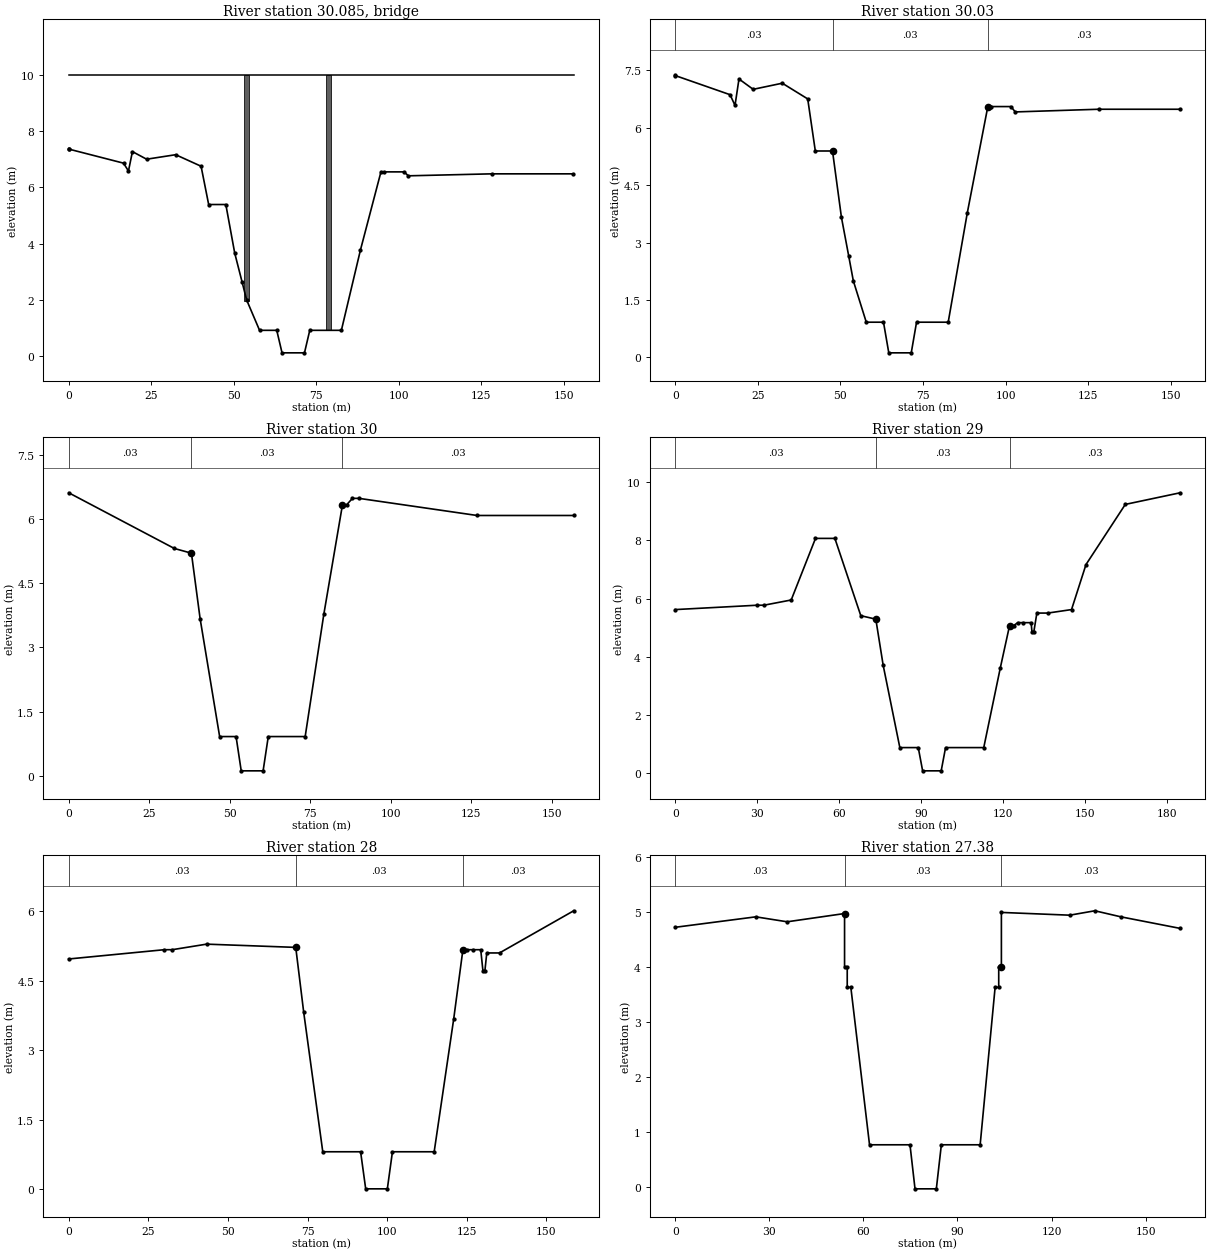
Type RM Length L Ch R = 3 ,30.085  ,,,
BEGIN DESCRIPTION:
ÁöÇÏÃ¶±³·®
END DESCRIPTION:
Bridge Culvert--1,0,-1,-1, 0
Deck Dist Width WeirC Skew NumUp NumDn MinLoCord MaxHiCord MaxSubmerge Is_Ogee
0.1,10,1.44,0, 2, 2, , , 0.95, 0, 0,0,,
       0     153
      10      10
      10      10
       0     153
      10      10
      10      10
Pier Skew, UpSta & Num, DnSta & Num=  ,54, 2 ,54, 2 , 0 , 0 , 0 ,,
     1.5     1.5
       0      10
     1.5     1.5
       0      10
Pier Skew, UpSta & Num, DnSta & Num=  ,78.6, 2 ,78.6, 2 , 0 , 0 , 0 ,,
     1.5     1.5
       0      10
     1.5     1.5
       0      10
BR Coef=-1 , 0 , 0 ,, 0 ,,,0.8,-1,,0,
WSPro=,,,, 1 ,,,, 0 ,,,, 0 ,,,,-1 ,-1 ,-1 , 0 , 0 , 0 , 0 , 0
BC Design=,, 0 ,, 0 ,,,,,,

Type RM Length L Ch R = 1 ,30.03   ,3,3,3
#Sta/Elev= 26
       0    7.38       0    7.36    16.6    6.86    18.1    6.58    19.3    7.27
    23.6       7    32.4    7.16    40.1    6.75    42.4    5.39    47.6    5.39
    50.3    3.66    52.5    2.65    53.9       2   57.82     .92   63.03     .92
   64.63     .12   71.43     .12   73.03     .92   82.61     .92    88.4    3.78
    94.6    6.55    95.6    6.55   101.6    6.55   102.9    6.41   128.1    6.48
   152.8    6.48
#Mann= 3 , 0 , 0
       0     .03       0    47.6     .03       0    94.6     .03       0
Bank Sta=47.6,94.6
Exp/Cntr=0.5,0.3

Type RM Length L Ch R = 1 ,30      ,50,50,50
#Sta/Elev= 17
       0    6.61    32.8    5.31    38.1     5.2    40.8    3.67   46.86     .92
   51.96     .92   53.56     .12   60.36     .12   61.96     .92   73.42     .92
    79.2    3.77      85    6.33    86.3    6.33    88.1    6.48    90.1    6.48
   126.8    6.08   156.8    6.08
#Mann= 3 , 0 , 0
       0     .03       0    38.1     .03       0      85     .03       0
Bank Sta=38.1,85
Exp/Cntr=0.3,0.1

Type RM Length L Ch R = 1 ,29      ,50,50,50
#Sta/Elev= 29
       0    5.62      30    5.77    32.5    5.77    42.5    5.95    51.4    8.07
    58.5    8.07      68    5.41    73.5    5.29    76.2     3.7    82.3     .87
   89.05     .87   90.65     .07   97.45     .07   99.05     .87  113.04     .87
   119.1    3.61   122.5    5.07     124    5.07   125.5    5.17   127.5    5.17
   130.4    5.17   130.7    4.86   131.4    4.86   132.5     5.5   136.5     5.5
   145.2    5.62   150.5    7.17   164.9    9.24     185    9.64
#Mann= 3 , 0 , 0
       0     .03       0    73.5     .03       0   122.5     .03       0
Bank Sta=73.5,122.5
Exp/Cntr=0.3,0.1

Type RM Length L Ch R = 1 ,28      ,12,12,12
#Sta/Elev= 22
       0    4.97      30    5.17    32.5    5.17    43.3    5.29    71.3    5.22
    73.8    3.82   79.79     .81   91.67     .81   93.27     .01  100.07     .01
  101.67     .81  114.78     .81   120.9    3.67   123.8    5.17     125    5.17
     127    5.17   129.4    5.17   130.1    4.71   130.7    4.71   131.3     5.1
   135.3     5.1   158.6    6.01
#Mann= 3 , 0 , 0
       0     .03       0    71.3     .03       0   123.8     .03       0
Bank Sta=71.3,123.8
Exp/Cntr=0.3,0.1

Type RM Length L Ch R = 1 ,27.38   ,30,30,30
#Sta/Elev= 23
       0    4.72    25.7    4.91    35.7    4.82      54    4.97      54       4
   54.85       4   54.85    3.63      56    3.63   61.96     .77   74.86     .77
   76.46    -.03   83.26    -.03   84.86     .77   97.23     .77     102    3.63
  103.15    3.63  103.15       4     104       4     104    4.99   125.8    4.94
   133.8    5.02   142.1    4.91     161     4.7
#Mann= 3 , 0 , 0
       0     .03       0      54     .03       0     104     .03       0
Bank Sta=54,104
Exp/Cntr=0.5,0.3

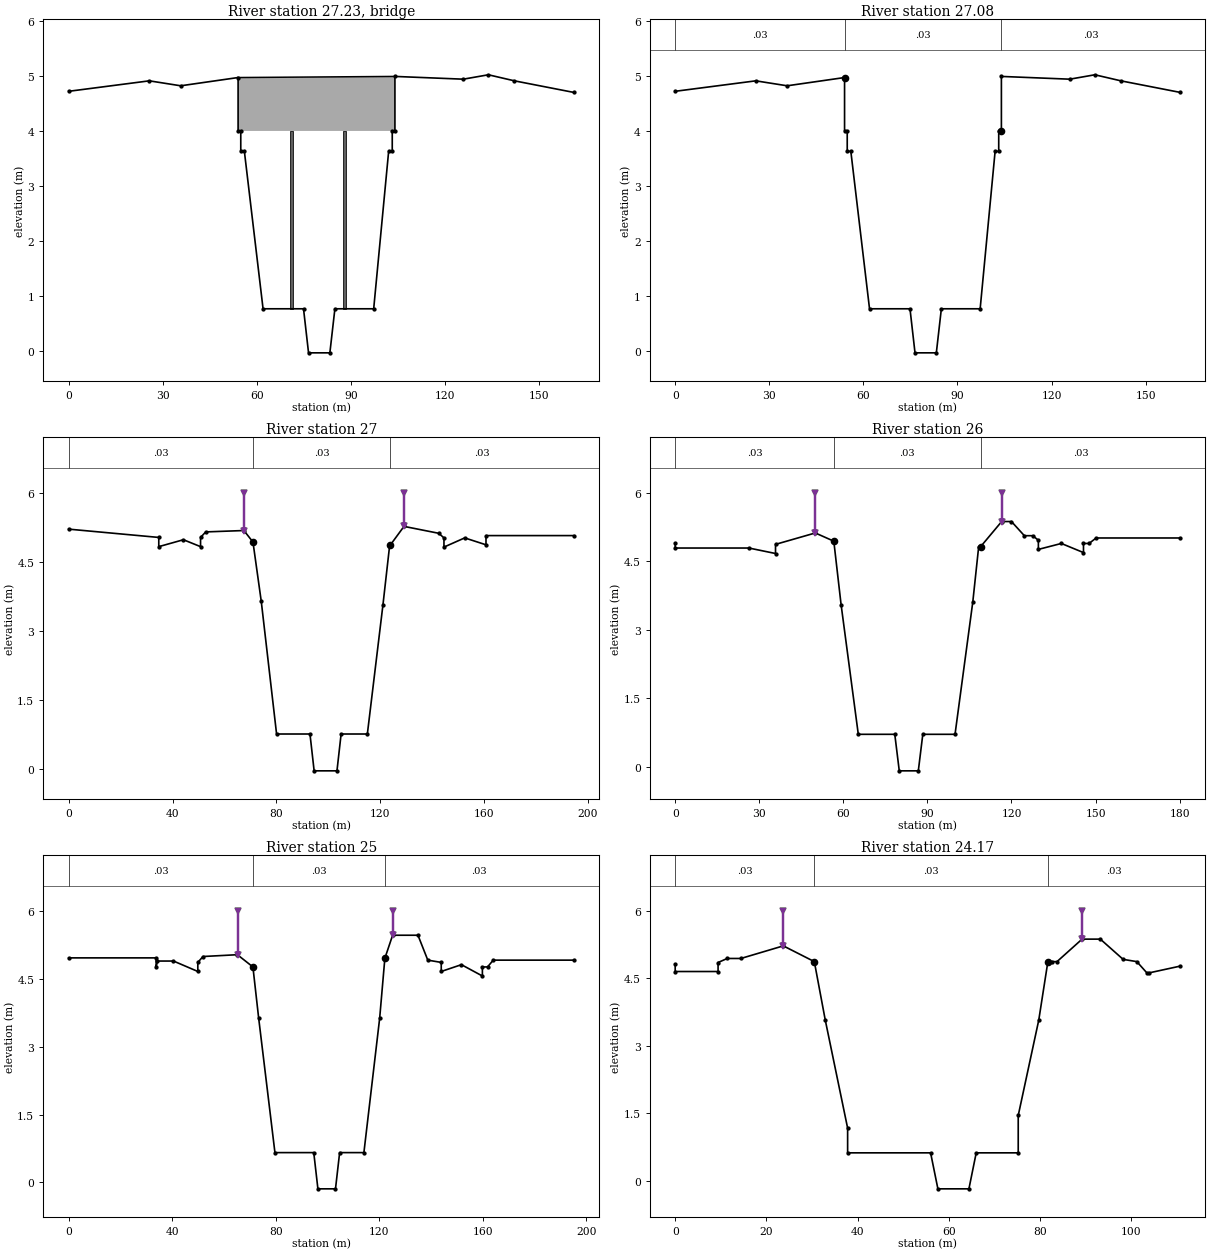
Type RM Length L Ch R = 3 ,27.23   ,,,
BEGIN DESCRIPTION:
È­Á¤11±³(È¾´Ü¼öÁ¤)
END DESCRIPTION:
Bridge Culvert--1,0,-1,-1, 0
Deck Dist Width WeirC Skew NumUp NumDn MinLoCord MaxHiCord MaxSubmerge Is_Ogee
0.1,29,1.44,0, 2, 2, , , 0.95, 0, 0,0,,
      54     104
    4.97    4.99
       4       4
      54     104
    4.97    4.99
       4       4
Pier Skew, UpSta & Num, DnSta & Num=  ,71, 2 ,71, 2 , 0 , 0 , 0 ,,
       1       1
       0       5
       1       1
       0       5
Pier Skew, UpSta & Num, DnSta & Num=  ,88, 2 ,88, 2 , 0 , 0 , 0 ,,
       1       1
       0       5
       1       1
       0       5
BR Coef=-1 , 0 , 0 ,, 0 ,,,0.8,-1,,0,
WSPro=,,,, 1 ,,,, 0 ,,,, 0 ,,,,-1 ,-1 ,-1 , 0 , 0 , 0 , 0 , 0
BC Design=,, 0 ,, 0 ,,,,,,

Type RM Length L Ch R = 1 ,27.08   ,8,8,8
BEGIN DESCRIPTION:
È¾´Ü¼öÁ¤
END DESCRIPTION:
#Sta/Elev= 23
       0    4.72    25.7    4.91    35.7    4.82      54    4.97      54       4
   54.85       4   54.85    3.63      56    3.63   61.96     .77   74.86     .77
   76.46    -.03   83.26    -.03   84.86     .77   97.23     .77     102    3.63
  103.15    3.63  103.15       4     104       4     104    4.99   125.8    4.94
   133.8    5.02   142.1    4.91     161     4.7
#Mann= 3 , 0 , 0
       0     .03       0      54     .03       0     104     .03       0
Bank Sta=54,104
Exp/Cntr=0.5,0.3

Type RM Length L Ch R = 1 ,27      ,50,50,50
#Sta/Elev= 27
       0    5.21    34.7    5.03    34.7    4.83    44.2    4.98    50.8    4.83
    50.8    5.03    52.8    5.15    67.5    5.18      71    4.93    74.2    3.64
    80.1     .76   92.97     .76   94.57    -.04  103.37    -.04  104.97     .76
  115.08     .76   121.1    3.57   123.7    4.87     124    4.87   129.2    5.27
   142.6    5.12   144.6    5.02   144.6    4.82   152.6    5.02   160.8    4.87
   160.8    5.07   194.6    5.07
#Mann= 3 , 0 , 0
       0     .03       0      71     .03       0     124     .03       0
Levee=-1,67.5,6,-1,129.2,6,,
Bank Sta=71,124
Exp/Cntr=0.3,0.1

Type RM Length L Ch R = 1 ,26      ,50,50,50
#Sta/Elev= 29
       0    4.89       0    4.79    26.3    4.79    35.8    4.67    35.8    4.87
      50    5.12    56.6    4.94    59.2    3.55   65.34     .71   78.36     .71
   79.96    -.09   86.76    -.09   88.36     .71   99.86     .71   106.2    3.61
   108.3    4.82     109    4.82   116.5    5.37     120    5.37   124.6    5.06
   127.6    5.06   129.6    4.96   129.6    4.76   137.8    4.89   145.7    4.69
   145.7    4.89   147.7    4.89   150.2    5.01   180.2    5.01
#Mann= 3 , 0 , 0
       0     .03       0    56.6     .03       0     109     .03       0
Levee=-1,50,6,-1,116.5,6,,
Bank Sta=56.6,109
Exp/Cntr=0.3,0.1

Type RM Length L Ch R = 1 ,25      ,33,33,33
#Sta/Elev= 30
       0    4.96    33.8    4.96    33.8    4.76    34.3    4.89    40.5    4.89
    49.9    4.66    49.9    4.86    51.9    4.99    65.2    5.03    71.2    4.76
    73.4    3.64   79.71     .66   94.72     .66   96.32    -.14  103.12    -.14
  104.72     .66   114.1     .66   120.2    3.63   122.2    4.95   125.2    5.46
     135    5.46   138.8    4.91     144    4.86     144    4.66   151.8    4.81
   159.9    4.56   159.9    4.76   161.9    4.76   164.1    4.91   195.2    4.91
#Mann= 3 , 0 , 0
       0     .03       0    71.2     .03       0   122.2     .03       0
Levee=-1,65.5,6,-1,125.2,6,,
Bank Sta=71.2,122.2
Exp/Cntr=0.3,0.1

Type RM Length L Ch R = 1 ,24.17   ,17,17,17
#Sta/Elev= 28
       0    4.82       0    4.65     9.4    4.65     9.4    4.85    11.4    4.94
    14.4    4.94    23.7    5.22    30.5    4.87    32.9    3.57    37.8    1.17
    37.8     .62   55.99     .62   57.59    -.18   64.39    -.18   65.99     .62
    75.2     .62    75.2    1.45    79.7    3.57    81.7    4.87    82.7    4.87
    83.7    4.87    89.2    5.37    93.2    5.37    98.2    4.92   101.2    4.87
   103.4    4.62   103.9    4.62   110.7    4.77
#Mann= 3 , 0 , 0
       0     .03       0    30.5     .03       0    81.7     .03       0
Levee=-1,23.7,6,-1,89.2,6,,
Bank Sta=30.5,81.7
Exp/Cntr=0.3,0.1

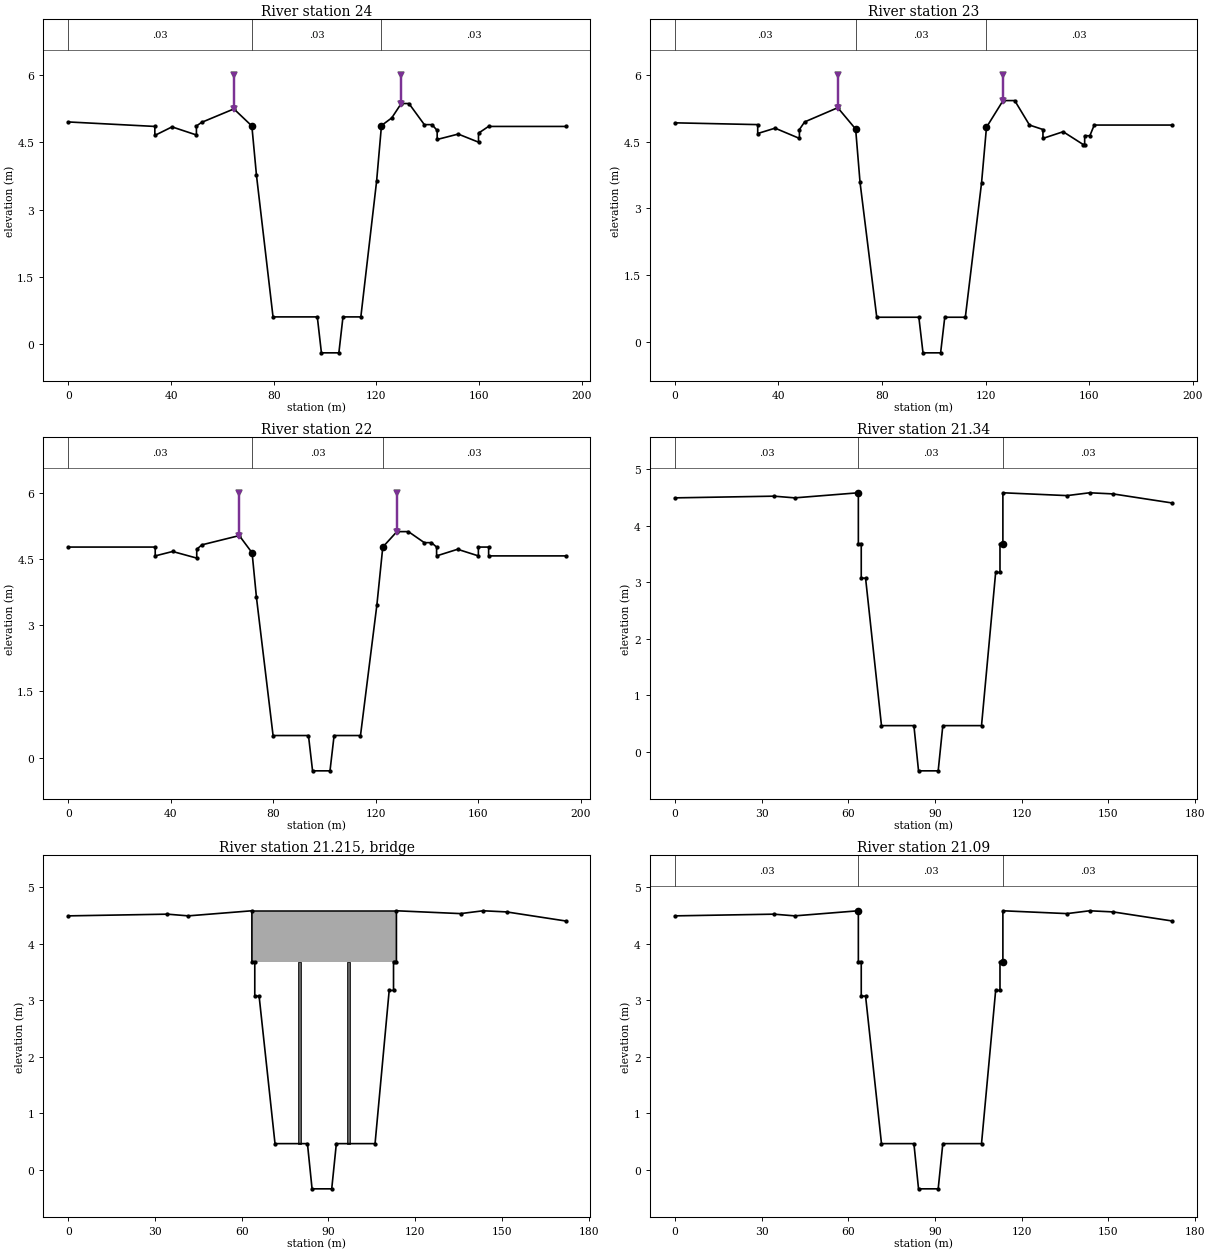
Type RM Length L Ch R = 1 ,24      ,50,50,50
#Sta/Elev= 30
       0    4.95    33.7    4.85    33.7    4.65    40.4    4.84    49.9    4.66
    49.9    4.86    51.9    4.94    64.5    5.24    71.5    4.86    73.3    3.76
   79.75     .61      97     .61    98.6    -.19   105.4    -.19     107     .61
  113.96     .61   120.1    3.63     122    4.87     126    5.04   129.7    5.36
   132.7    5.36   138.7    4.89   141.7    4.89   143.7    4.76   143.7    4.56
   151.9    4.68   159.8     4.5   159.8     4.7   163.7    4.85   193.7    4.85
#Mann= 3 , 0 , 0
       0     .03       0    71.5     .03       0     122     .03       0
Levee=-1,64.5,6,-1,129.7,6,,
Bank Sta=71.5,122
Exp/Cntr=0.3,0.1

Type RM Length L Ch R = 1 ,23      ,50,50,50
#Sta/Elev= 30
       0    4.92      32    4.88      32    4.68    38.7     4.8    48.1    4.57
    48.1    4.77    50.1    4.94    62.9    5.26    69.8    4.78    71.5    3.58
   77.95     .55    94.2     .55    95.8    -.25   102.6    -.25   104.2     .55
  112.14     .55   118.4    3.57   120.3    4.82   126.7    5.42   131.2    5.42
   136.9    4.87   142.1    4.77   142.1    4.57   149.9    4.72   157.7    4.43
   158.2    4.43   158.2    4.63   160.2    4.63   161.9    4.87   191.9    4.87
#Mann= 3 , 0 , 0
       0     .03       0    69.8     .03       0   120.3     .03       0
Levee=-1,62.9,6,-1,126.7,6,,
Bank Sta=69.8,120.3
Exp/Cntr=0.3,0.1

Type RM Length L Ch R = 1 ,22      ,16,16,16
#Sta/Elev= 30
       0    4.77    33.9    4.77    33.9    4.57    40.7    4.67    50.1    4.52
    50.1    4.72    52.1    4.82    66.7    5.03    71.7    4.64    73.4    3.63
   79.89      .5    93.7      .5    95.3     -.3   102.1     -.3   103.7      .5
     114      .5   120.4    3.46   122.7    4.77   128.2    5.12   132.7    5.12
   138.9    4.87   141.7    4.87   143.7    4.77   143.7    4.57   151.9    4.72
     160    4.57     160    4.77     164    4.77     164    4.57     194    4.57
#Mann= 3 , 0 , 0
       0     .03       0    71.7     .03       0   122.7     .03       0
Levee=-1,66.7,6,-1,128.2,6,,
Bank Sta=71.7,122.7
Exp/Cntr=0.3,0.1

Type RM Length L Ch R = 1 ,21.34   ,25,25,25
#Sta/Elev= 23
       0    4.49    34.3    4.52    41.5    4.49    63.5    4.58    63.5    3.68
    64.5    3.68    64.5    3.07      66    3.07    71.5     .46   82.72     .46
   84.32    -.34   91.12    -.34   92.72     .46  106.11     .46     111    3.17
   112.5    3.17   112.5    3.68   113.5    3.68   113.5    4.58   135.7    4.53
   143.5    4.58   151.6    4.56     172     4.4
#Mann= 3 , 0 , 0
       0     .03       0    63.5     .03       0   113.5     .03       0
Bank Sta=63.5,113.5
Exp/Cntr=0.5,0.3

Type RM Length L Ch R = 3 ,21.215  ,,,
BEGIN DESCRIPTION:
È­Á¤12±³
END DESCRIPTION:
Bridge Culvert--1,0,-1,-1, 0
Deck Dist Width WeirC Skew NumUp NumDn MinLoCord MaxHiCord MaxSubmerge Is_Ogee
0.1,24,1.44,0, 2, 2, , , 0.95, 0, 0,0,,
    63.5   113.5
    4.58    4.58
    3.68    3.68
    63.5   113.5
    4.58    4.58
    3.68    3.68
Pier Skew, UpSta & Num, DnSta & Num=  ,80, 2 ,80, 2 , 0 , 0 , 0 ,,
       1       1
       0       5
       1       1
       0       5
Pier Skew, UpSta & Num, DnSta & Num=  ,97, 2 ,97, 2 , 0 , 0 , 0 ,,
       1       1
       0       5
       1       1
       0       5
BR Coef=-1 , 0 , 0 ,, 0 ,,,0.8,-1,,0,
WSPro=,,,, 1 ,,,, 0 ,,,, 0 ,,,,-1 ,-1 ,-1 , 0 , 0 , 0 , 0 , 0
BC Design=,, 0 ,, 0 ,,,,,,

Type RM Length L Ch R = 1 ,21.09   ,9,9,9
#Sta/Elev= 23
       0    4.49    34.3    4.52    41.5    4.49    63.5    4.58    63.5    3.68
    64.5    3.68    64.5    3.07      66    3.07    71.5     .46   82.72     .46
   84.32    -.34   91.12    -.34   92.72     .46  106.11     .46     111    3.17
   112.5    3.17   112.5    3.68   113.5    3.68   113.5    4.58   135.7    4.53
   143.5    4.58   151.6    4.56     172     4.4
#Mann= 3 , 0 , 0
       0     .03       0    63.5     .03       0   113.5     .03       0
Bank Sta=63.5,113.5
Exp/Cntr=0.5,0.3