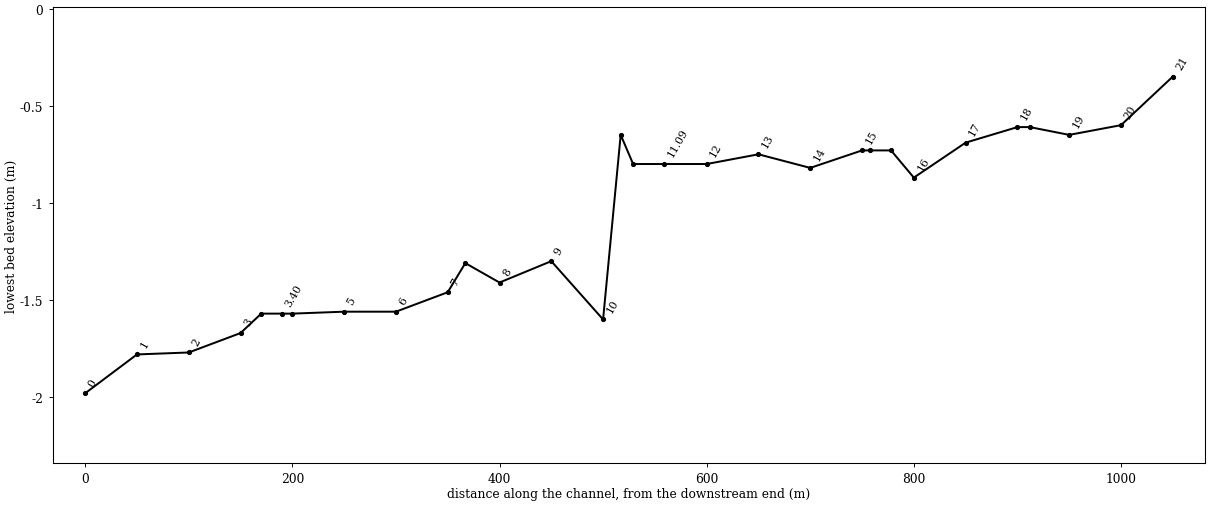
HEC-RAS study hj.prj: Hwajung_plan

--- hj.g01 (geometry) --- (continued)

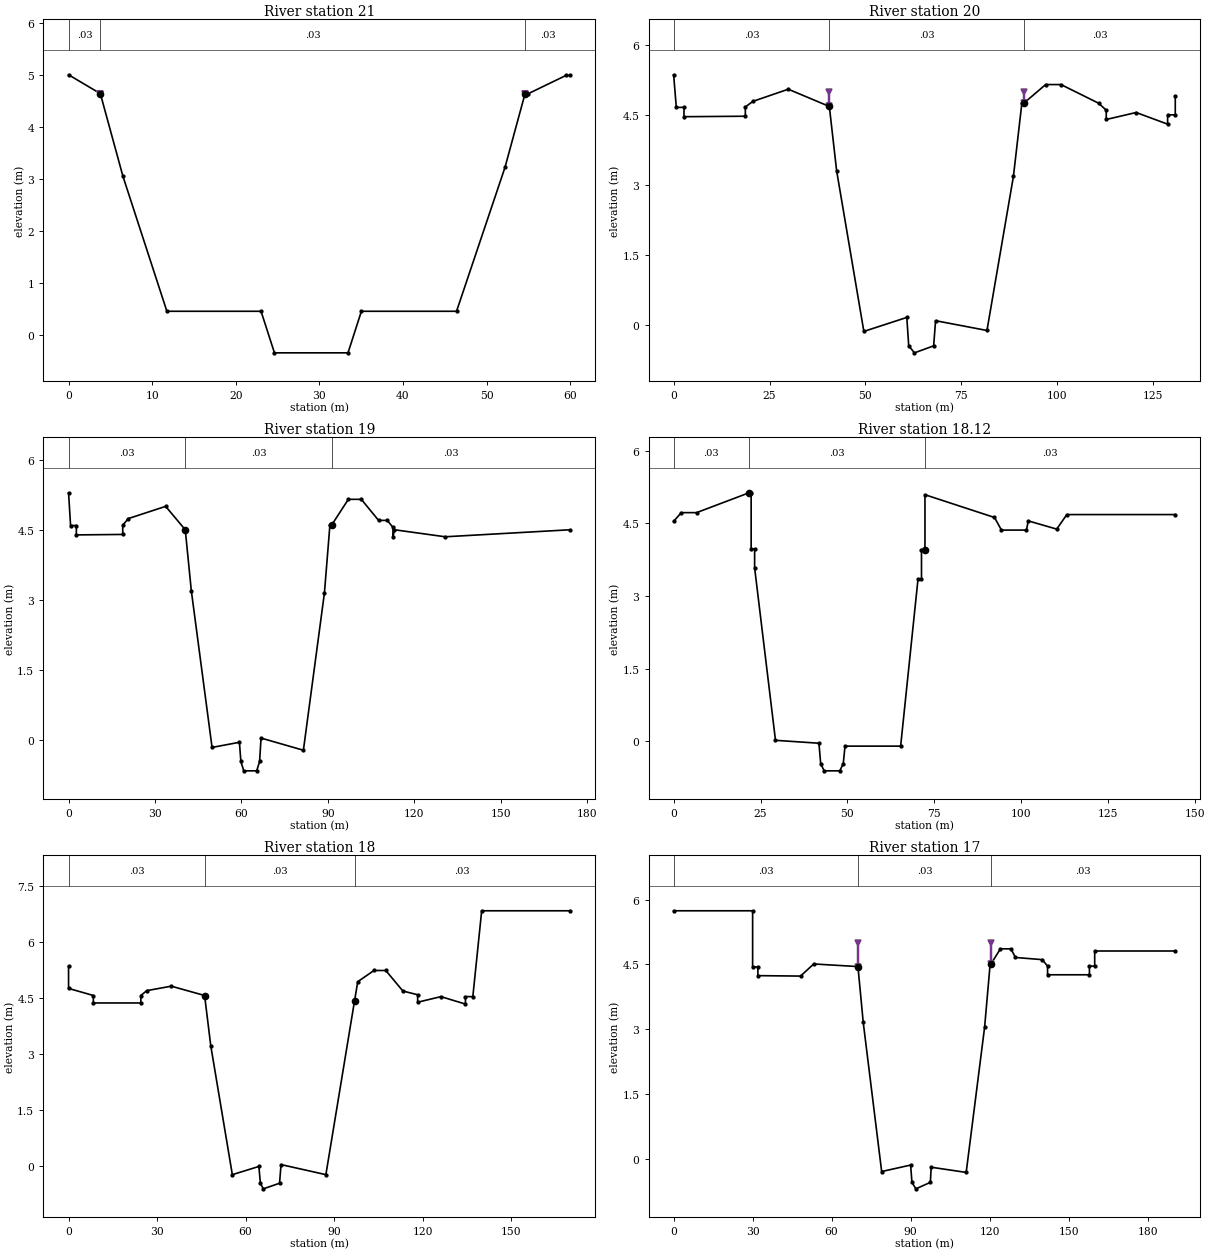
Type RM Length L Ch R = 1 ,21      ,50,50,50
#Sta/Elev= 14
       0  5.0023     3.8    4.64     6.5    3.05 11.7595     .45 23.0235     .45
 24.6235    -.35 33.4235    -.35 35.0235     .45 46.4046     .45    52.2    3.22
    54.6    4.64      55    4.64    59.5    4.99      60    4.99
#Mann= 3 , 0 , 0
       0     .03       0     3.8     .03       0    54.6     .03       0
Levee=-1,3.8,4.64,-1,54.6,4.64,,
Bank Sta=3.8,54.6
Exp/Cntr=0.3,0.1

Type RM Length L Ch R = 1 ,20      ,50,50,50
#Sta/Elev= 30
       0    5.37      .7    4.67     2.7    4.67     2.7    4.47    18.7    4.48
    18.7    4.68    20.7     4.8    29.9    5.06    40.6    4.69    42.5    3.31
    49.6    -.14    60.8     .16    61.3    -.45    62.8     -.6    67.8    -.45
    68.3     .09    81.7    -.12    88.6    3.19    90.8    4.76    91.3    4.76
      97    5.16     101    5.16   110.8    4.76   112.8    4.61   112.8    4.41
   120.6    4.56   128.8    4.31   128.8    4.51   130.8    4.51   130.8    4.91
#Mann= 3 , 0 , 0
       0     .03       0    40.6     .03       0    91.3     .03       0
Levee=-1,40.6,5,-1,91.3,5,,
Bank Sta=40.6,91.3
Exp/Cntr=0.3,0.1

Type RM Length L Ch R = 1 ,19      ,38,38,38
#Sta/Elev= 30
       0    5.29      .7    4.59     2.7    4.59     2.7    4.39    18.8     4.4
    18.8     4.6    20.8    4.74    33.7       5    40.5     4.5    42.6     3.2
    49.8    -.15    59.3    -.04    59.8    -.45    60.8    -.65    65.3    -.65
    66.3    -.45    66.8     .05    81.5    -.21    88.8    3.15    90.7     4.6
    91.3     4.6    97.1    5.15   101.6    5.15   107.6     4.7   110.6     4.7
   112.6    4.55   112.6    4.35   113.1     4.5   130.7    4.35   174.1     4.5
#Mann= 3 , 0 , 0
       0     .03       0    40.5     .03       0    91.3     .03       0
Bank Sta=40.5,91.3
Exp/Cntr=0.3,0.1

Type RM Length L Ch R = 1 ,18.12   ,12,12,12
#Sta/Elev= 28
       0    4.54     2.2    4.72     6.6    4.72    21.7    5.13    22.3    5.12
    22.3    3.97    23.3    3.97    23.3    3.58    29.3     .02    41.8    -.04
    42.3    -.46    43.3    -.61    47.8    -.61    48.8    -.46    49.3     -.1
    65.3     -.1    70.3    3.35    71.3    3.35    71.3    3.94    72.3    3.94
    72.3    5.09    92.3    4.62    94.3    4.36   101.5    4.36     102    4.55
   110.2    4.38   113.1    4.68   144.3    4.68
#Mann= 3 , 0 , 0
       0     .03       0    21.7     .03       0    72.3     .03       0
Bank Sta=21.7,72.3
Exp/Cntr=0.3,0.1

Type RM Length L Ch R = 1 ,18      ,50,50,50
#Sta/Elev= 30
       0    5.36       0    4.76     8.4    4.57     8.4    4.37    24.5    4.37
    24.5    4.57    26.5     4.7    34.8    4.82    46.1    4.57    48.2    3.22
    55.5    -.23    64.5    -.01      65    -.46      66    -.61    71.5    -.46
      72     .04    87.2    -.23    96.9    4.42      98    4.94   103.5    5.24
   107.5    5.24   113.3    4.69   118.3    4.59   118.3    4.39   126.2    4.54
   134.5    4.34   134.5    4.54     137    4.54     140    6.84     170    6.84
#Mann= 3 , 0 , 0
       0     .03       0    46.1     .03       0    96.9     .03       0
Bank Sta=46.1,96.9
Exp/Cntr=0.3,0.1

Type RM Length L Ch R = 1 ,17      ,50,50,50
#Sta/Elev= 30
       0    5.74      30    5.74      30    4.44      32    4.44      32    4.24
    48.2    4.23    53.2    4.51      70    4.45      72    3.16      79    -.29
      90    -.14    90.5    -.54      92    -.69    97.5    -.54    97.8    -.19
   111.1    -.31   118.1    3.05   120.2    4.51   120.5    4.51   124.1    4.86
   128.1    4.86   129.8    4.66     140    4.61     142    4.46     142    4.26
   157.9    4.26   157.9    4.46   159.9    4.46   159.9    4.81   190.5    4.81
#Mann= 3 , 0 , 0
       0     .03       0      70     .03       0   120.5     .03       0
Levee=-1,70,5,-1,120.5,5,,
Bank Sta=70,120.5
Exp/Cntr=0.3,0.1

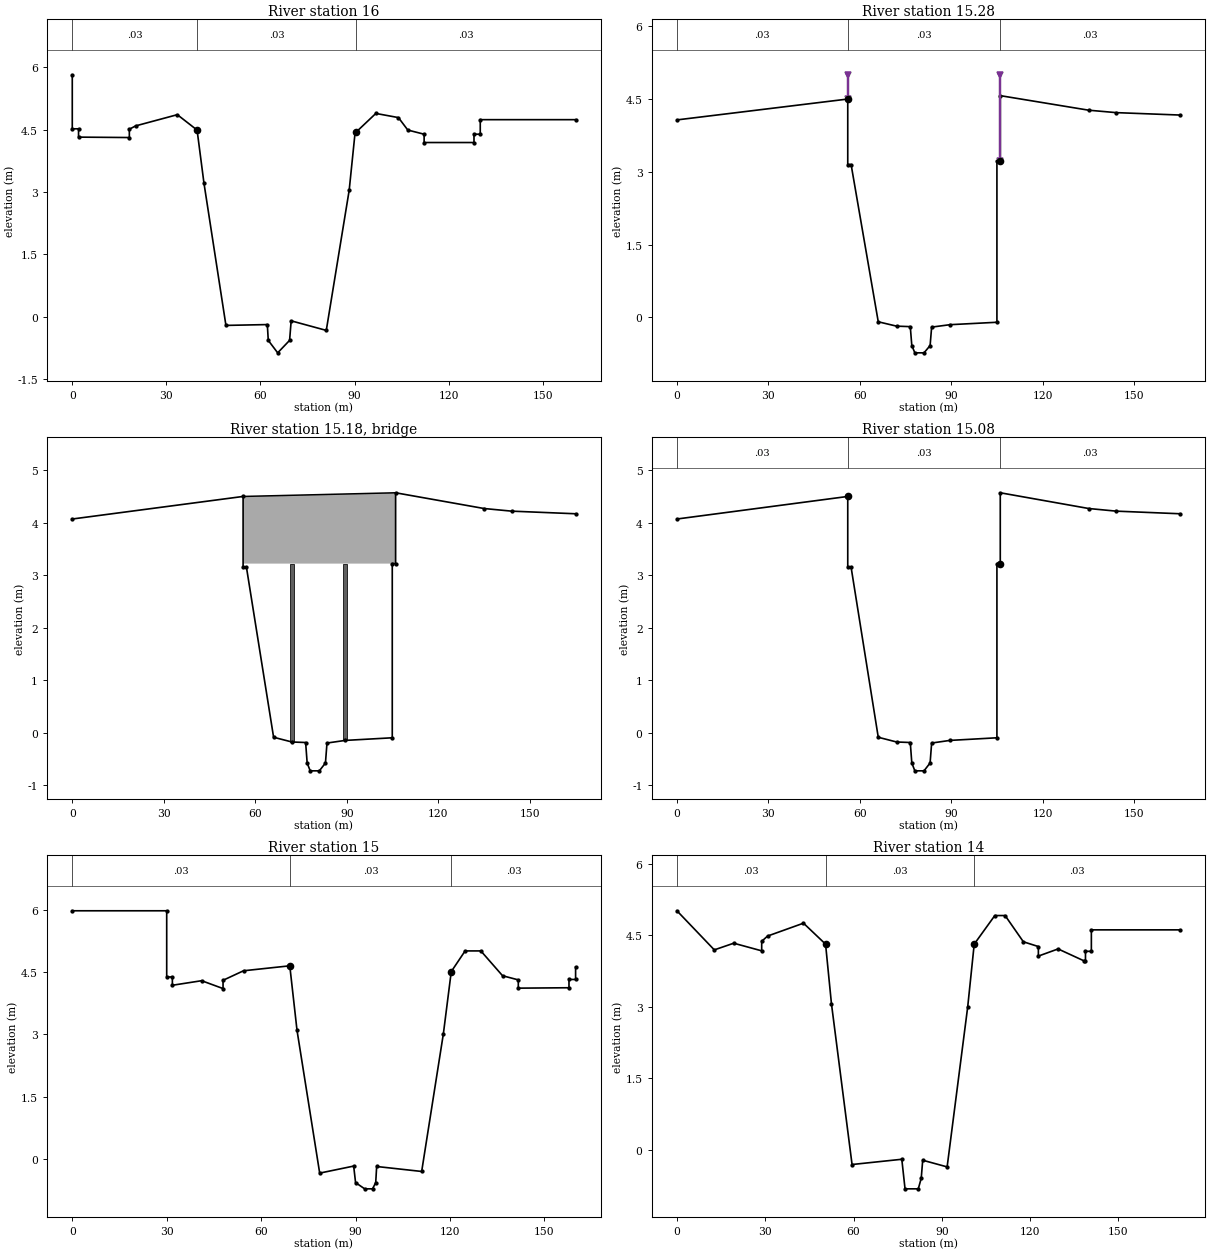
Type RM Length L Ch R = 1 ,16      ,22,22,22
#Sta/Elev= 30
       0    5.82       0    4.52       2    4.52       2    4.32    18.2    4.31
    18.2    4.51    20.2    4.59    33.5    4.86    39.8    4.49      42    3.21
      49    -.21    62.2    -.19    62.5    -.57    65.5    -.87    69.3    -.57
    69.8     -.1      81    -.33    88.3    3.04    90.2    4.44    90.5    4.44
    96.8    4.89     104    4.79     107    4.49   112.2    4.39   112.2    4.19
   128.1    4.19   128.1    4.39   130.1    4.39   130.1    4.74   160.5    4.74
#Mann= 3 , 0 , 0
       0     .03       0    39.8     .03       0    90.5     .03       0
Bank Sta=39.8,90.5
Exp/Cntr=0.3,0.1

Type RM Length L Ch R = 1 ,15.28   ,20,20,20
#Sta/Elev= 20
       0    4.07      56     4.5      56    3.15    57.1    3.15      66    -.09
      72    -.18    76.5    -.19      77    -.58      78    -.73      81    -.73
      83    -.58    83.5     -.2    89.5    -.15   104.9     -.1   104.9    3.22
     106    3.22     106    4.57     135    4.27     144    4.22     165    4.17
#Mann= 3 , 0 , 0
       0     .03       0      56     .03       0     106     .03       0
Levee=-1,56,5,-1,106,5,,
Bank Sta=56,106
Exp/Cntr=0.5,0.3

Type RM Length L Ch R = 3 ,15.18   ,,,
BEGIN DESCRIPTION:
È­Á¤14±³
END DESCRIPTION:
Bridge Culvert--1,0,-1,-1, 0
Deck Dist Width WeirC Skew NumUp NumDn MinLoCord MaxHiCord MaxSubmerge Is_Ogee
0.1,19,1.44,0, 2, 2, , , 0.95, 0, 0,0,,
      56     106
     4.5    4.57
    3.22    3.22
      56     106
     4.5    4.57
    3.22    3.22
Pier Skew, UpSta & Num, DnSta & Num=  ,72, 2 ,72, 2 , 0 , 0 , 0 ,,
     1.2     1.2
       0       4
     1.2     1.2
       0       4
Pier Skew, UpSta & Num, DnSta & Num=  ,89.5, 2 ,89.5, 2 , 0 , 0 , 0 ,,
     1.2     1.2
       0       4
     1.2     1.2
       0       4
BR Coef=-1 , 0 , 0 ,, 0 ,,,0.8,-1,,0,
WSPro=,,,, 1 ,,,, 0 ,,,, 0 ,,,,-1 ,-1 ,-1 , 0 , 0 , 0 , 0 , 0
BC Design=,, 0 ,, 0 ,,,,,,

Type RM Length L Ch R = 1 ,15.08   ,8,8,8
#Sta/Elev= 20
       0    4.07      56     4.5      56    3.15    57.1    3.15      66    -.09
      72    -.18    76.5    -.19      77    -.58      78    -.73      81    -.73
      83    -.58    83.5     -.2    89.5    -.15   104.9     -.1   104.9    3.22
     106    3.22     106    4.57     135    4.27     144    4.22     165    4.17
#Mann= 3 , 0 , 0
       0     .03       0      56     .03       0     106     .03       0
Bank Sta=56,106
Exp/Cntr=0.5,0.3

Type RM Length L Ch R = 1 ,15      ,50,50,50
#Sta/Elev= 30
       0    5.99      30    5.99      30    4.39    31.8    4.39    31.8    4.19
    41.1     4.3    47.9    4.11    47.9    4.31    54.4    4.54    69.1    4.66
    71.4     3.1    78.6    -.35    89.4    -.18      90    -.58    92.9    -.73
    95.4    -.73    96.4    -.58    96.7    -.19     111    -.31   117.9    3.02
   120.4    4.52   124.8    5.02   129.8    5.02   136.7    4.42   141.7    4.32
   141.7    4.12   157.8    4.13   157.8    4.33   159.9    4.33   159.9    4.63
#Mann= 3 , 0 , 0
       0     .03       0    69.1     .03       0   120.4     .03       0
Bank Sta=69.1,120.4
Exp/Cntr=0.3,0.1

Type RM Length L Ch R = 1 ,14      ,50,50,50
#Sta/Elev= 30
       0    5.01    12.7    4.19    19.3    4.33    28.8    4.17    28.8    4.37
    30.8    4.48      43    4.75    50.5    4.31    52.5    3.06    59.5    -.31
    76.4     -.2    77.5    -.82      82    -.82      83     -.6    83.5    -.22
    91.8    -.36    98.8       3     101    4.31     108    4.91   111.5    4.91
   117.7    4.36   122.8    4.26   122.8    4.06   129.5    4.21   138.3    3.96
   138.8    3.96   138.8    4.16   140.8    4.16   140.8    4.61     171    4.61
#Mann= 3 , 0 , 0
       0     .03       0    50.5     .03       0     101     .03       0
Bank Sta=50.5,101
Exp/Cntr=0.3,0.1

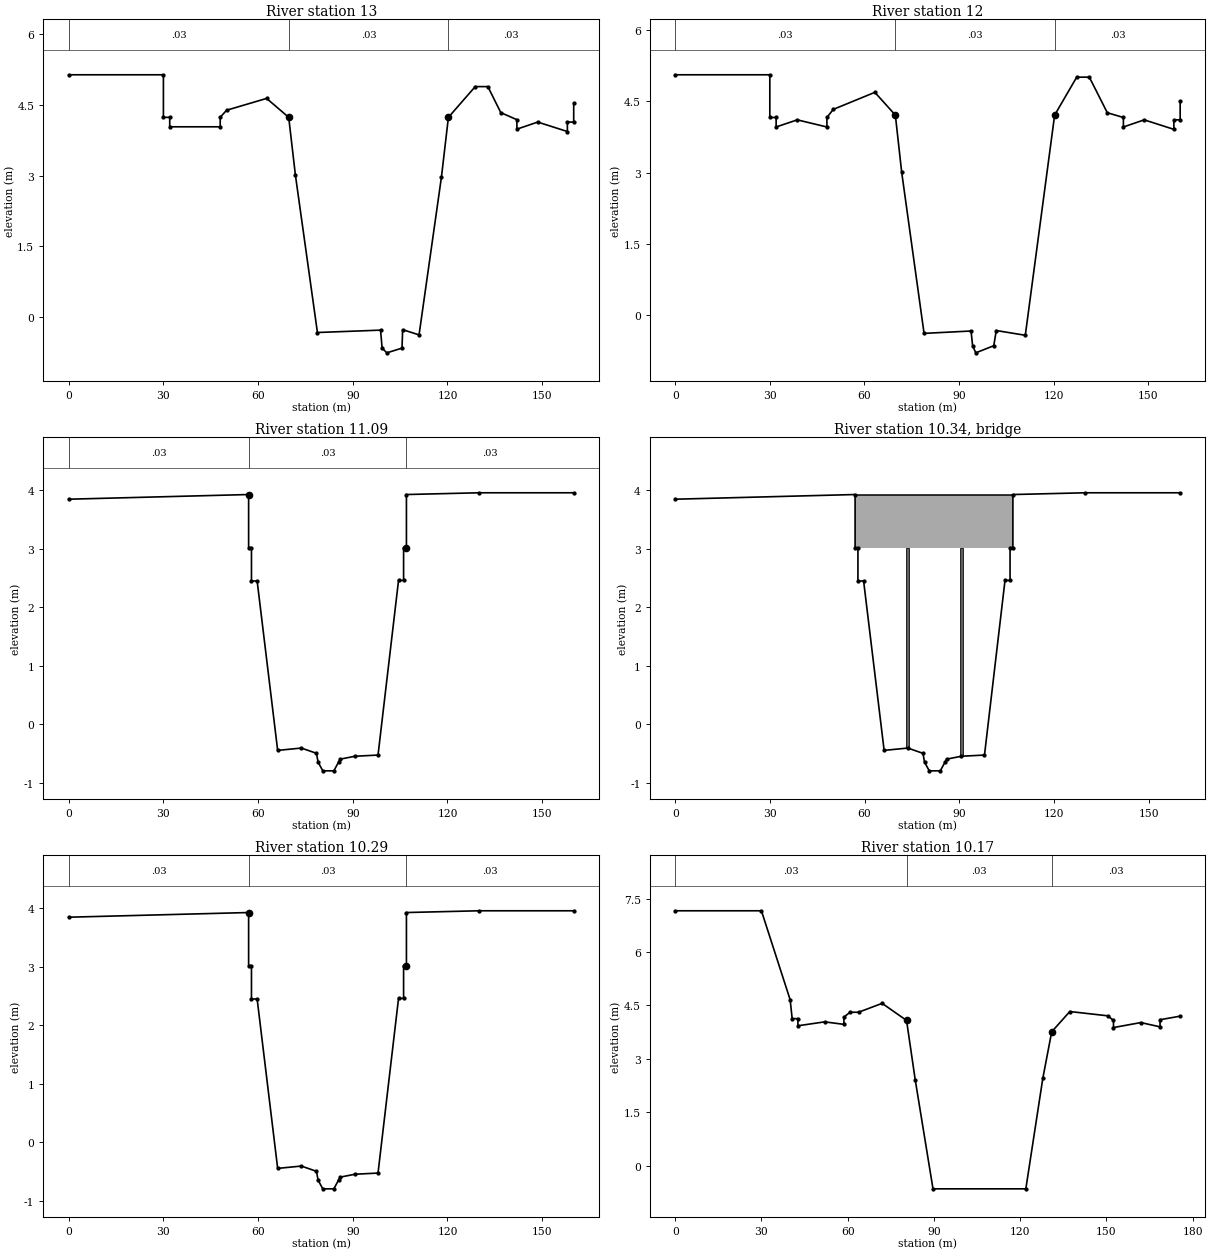
Type RM Length L Ch R = 1 ,13      ,50,50,50
#Sta/Elev= 30
       0    5.13      30    5.13      30    4.23      32    4.23      32    4.03
      48    4.03      48    4.23      50    4.38    62.7    4.63    69.7    4.23
    71.8    3.02    78.8    -.32    98.8    -.27    99.3    -.65   100.8    -.75
   105.6    -.65   105.8    -.26     111    -.37   118.1    2.97   120.3    4.23
   128.8    4.88   132.8    4.88   136.9    4.33     142    4.18     142    3.98
   148.6    4.13     158    3.93     158    4.13     160    4.13     160    4.53
#Mann= 3 , 0 , 0
       0     .03       0    69.7     .03       0   120.3     .03       0
Bank Sta=69.7,120.3
Exp/Cntr=0.3,0.1

Type RM Length L Ch R = 1 ,12      ,41,41,41
#Sta/Elev= 30
       0    5.06      30    5.06      30    4.16      32    4.16      32    3.96
    38.7    4.11    48.1    3.96    48.1    4.16    50.1    4.33    63.3    4.69
    69.8    4.21    71.8    3.01    78.9    -.39    93.8    -.34    94.3    -.65
    95.3     -.8     101    -.65   101.8    -.33     111    -.43   120.3    4.21
   127.3    5.01   131.3    5.01     137    4.26   142.1    4.16   142.1    3.96
   148.7    4.11   158.1    3.91   158.1    4.11   160.1    4.11   160.1    4.51
#Mann= 3 , 0 , 0
       0     .03       0    69.8     .03       0   120.3     .03       0
Bank Sta=69.8,120.3
Exp/Cntr=0.3,0.1

Type RM Length L Ch R = 1 ,11.09   ,30,30,30
#Sta/Elev= 23
       0    3.85      57    3.93      57    3.02    57.9    3.02    57.9    2.45
    59.7    2.45    66.2    -.45    73.7    -.41    78.5     -.5      79    -.65
    80.5     -.8      84     -.8    85.5    -.65      86     -.6    90.7    -.55
      98    -.53   104.5    2.46   106.1    2.46   106.1    3.02     107    3.02
     107    3.93     130    3.96     160    3.96
#Mann= 3 , 0 , 0
       0     .03       0      57     .03       0     107     .03       0
Bank Sta=57,107
Exp/Cntr=0.5,0.3

Type RM Length L Ch R = 3 ,10.34   ,,,
BEGIN DESCRIPTION:
È­Á¤15±³
END DESCRIPTION:
Bridge Culvert--1,0,-1,-1, 0
Deck Dist Width WeirC Skew NumUp NumDn MinLoCord MaxHiCord MaxSubmerge Is_Ogee
0.1,29,1.44,0, 2, 2, , , 0.95, 0, 0,0,,
      57     107
    3.93    3.93
    3.02    3.02
      57     107
    3.93    3.93
    3.02    3.02
Pier Skew, UpSta & Num, DnSta & Num=  ,73.7, 2 ,73.7, 2 , 0 , 0 , 0 ,,
       1       1
       0       4
       1       1
       0       4
Pier Skew, UpSta & Num, DnSta & Num=  ,90.7, 2 ,90.7, 2 , 0 , 0 , 0 ,,
       1       1
       0       4
       1       1
       0       4
BR Coef=-1 , 0 , 0 ,, 0 ,,,0.8,-1,,0,
WSPro=,,,, 1 ,,,, 0 ,,,, 0 ,,,,-1 ,-1 ,-1 , 0 , 0 , 0 , 0 , 0
BC Design=,, 0 ,, 0 ,,,,,,

Type RM Length L Ch R = 1 ,10.29   ,12,12,12
#Sta/Elev= 23
       0    3.85      57    3.93      57    3.02    57.9    3.02    57.9    2.45
    59.7    2.45    66.2    -.45    73.7    -.41    78.5     -.5      79    -.65
    80.5     -.8      84     -.8    85.5    -.65      86     -.6    90.7    -.55
      98    -.53   104.5    2.46   106.1    2.46   106.1    3.02     107    3.02
     107    3.93     130    3.96     160    3.96
#Mann= 3 , 0 , 0
       0     .03       0      57     .03       0     107     .03       0
Bank Sta=57,107
Exp/Cntr=0.5,0.3

Type RM Length L Ch R = 1 ,10.17   ,17,17,17
BEGIN DESCRIPTION:
10+17³«Â÷°ø»ó·ù
END DESCRIPTION:
#Sta/Elev= 26
       0    7.16      30    7.16      40    4.66    40.7    4.13    42.7    4.13
    42.7    3.93      52    4.04    58.7    3.97    58.7    4.17    60.8    4.31
    63.8    4.31      72    4.56    80.5    4.08    83.5    2.42    89.7    -.65
     122    -.65   127.9    2.45     131    3.76   137.3    4.33   150.5    4.21
   152.5    4.08   152.5    3.88     162    4.02   168.7     3.9   168.7     4.1
   175.7     4.2
#Mann= 3 , 0 , 0
       0     .03       0    80.5     .03       0     131     .03       0
Bank Sta=80.5,131
Exp/Cntr=0.3,0.1

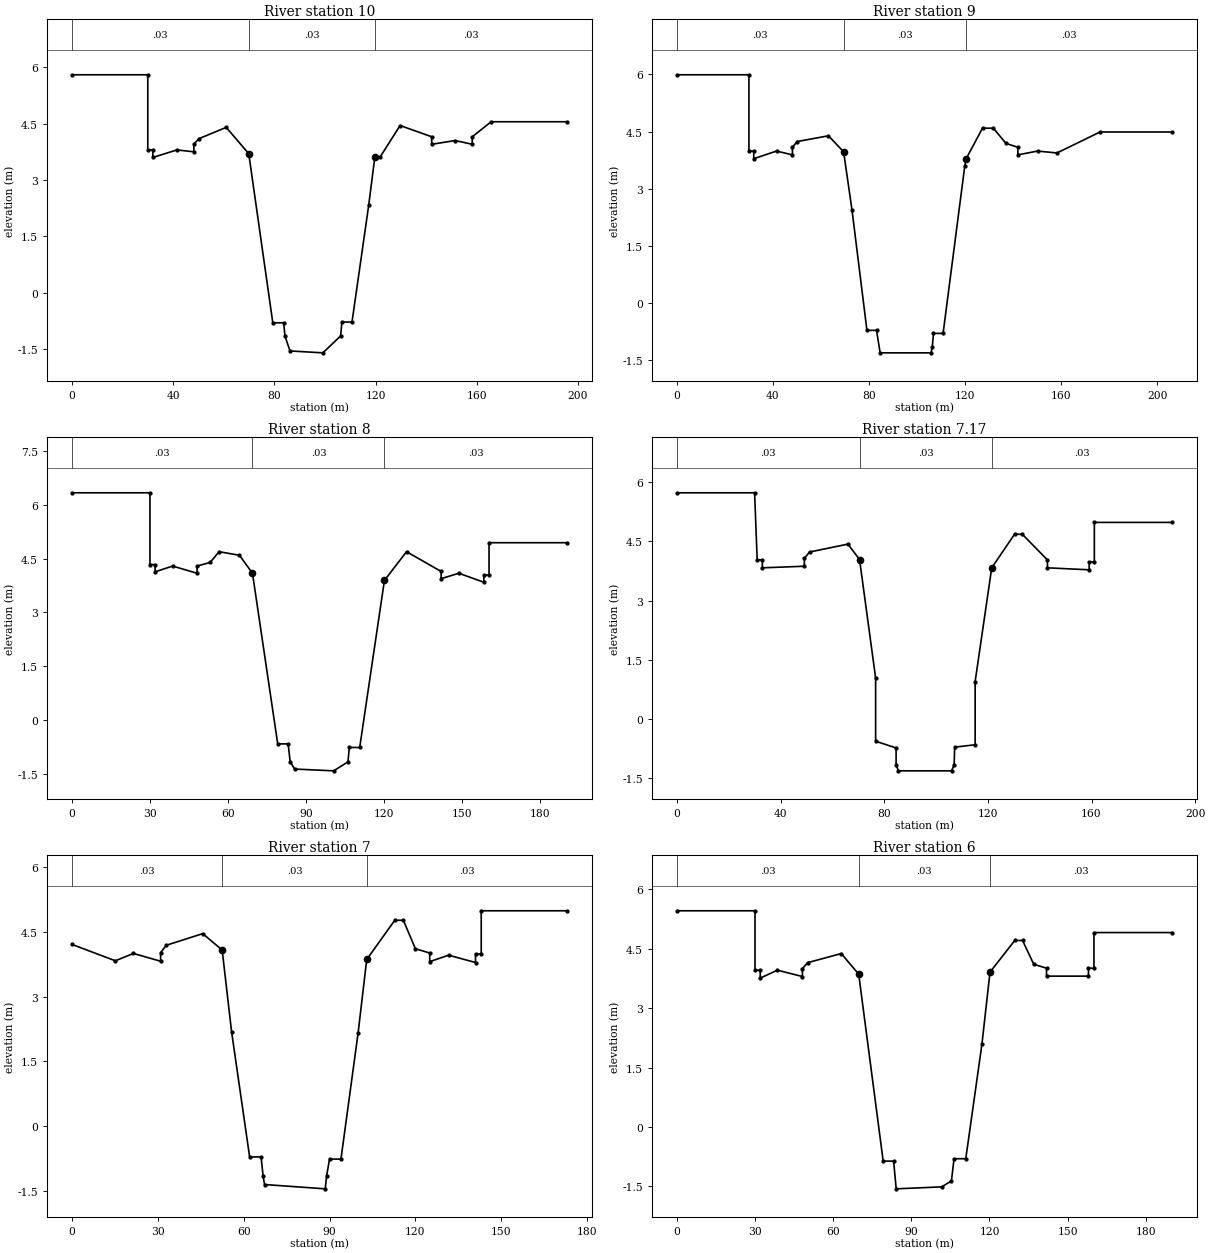
Type RM Length L Ch R = 1 ,10      ,50,50,50
#Sta/Elev= 30
       0     5.8      30     5.8      30     3.8      32     3.8      32     3.6
    41.5     3.8    48.2    3.75    48.2    3.95    50.2     4.1      61     4.4
    69.9     3.7    79.4     -.8    83.7     -.8    84.2   -1.15    86.2   -1.55
    99.2    -1.6   106.2   -1.15   106.7    -.78   110.7    -.78   117.3    2.33
   119.7     3.6   121.7     3.6   129.7    4.45   142.2    4.15   142.2    3.95
   151.5    4.05   158.2    3.95   158.2    4.15   165.7    4.55   195.7    4.55
#Mann= 3 , 0 , 0
       0     .03       0    69.9     .03       0   119.7     .03       0
Bank Sta=69.9,119.7
Exp/Cntr=0.3,0.1

Type RM Length L Ch R = 1 ,9       ,50,50,50
#Sta/Elev= 30
       0    5.99      30    5.99      30    3.99      32    3.99      32    3.79
    41.5    3.99    48.1    3.89    48.1    4.09    50.1    4.24    63.1    4.39
    69.4    3.97    72.9    2.44    79.1    -.71    83.1    -.71    84.6    -1.3
   105.8    -1.3   106.3   -1.15   106.8    -.79   110.8    -.79   119.8    3.59
   120.4    3.79   127.2    4.59   131.7    4.59     137    4.19   141.9    4.09
   141.9    3.89   150.1    3.99   158.2    3.94   176.1    4.49   206.1    4.49
#Mann= 3 , 0 , 0
       0     .03       0    69.4     .03       0   120.4     .03       0
Bank Sta=69.4,120.4
Exp/Cntr=0.3,0.1

Type RM Length L Ch R = 1 ,8       ,33,33,33
#Sta/Elev= 30
       0    6.33      30    6.33      30    4.33      32    4.33      32    4.13
    38.7    4.29    48.1    4.09    48.1    4.29    53.1    4.39    56.6    4.69
    64.4    4.59    69.4    4.09    79.1    -.66    83.1    -.66    83.9   -1.16
    85.6   -1.36   100.6   -1.41   106.1   -1.16   106.6    -.76   110.6    -.76
   120.1    3.89   128.6    4.69   141.9    4.14   141.9    3.94   148.7    4.09
   158.3    3.84   158.3    4.04   160.3    4.04   160.3    4.94   190.3    4.94
#Mann= 3 , 0 , 0
       0     .03       0    69.4     .03       0   120.1     .03       0
Bank Sta=69.4,120.1
Exp/Cntr=0.3,0.1

Type RM Length L Ch R = 1 ,7.17    ,17,17,17
#Sta/Elev= 30
       0    5.73      30    5.73      31    4.03      33    4.03      33    3.83
    49.2    3.87    49.2    4.07    51.2    4.23      66    4.43    70.5    4.04
    76.7    1.04    76.7    -.56    84.6    -.73    84.6   -1.16    85.5   -1.31
     106   -1.31     107   -1.16   107.2    -.71   115.1    -.65   115.1     .95
   121.5    3.83   130.3    4.68   133.3    4.68     143    4.03     143    3.83
   159.1    3.78   159.1    3.98   161.1    3.98   161.1    4.98   191.1    4.98
#Mann= 3 , 0 , 0
       0     .03       0    70.5     .03       0   121.5     .03       0
Bank Sta=70.5,121.5
Exp/Cntr=0.3,0.1

Type RM Length L Ch R = 1 ,7       ,50,50,50
#Sta/Elev= 30
       0    4.21    15.2    3.83    21.5       4      31    3.82      31    4.02
      33    4.19    45.7    4.46    52.5    4.08    55.8    2.18    62.1    -.72
    66.1    -.72    66.8   -1.16    67.3   -1.36    88.5   -1.46      89   -1.16
      90    -.77      94    -.77     100    2.16     103    3.86   112.8    4.77
   115.8    4.77     120    4.11     125    4.01     125    3.81   131.6    3.96
     141    3.79     141    3.99     143    3.99     143    4.99     173    4.99
#Mann= 3 , 0 , 0
       0     .03       0    52.5     .03       0     103     .03       0
Bank Sta=52.5,103
Exp/Cntr=0.3,0.1

Type RM Length L Ch R = 1 ,6       ,50,50,50
#Sta/Elev= 30
       0    5.46      30    5.46      30    3.96      32    3.96      32    3.76
    38.6    3.96    48.2     3.8    48.2       4    50.2    4.15    63.1    4.38
    69.8    3.86    79.2    -.86    83.2    -.86    84.2   -1.56   101.7   -1.51
   105.4   -1.36   106.4     -.8   110.9     -.8   117.1    2.09   120.2    3.91
   129.7    4.71   132.7    4.71     137    4.11   141.9    4.01   141.9    3.81
     158    3.81     158    4.01   160.1    4.01   160.1    4.91   190.1    4.91
#Mann= 3 , 0 , 0
       0     .03       0    69.8     .03       0   120.2     .03       0
Bank Sta=69.8,120.2
Exp/Cntr=0.3,0.1

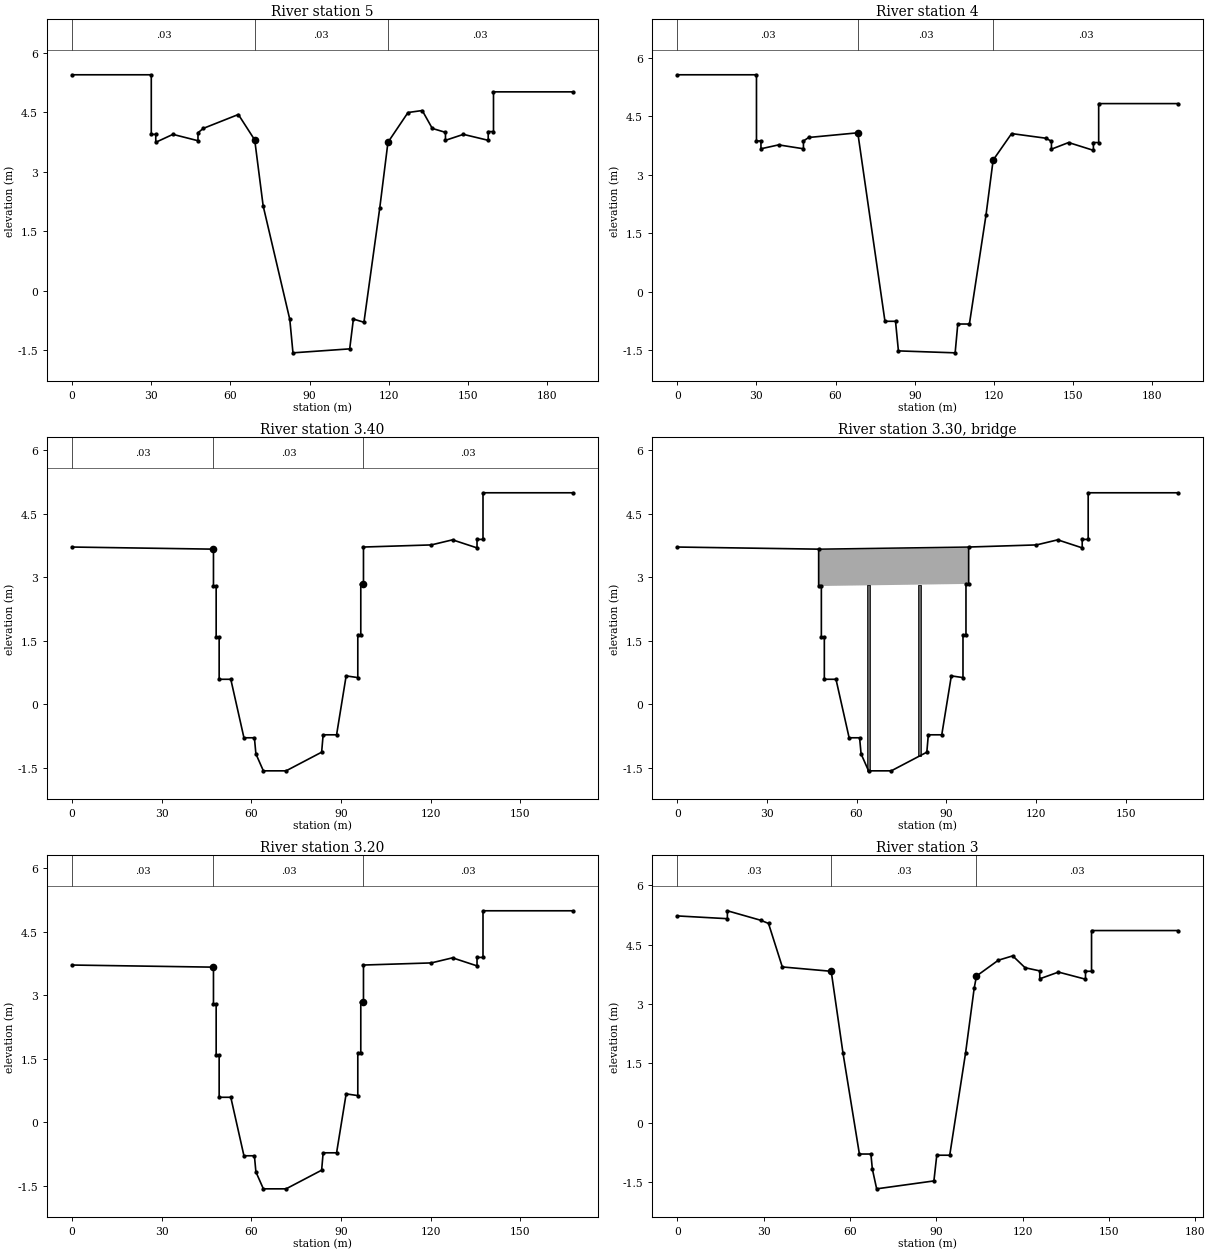
Type RM Length L Ch R = 1 ,5       ,50,50,50
#Sta/Elev= 30
       0    5.44      30    5.44      30    3.94    31.7    3.94    31.7    3.74
    38.2    3.94    47.7    3.78    47.7    3.98    49.7    4.09      63    4.44
    69.2     3.8    72.4    2.14    82.5    -.72    83.7   -1.56   105.2   -1.46
   106.6    -.71   110.6    -.79   116.6    2.09   119.7    3.74   127.3    4.49
   132.7    4.54   136.5    4.09   141.5    3.99   141.5    3.79   148.3    3.94
   157.7    3.79   157.7    4.01   159.7    4.01   159.7    5.01   189.7    5.01
#Mann= 3 , 0 , 0
       0     .03       0    69.2     .03       0   119.7     .03       0
Bank Sta=69.2,119.7
Exp/Cntr=0.3,0.1

Type RM Length L Ch R = 1 ,4       ,10,10,10
#Sta/Elev= 28
       0    5.57      30    5.57      30    3.87    31.7    3.87    31.7    3.67
    38.4    3.77    47.8    3.67    47.8    3.87    49.8    3.96    68.4    4.08
    78.7    -.76    82.7    -.76    83.8   -1.52   105.3   -1.57   106.3    -.83
   110.7    -.83     117    1.97   119.7    3.38   126.7    4.06   139.8    3.94
   141.8    3.86   141.8    3.66   148.3    3.83   157.7    3.63   157.7    3.83
   159.7    3.83   159.7    4.83   189.7    4.83
#Mann= 3 , 0 , 0
       0     .03       0    68.4     .03       0   119.7     .03       0
Bank Sta=68.4,119.7
Exp/Cntr=0.3,0.1

Type RM Length L Ch R = 1 ,3.40    ,20,20,20
#Sta/Elev= 30
       0    3.71    47.3    3.66    47.3    2.79    48.2    2.79    48.2    1.59
    49.2    1.59    49.2     .59    53.1     .59    57.5    -.79      61    -.79
    61.5   -1.17      64   -1.57    71.6   -1.57    83.5   -1.13      84    -.72
    88.5    -.72    91.7     .67    95.6     .63    95.6    1.64    96.6    1.64
    96.6    2.84    97.5    2.84    97.5    3.71   120.2    3.76   127.3    3.88
   135.5    3.69   135.5    3.89   137.5    3.89   137.5    4.99   167.5    4.99
#Mann= 3 , 0 , 0
       0     .03       0    47.3     .03       0    97.5     .03       0
Bank Sta=47.3,97.5
Exp/Cntr=0.5,0.3

Type RM Length L Ch R = 3 ,3.30    ,,,
BEGIN DESCRIPTION:
È­Á¤16±³
END DESCRIPTION:
Bridge Culvert--1,0,-1,-1, 0
Deck Dist Width WeirC Skew NumUp NumDn MinLoCord MaxHiCord MaxSubmerge Is_Ogee
0.1,19,1.44,0, 2, 2, , , 0.95, 0, 0,0,,
    47.3    97.5
    3.66    3.71
    2.79    2.84
    47.3    97.5
    3.66    3.71
    2.79    2.84
Pier Skew, UpSta & Num, DnSta & Num=  ,64, 2 ,64, 2 , 0 , 0 , 0 ,,
       1       1
       0     4.5
       1       1
       0     4.5
Pier Skew, UpSta & Num, DnSta & Num=  ,81, 2 ,81, 2 , 0 , 0 , 0 ,,
       1       1
       0     4.5
       1       1
       0     4.5
BR Coef=-1 , 0 , 0 ,, 0 ,,,0.8,-1,,0,
WSPro=,,,, 1 ,,,, 0 ,,,, 0 ,,,,-1 ,-1 ,-1 , 0 , 0 , 0 , 0 , 0
BC Design=,, 0 ,, 0 ,,,,,,

Type RM Length L Ch R = 1 ,3.20    ,20,20,20
#Sta/Elev= 30
       0    3.71    47.3    3.66    47.3    2.79    48.2    2.79    48.2    1.59
    49.2    1.59    49.2     .59    53.1     .59    57.5    -.79      61    -.79
    61.5   -1.17      64   -1.57    71.6   -1.57    83.5   -1.13      84    -.72
    88.5    -.72    91.7     .67    95.6     .63    95.6    1.64    96.6    1.64
    96.6    2.84    97.5    2.84    97.5    3.71   120.2    3.76   127.3    3.88
   135.5    3.69   135.5    3.89   137.5    3.89   137.5    4.99   167.5    4.99
#Mann= 3 , 0 , 0
       0     .03       0    47.3     .03       0    97.5     .03       0
Bank Sta=47.3,97.5
Exp/Cntr=0.5,0.3

Type RM Length L Ch R = 1 ,3       ,50,50,50
#Sta/Elev= 29
       0    5.23    17.4    5.16    17.4    5.36      29    5.12    31.7    5.04
    36.5    3.94    53.5    3.83    57.6    1.76    63.3    -.79    67.3    -.79
    67.8   -1.17    69.3   -1.67    89.2   -1.47    90.2    -.82    94.7    -.82
   100.2    1.76   103.2     3.4     104    3.71   111.6    4.11   116.6    4.22
   120.9    3.92     126    3.84     126    3.64   132.5    3.81   141.9    3.63
   141.9    3.83     144    3.83     144    4.86     174    4.86
#Mann= 3 , 0 , 0
       0     .03       0    53.5     .03       0     104     .03       0
Bank Sta=53.5,104
Exp/Cntr=0.3,0.1

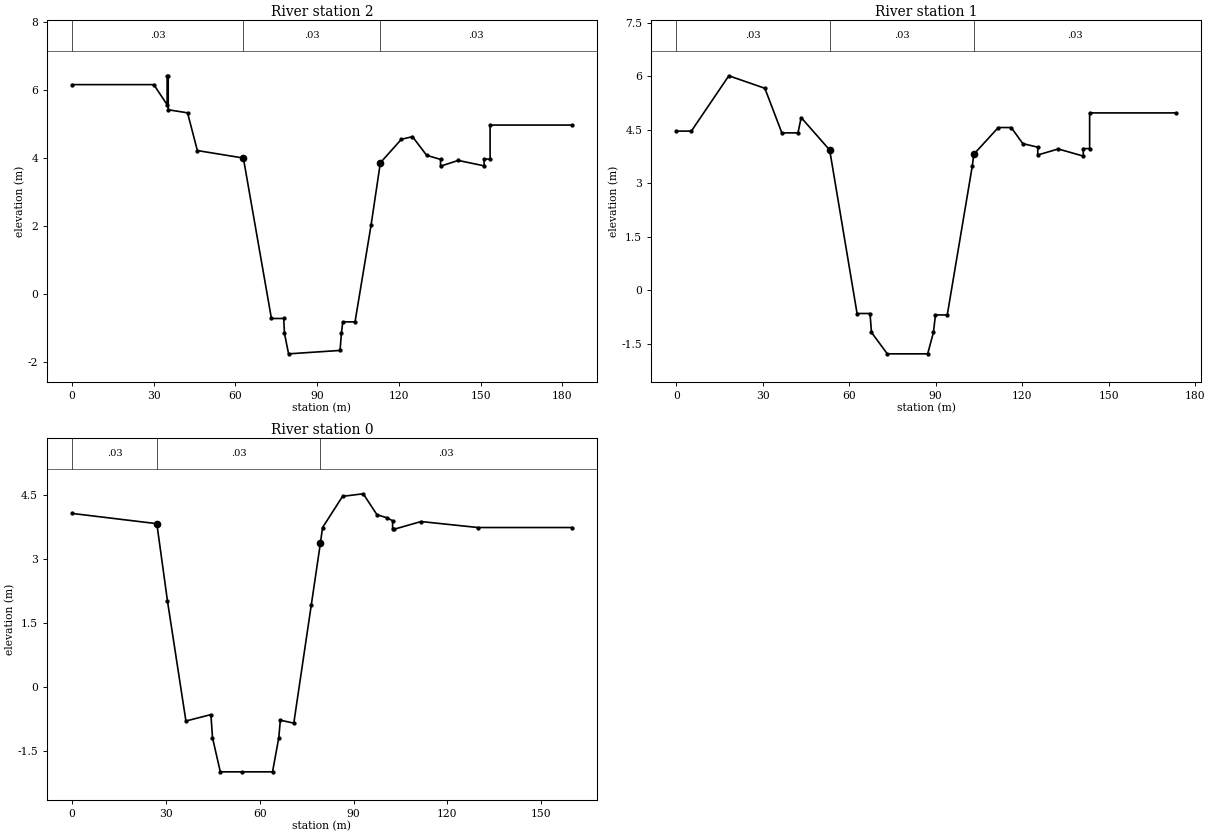
Type RM Length L Ch R = 1 ,2       ,50,50,50
#Sta/Elev= 30
       0    6.15      30    6.15    34.9    5.56    34.9    6.41    35.3    6.41
    35.3    5.41    42.4    5.32      46    4.21    62.9    3.99    73.2    -.73
    77.7    -.73      78   -1.17    79.5   -1.77    98.4   -1.67    98.9   -1.17
    99.4    -.83   103.9    -.83   109.8    2.02   113.2    3.85   120.9    4.54
     125    4.62   130.2    4.07   135.3    3.95   135.3    3.75   141.8    3.92
   151.3    3.76   151.3    3.96   153.5    3.96   153.5    4.96   183.5    4.96
#Mann= 3 , 0 , 0
       0     .03       0    62.9     .03       0   113.2     .03       0
Bank Sta=62.9,113.2
Exp/Cntr=0.3,0.1

Type RM Length L Ch R = 1 ,1       ,50,50,50
#Sta/Elev= 29
       0    4.46     5.2    4.46    18.2    6.01    30.7    5.66    36.6    4.41
    42.2    4.41    43.3    4.84    53.2    3.93    62.7    -.65    67.2    -.65
    67.7   -1.18    73.2   -1.78    87.2   -1.78    89.2   -1.18    89.9    -.69
      94    -.69   102.7    3.49   103.2    3.81   111.7    4.56   116.2    4.56
   120.2    4.11   125.4    4.01   125.4    3.79   132.5    3.96   141.2    3.76
   141.2    3.97   143.4    3.97   143.4    4.97   173.4    4.97
#Mann= 3 , 0 , 0
       0     .03       0    53.2     .03       0   103.2     .03       0
Bank Sta=53.2,103.2
Exp/Cntr=0.3,0.1

Type RM Length L Ch R = 1 ,0       ,0,0,0
#Sta/Elev= 25
       0    4.07    27.1    3.83    30.5    2.02    36.4    -.79    44.4    -.64
    44.9   -1.18    47.4   -1.98    54.4   -1.98    64.1   -1.98    66.1   -1.18
    66.6    -.77    70.9    -.84    76.5    1.93    79.4    3.37    80.1    3.74
    86.5    4.47    93.1    4.53    97.5    4.04   100.6    3.97   102.5     3.9
   102.5     3.7     103     3.7   111.6    3.88   129.8    3.74   159.8    3.74
#Mann= 3 , 0 , 0
       0     .03       0    27.1     .03       0    79.4     .03       0
Bank Sta=27.1,79.4
Exp/Cntr=0.3,0.1

Chan Stop Cuts=-1
Use User Specified Reach Order=0
User Specified Reach Order=RIVER-1         ,Reach-1