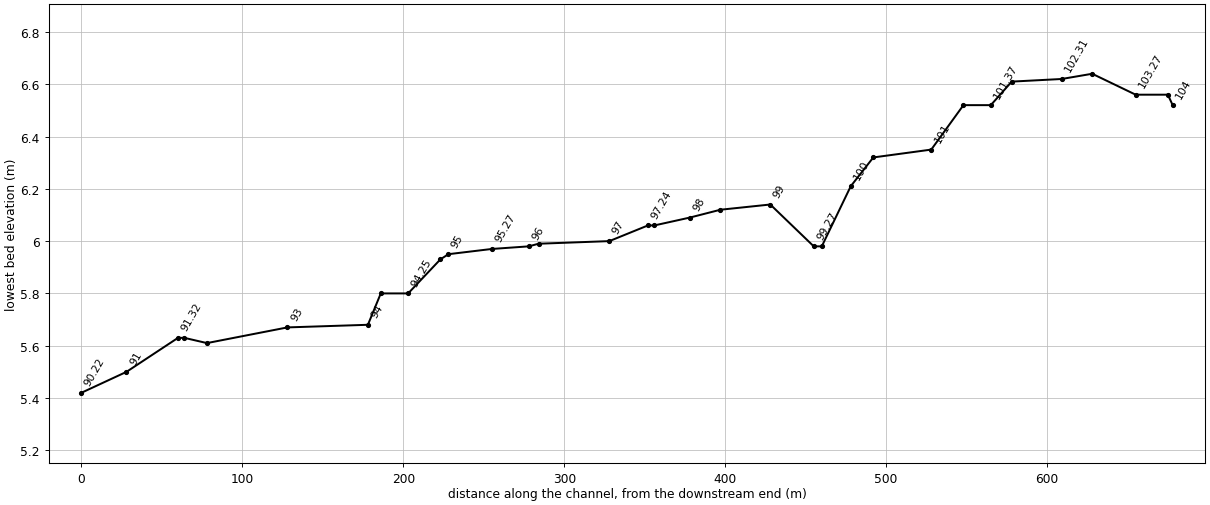
--- Hwajung.prj (project) ---

Proj Title=Hwajung
Current Plan=p03
Default Exp/Contr=0.3,0.1
SI Units
Geom File=g01
Flow File=f06
Flow File=f01
Flow File=f02
Flow File=f03
Flow File=f04
Flow File=f05
Plan File=p03
Plan File=p02
Plan File=p01
Y Axis Title=Elevation
X Axis Title(PF)=Main Channel Distance
X Axis Title(XS)=Station
BEGIN DESCRIPTION:
END DESCRIPTION:
DSS Export Rating Curves= 0
DSS Export Rating Curve Sorted= 0
DSS Export Volume Flow Curves= 0
DXF OffsetX= 0
DXF OffsetY= 0
DXF ScaleX= 1
DXF ScaleY= 10

--- Hwajung.p03 (plan) ---

Plan Title=Plan 03
Program Version=3.13
Short Identifier=Plan 03
Geom File=g01
Flow File=f06
Subcritical Flow
K Sum by GR= 0
Std Step Tol= 0.01
Critical Tol= 0.01
Num of Std Step Trials= 20
Max Error Tol= 0.3
Flow Tol Ratio= 0.001
Split Flow NTrial= 30
Split Flow Tol= 0.02
Split Flow Ratio= 0.02
Log Output Level= 0
Friction Slope Method= 1
Unsteady Friction Slope Method= 2
Unsteady Bridges Friction Slope Method= 1
Parabolic Critical Depth
Global Vel Dist= 0 , 0 , 0
Global Log Level= 0
CheckData=True
Encroach Param=-1 ,0,0, 0
Computation Interval=1HOUR
Output Interval=1HOUR
Run HTab= 0
Run UNet= 0
Run PostProcess= 0
UNET Theta= 1
UNET Theta Warmup= 1
UNET ZTol= 0.02
UNET ZSATol= 0.05
UNET MxIter= 20
UNET MaxInSteps= 0
UNET DtIC= 0
UNET DtMin= 0
UNET MaxCRTS= 20
UNET WFStab= 2
UNET SFStab= 1
UNET WFX= 1
UNET SFX= 1
UNET DSS MLevel= 4
UNET DZMax Abort= 100
UNET Convert EG Bridges=-1
UNET Use Existing IB Tables=-1
UNET Froude Reduction=False
UNET Froude Limit= 1
UNET Froude Power= 10
Instantaneous Interval=1HOUR
DSS File=dss
Write IC File= 0
Echo Input=False
Echo Output=False
Write Detailed= 0
Detailed Automatic Start=False, 10

--- Hwajung.p01 (plan) ---

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Plan Title=Plan 01
Short Identifier=1
Geom File=g01
Flow File=f01
Supercritical Flow

--- Hwajung.p02 (plan) ---

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Plan Title=Plan 02
Geom File=g01

--- Hwajung.f06 (steady flow) ---

Flow Title=96yr
Program Version=3.12
Number of Profiles= 10
Profile Names=1.58yr,10yr,20yr,30yr,50yr,80yr,100yr,200yr,box(40CMS),box(60CMS)
River Rch & RM=RIVER-1,Reach-1         ,104
      35      75      90     100     110     120     125     140     125     125
River Rch & RM=RIVER-1,Reach-1         ,101.20
      35      75      90     100     110     120     125     140      85      65
River Rch & RM=RIVER-1,Reach-1         ,87
      50     110     135     145     160     175     180     200     140     120
River Rch & RM=RIVER-1,Reach-1         ,69.22
      65     140     165     180     200     215     225     250     185     165
River Rch & RM=RIVER-1,Reach-1         ,41.02
      65     140     165     180     200     215     225     250     225     225
River Rch & RM=RIVER-1,Reach-1         ,30.38
      75     160     190     205     225     245     255     285     255     255
Boundary for River Rch & Prof#=RIVER-1,Reach-1         , 1
Up Type= 0
Dn Type= 1
Dn Known WS=0.24
Boundary for River Rch & Prof#=RIVER-1,Reach-1         , 2
Up Type= 0
Dn Type= 1
Dn Known WS=1.24
Boundary for River Rch & Prof#=RIVER-1,Reach-1         , 3
Up Type= 0
Dn Type= 1
Dn Known WS=1.51
Boundary for River Rch & Prof#=RIVER-1,Reach-1         , 4
Up Type= 0
Dn Type= 1
Dn Known WS=1.68
Boundary for River Rch & Prof#=RIVER-1,Reach-1         , 5
Up Type= 0
Dn Type= 1
Dn Known WS=1.86
Boundary for River Rch & Prof#=RIVER-1,Reach-1         , 6
Up Type= 0
Dn Type= 1
Dn Known WS=2.02
Boundary for River Rch & Prof#=RIVER-1,Reach-1         , 7
Up Type= 0
Dn Type= 1
Dn Known WS=2.05
Boundary for River Rch & Prof#=RIVER-1,Reach-1         , 8
Up Type= 0
Dn Type= 1
Dn Known WS=2.32
Boundary for River Rch & Prof#=RIVER-1,Reach-1         , 9
Up Type= 0
Dn Type= 1
Dn Known WS=2.05
Boundary for River Rch & Prof#=RIVER-1,Reach-1         , 10
Up Type= 0
Dn Type= 1
Dn Known WS=2.05
DSS Import GetInterval= 0
DSS Import GetPeak= 0
DSS Import FillOption= 0

--- Hwajung.f01 (steady flow) ---

Flow Title=Flow 01
Program Version=3.13
Number of Profiles= 1
Profile Names=plan
River Rch & RM=RIVER-1,Reach-1         ,104
     215
River Rch & RM=RIVER-1,Reach-1         ,69.22
     295
River Rch & RM=RIVER-1,Reach-1         ,27.08
     385
Boundary for River Rch & Prof#=RIVER-1,Reach-1         , 1
Up Type= 0
Dn Type= 1
Dn Known WS=2.44
DSS Import GetInterval= 0
DSS Import GetPeak= 0
DSS Import FillOption= 0

--- Hwajung.f02 (steady flow) ---

Flow Title=Flow 02
Program Version=3.11
Number of Profiles= 1
Profile Names=PF 1
River Rch & RM=RIVER-1,Reach-1         ,104
DSS Import GetInterval= 0
DSS Import GetPeak= 0
DSS Import FillOption= 0

--- Hwajung.f03 (steady flow) ---

Flow Title=Flow 03
Program Version=3.13
Number of Profiles= 1
Profile Names=PF 1
DSS Import GetInterval= 0
DSS Import GetPeak= 0
DSS Import FillOption= 0

--- Hwajung.f04 (steady flow) ---

Flow Title=Flow 04
Program Version=3.13
Number of Profiles= 1
Profile Names=96'
River Rch & RM=RIVER-1,Reach-1         ,104
     215
River Rch & RM=RIVER-1,Reach-1         ,69.21
     295
River Rch & RM=RIVER-1,Reach-1         ,30.379
     385
Boundary for River Rch & Prof#=RIVER-1,Reach-1         , 1
Up Type= 3
Up Slope=0.001999
Dn Type= 1
Dn Known WS=2.31
DSS Import GetInterval= 0
DSS Import GetPeak= 0
DSS Import FillOption= 0

--- Hwajung.f05 (steady flow) ---

Flow Title=Flow 05
Program Version=3.13
Number of Profiles= 1
Profile Names=PF 1
River Rch & RM=RIVER-1,Reach-1         ,104
     215
River Rch & RM=RIVER-1,Reach-1         ,69
     295
River Rch & RM=RIVER-1,Reach-1         ,30
     385
Boundary for River Rch & Prof#=RIVER-1,Reach-1         , 1
Up Type= 0
Dn Type= 1
Dn Known WS=2.31
DSS Import GetInterval= 0
DSS Import GetPeak= 0
DSS Import FillOption= 0

--- Hwajung.g01 (geometry) ---

Geom Title=Geom 01
Program Version=3.12

River Reach=RIVER-1         ,Reach-1
Reach XY= 2
              .5             .95              .5             .05

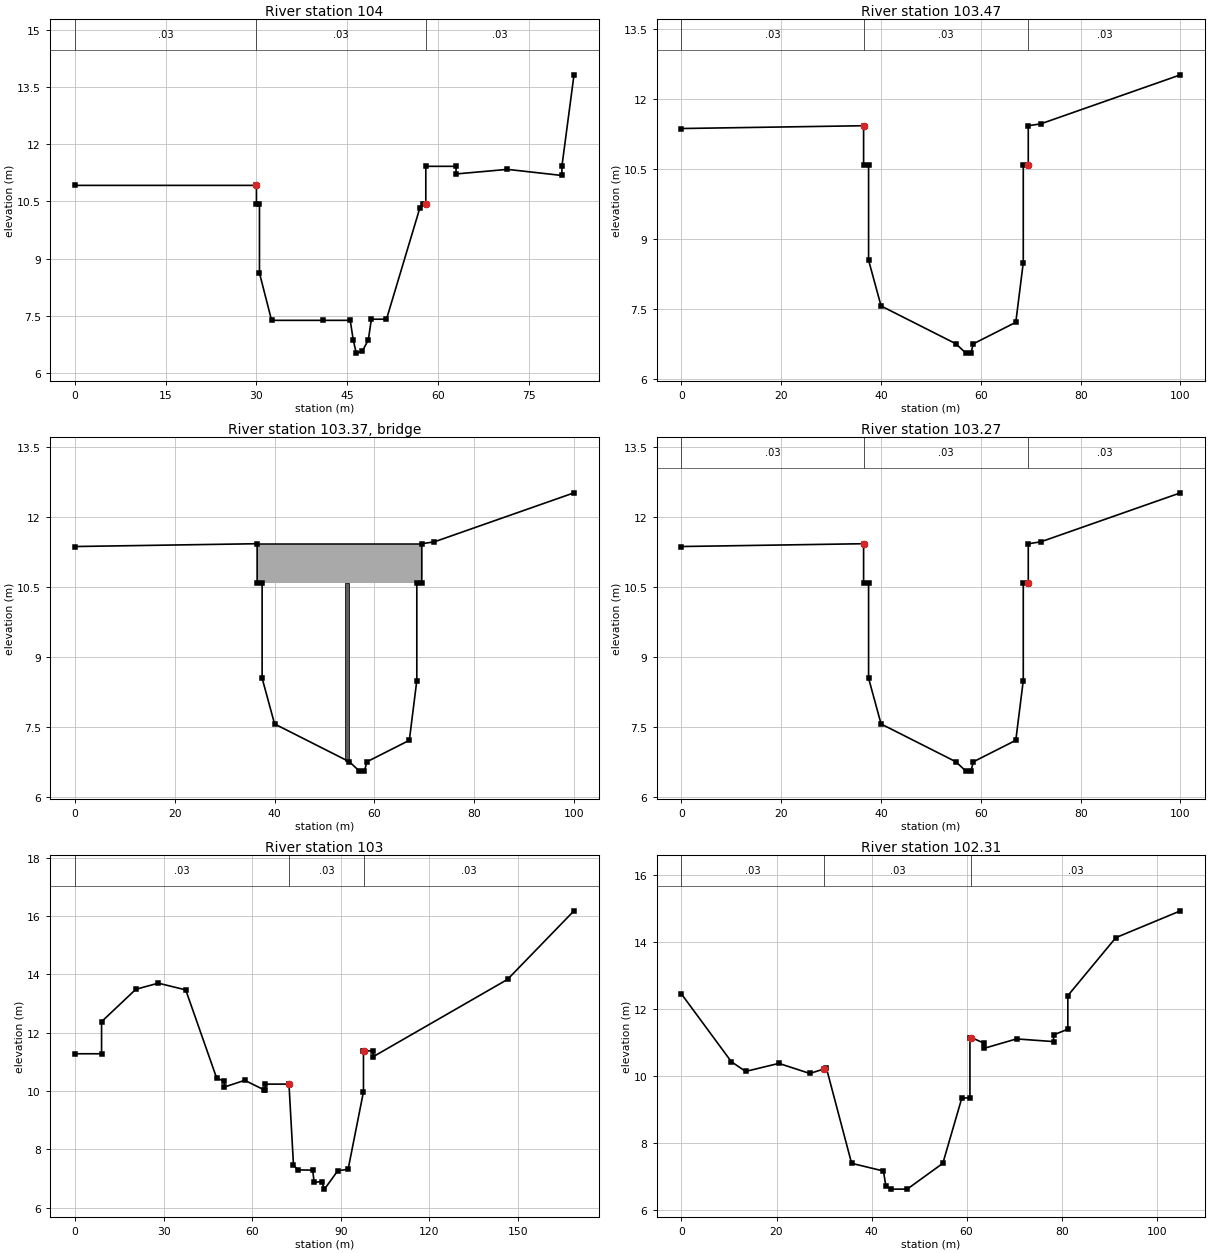
Type RM Length L Ch R = 1 ,104     ,3,3,3
#Sta/Elev= 24
       0   10.92      30   10.92      30   10.42    30.5   10.42    30.5    8.62
    32.5    7.38      41    7.38    45.5    7.38      46    6.87    46.5    6.52
    47.5    6.57    48.5    6.87      49    7.41    51.5    7.41      57   10.32
    57.5   10.42      58   10.42      58   11.42      63   11.42      63   11.22
    71.5   11.34    80.5   11.18    80.5   11.42    82.5   13.82
#Mann= 3 , 0 , 0
       0     .03       0      30     .03       0      58     .03       0
Bank Sta=30,58
Exp/Cntr=0.3,0.1

Type RM Length L Ch R = 1 ,103.47  ,20,20,20
#Sta/Elev= 17
       0   11.37    36.5   11.43    36.5   10.58    37.5   10.58    37.5    8.55
      40    7.57      55    6.76      57    6.56      58    6.56    58.5    6.76
      67    7.22    68.5     8.5    68.5   10.58    69.5   10.58    69.5   11.43
      72   11.47     100   12.52
#Mann= 3 , 0 , 0
       0     .03       0    36.5     .03       0    69.5     .03       0
Bank Sta=36.5,69.5
Exp/Cntr=0.5,0.3

Type RM Length L Ch R = 3 ,103.37  ,,,
BEGIN DESCRIPTION:
È­Á¤8±³
END DESCRIPTION:
Bridge Culvert--1,0,-1,-1, 0
Deck Dist Width WeirC Skew NumUp NumDn MinLoCord MaxHiCord MaxSubmerge Is_Ogee
0.1,19,1.44,0, 2, 2, , , 0.95, 0, 0,0,,
    36.5    69.5
   11.43   11.43
   10.58   10.58
    36.5    69.5
   11.43   11.43
   10.58   10.58
Pier Skew, UpSta & Num, DnSta & Num=  ,54.5, 2 ,54.5, 2 , 0 , 0 , 0 ,,
      .7      .7
       5      11
      .7      .7
       5      11
BR Coef=-1 , 0 , 0 ,, 0 ,,,0.8,-1,,0,
WSPro=,,,, 1 ,,,, 0 ,,,, 0 ,,,,-1 ,-1 ,-1 , 0 , 0 , 0 , 0 , 0
BC Design=,, 0 ,, 0 ,,,,,,

Type RM Length L Ch R = 1 ,103.27  ,27,27,27
#Sta/Elev= 17
       0   11.37    36.5   11.43    36.5   10.58    37.5   10.58    37.5    8.55
      40    7.57      55    6.76      57    6.56      58    6.56    58.5    6.76
      67    7.22    68.5     8.5    68.5   10.58    69.5   10.58    69.5   11.43
      72   11.47     100   12.52
#Mann= 3 , 0 , 0
       0     .03       0    36.5     .03       0    69.5     .03       0
Bank Sta=36.5,69.5
Exp/Cntr=0.5,0.3

Type RM Length L Ch R = 1 ,103     ,19,19,19
#Sta/Elev= 30
       0   11.28       9   11.28       9   12.38    20.6   13.49    28.2    13.7
    37.5   13.47      48   10.44    50.6   10.34    50.6   10.14    57.5   10.37
    64.1   10.04    64.5   10.04    64.5   10.24   72.33   10.24   72.47   10.24
      74    7.46    75.5     7.3    80.5    7.29      81    6.87    83.5     6.9
    84.5    6.64      89    7.27    92.5    7.32    97.7    9.98    97.7   11.38
      98   11.38     101   11.38     101   11.18   146.5   13.83     169   16.18
#Mann= 3 , 0 , 0
       0     .03       0   72.33     .03       0      98     .03       0
Bank Sta=72.33,98
Exp/Cntr=0.3,0.1

Type RM Length L Ch R = 1 ,102.31  ,31,31,31
#Sta/Elev= 26
       0   12.44    10.5   10.42    13.5   10.13    20.5   10.37      27   10.07
    29.9  10.199    30.5   10.23    35.8    7.39    42.5    7.16      43    6.72
      44    6.62    47.5    6.62      55    7.39      59    9.34    60.7    9.34
    60.7   11.14      61   11.14    63.7   10.97    63.7   10.82    70.5    11.1
    78.3   11.02    78.3   11.22    81.3   11.39    81.3   12.39    91.4   14.12
     105   14.92
#Mann= 3 , 0 , 0
       0     .03       0    29.9     .03       0      61     .03       0
Bank Sta=29.9,61
Exp/Cntr=0.3,0.1

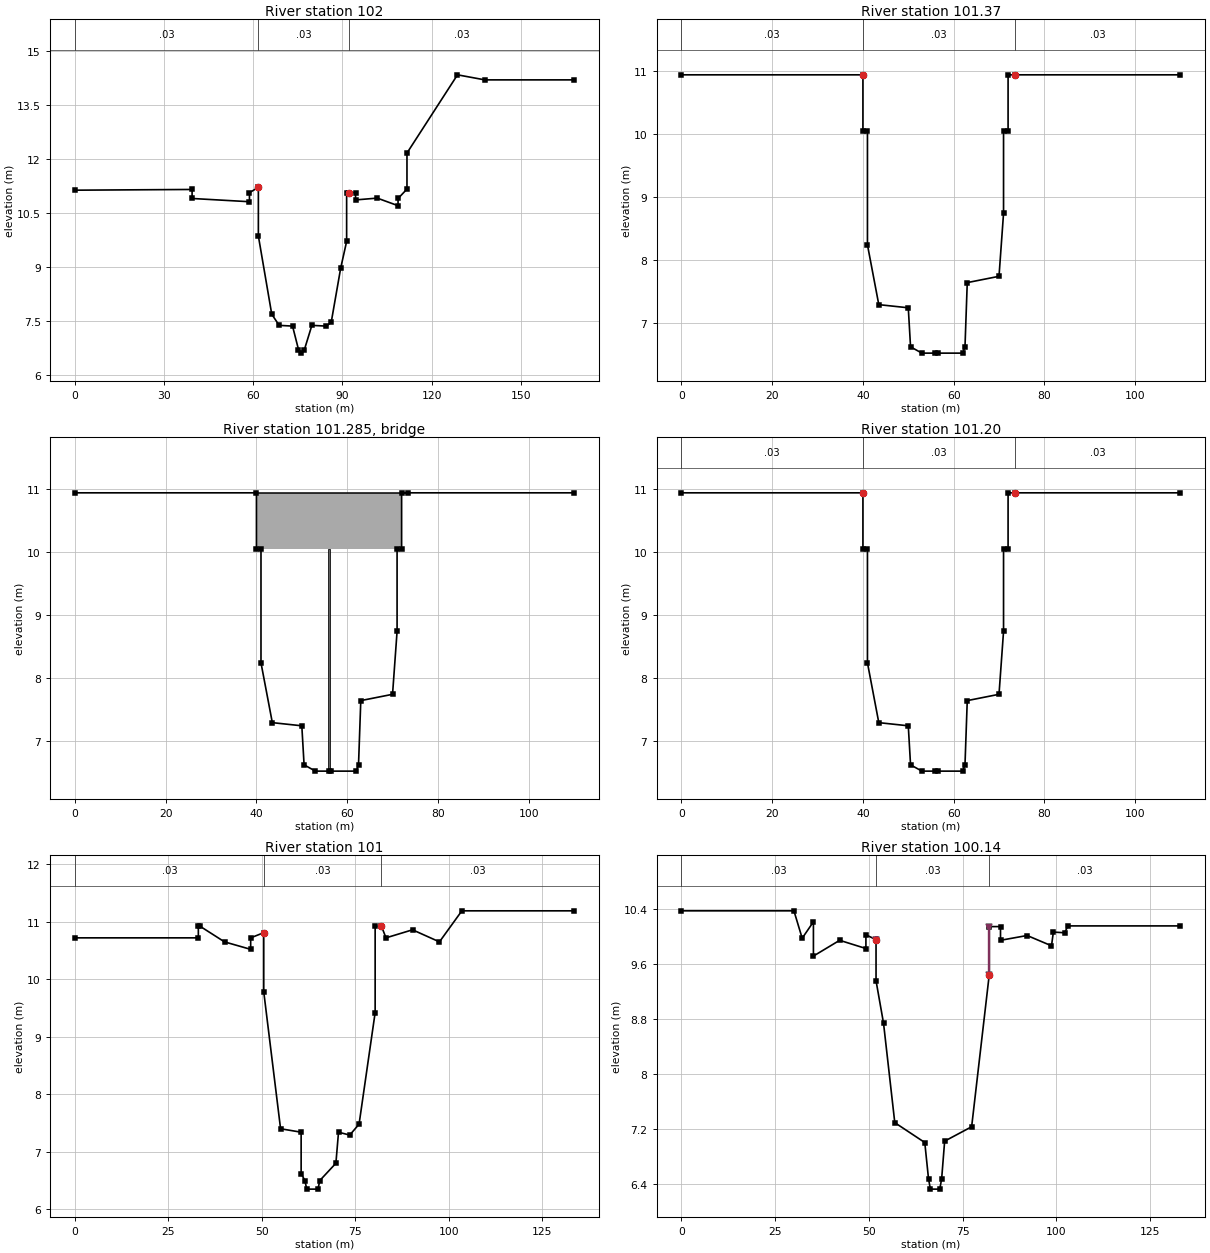
Type RM Length L Ch R = 1 ,102     ,13,13,13
#Sta/Elev= 30
       0   11.13    39.4   11.15    39.4    10.9    58.7   10.81    58.7   11.06
    61.7   11.21    61.7    9.86    66.2    7.69    68.7    7.38    73.2    7.36
    75.2    6.71    76.2    6.61    77.2    6.71    79.7    7.38    84.5    7.36
    86.2    7.46    89.4    8.97    91.4    9.71    91.4   11.06    92.2   11.06
    94.4   11.06    94.4   10.86   101.7   10.91   108.7    10.7   108.7    10.9
   111.7   11.16   111.7   12.16   128.7   14.33   137.9   14.19   167.9   14.19
#Mann= 3 , 0 , 0
       0     .03       0    61.7     .03       0    92.2     .03       0
Bank Sta=61.7,92.2
Exp/Cntr=0.3,0.1

Type RM Length L Ch R = 1 ,101.37  ,17,17,17
#Sta/Elev= 21
       0   10.94      40   10.94      40   10.04      41   10.04      41    8.24
    43.5    7.29      50    7.24    50.5    6.62      53    6.52      56    6.52
    56.5    6.52      62    6.52    62.5    6.62      63    7.64      70    7.74
      71    8.74      71   10.04      72   10.04      72   10.94    73.5   10.94
     110   10.94
#Mann= 3 , 0 , 0
       0     .03       0      40     .03       0    73.5     .03       0
Bank Sta=40,73.5
Exp/Cntr=0.5,0.3

Type RM Length L Ch R = 3 ,101.285 ,,,
BEGIN DESCRIPTION:
È­Á¤7±³
END DESCRIPTION:
Bridge Culvert--1,0,-1,-1, 0
Deck Dist Width WeirC Skew NumUp NumDn MinLoCord MaxHiCord MaxSubmerge Is_Ogee
0.1,16,1.44,0, 2, 2, , , 0.95, 0, 0,0,,
      40    73.5
   10.94   10.94
   10.04   10.04
      40    73.5
   10.94   10.94
   10.04   10.04
Pier Skew, UpSta & Num, DnSta & Num=  ,56, 2 ,56, 2 , 0 , 0 , 0 ,,
      .6      .6
       5      11
      .6      .6
       5      11
BR Coef=-1 , 0 , 0 ,, 0 ,,,0.8,-1,,0,
WSPro=,,,, 1 ,,,, 0 ,,,, 0 ,,,,-1 ,-1 ,-1 , 0 , 0 , 0 , 0 , 0
BC Design=,, 0 ,, 0 ,,,,,,

Type RM Length L Ch R = 1 ,101.20  ,20,20,20
#Sta/Elev= 21
       0   10.94      40   10.94      40   10.04      41   10.04      41    8.24
    43.5    7.29      50    7.24    50.5    6.62      53    6.52      56    6.52
    56.5    6.52      62    6.52    62.5    6.62      63    7.64      70    7.74
      71    8.74      71   10.04      72   10.04      72   10.94    73.5   10.94
     110   10.94
#Mann= 3 , 0 , 0
       0     .03       0      40     .03       0    73.5     .03       0
Bank Sta=40,73.5
Exp/Cntr=0.5,0.3

Type RM Length L Ch R = 1 ,101     ,36,36,36
#Sta/Elev= 28
       0   10.72      33   10.72      33   10.92    33.5   10.92      40   10.65
      47   10.52      47   10.72    50.5   10.81    50.5    9.78      55     7.4
    60.5    7.34    60.5    6.62    61.5     6.5      62    6.35      65    6.35
    65.5     6.5    69.8     6.8    70.5    7.34    73.5    7.29      76    7.48
    80.3    9.42    80.3   10.92      82   10.92    83.2   10.72    90.3   10.86
    97.5   10.65   103.5   11.19   133.5   11.19
#Mann= 3 , 0 , 0
       0     .03       0    50.5     .03       0      82     .03       0
Bank Sta=50.5,82
Exp/Cntr=0.3,0.1

Type RM Length L Ch R = 1 ,100.14  ,14,14,14
#Sta/Elev= 30
       0   10.38      30   10.38    32.2    9.98    35.2   10.22    35.2    9.72
    42.2    9.95    49.2    9.83    49.2   10.03   51.85   9.961    51.9    9.96
    51.9    9.36    53.9    8.74    56.9    7.29    64.9       7    65.9    6.47
    66.4    6.32    68.9    6.32    69.4    6.47    70.2    7.02    77.4    7.23
    82.1    9.45    82.1   10.15    85.1   10.15    85.1    9.95    92.2   10.02
    98.7    9.87    99.2   10.07   102.2   10.06   103.1   10.16   133.1   10.16
#Mann= 3 , 0 , 0
       0     .03       0   51.85     .03       0    82.1     .03       0
Levee=-1,51.85,9.961,-1,82.1,10.15,,
Bank Sta=51.85,82.1
Exp/Cntr=0.3,0.1

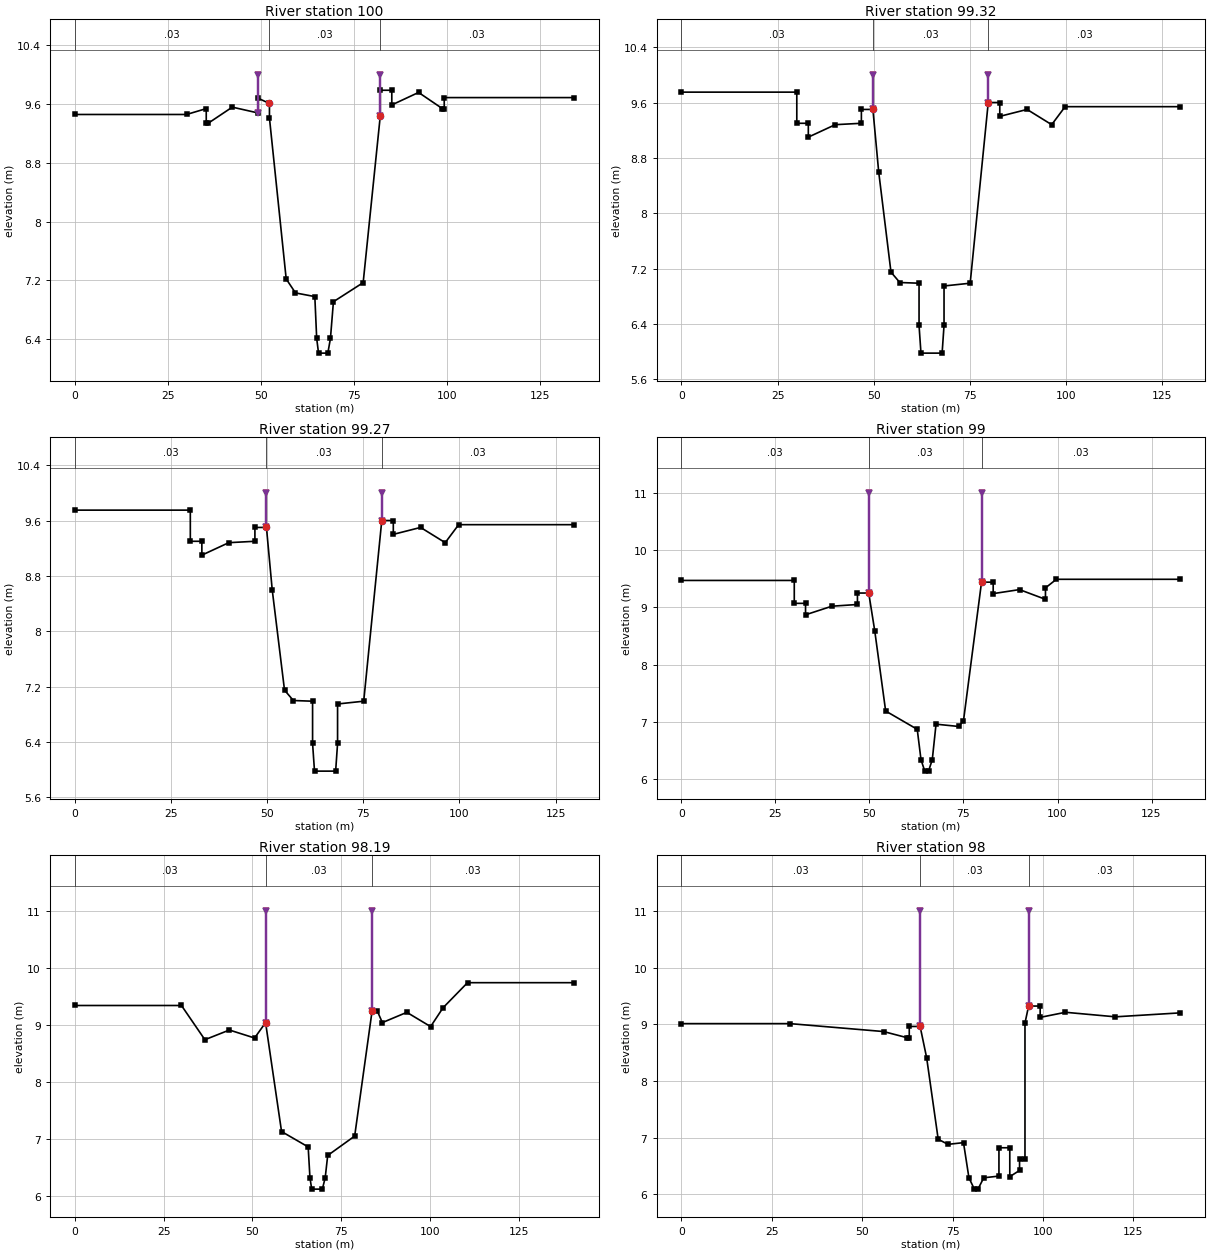
Type RM Length L Ch R = 1 ,100     ,18,18,18
#Sta/Elev= 28
       0    9.46      30    9.46    35.3    9.54    35.3    9.34    35.8    9.34
    42.3    9.56    49.3    9.48    49.3    9.68    52.3    9.61    52.3    9.41
    56.8    7.22    59.3    7.03    64.5    6.98      65    6.41    65.5    6.21
      68    6.21    68.7    6.41    69.5    6.91    77.5    7.17    82.1    9.44
    82.1    9.79    85.2    9.79    85.2    9.59    92.4    9.76    98.8    9.54
    99.3    9.54    99.3    9.69   134.2    9.69
#Mann= 3 , 0 , 0
       0     .03       0    52.3     .03       0    82.1     .03       0
Levee=-1,49.3,10,-1,82.1,10,,
Bank Sta=52.3,82.1
Exp/Cntr=0.3,0.1

Type RM Length L Ch R = 1 ,99.32   ,5,5,5
#Sta/Elev= 26
       0    9.75      30    9.75      30     9.3      33     9.3      33     9.1
      40    9.28    46.8     9.3    46.8     9.5    49.8     9.5    51.3     8.6
    54.5    7.15    56.8       7    61.8    6.99    61.8    6.38    62.3    5.98
    67.8    5.98    68.3    6.38    68.3    6.95    75.1    6.99    79.8     9.6
    82.8     9.6    82.8     9.4    89.9     9.5    96.3    9.28    99.8    9.54
   129.8    9.54
#Mann= 3 , 0 , 0
       0     .03       0    49.8     .03       0    79.8     .03       0
Levee=-1,49.8,10,-1,79.8,10,,
Bank Sta=49.8,79.8
Exp/Cntr=0.3,0.1

Type RM Length L Ch R = 1 ,99.27   ,27,27,27
#Sta/Elev= 26
       0    9.75      30    9.75      30     9.3      33     9.3      33     9.1
      40    9.28    46.8     9.3    46.8     9.5    49.8     9.5    51.3     8.6
    54.5    7.15    56.8       7    61.8    6.99    61.8    6.38    62.3    5.98
    67.8    5.98    68.3    6.38    68.3    6.95    75.1    6.99    79.8     9.6
    82.8     9.6    82.8     9.4    89.9     9.5    96.3    9.28    99.8    9.54
   129.8    9.54
#Mann= 3 , 0 , 0
       0     .03       0    49.8     .03       0    79.8     .03       0
Levee=-1,49.8,10,-1,79.8,10,,
Bank Sta=49.8,79.8
Exp/Cntr=0.3,0.1

Type RM Length L Ch R = 1 ,99      ,31,31,31
#Sta/Elev= 27
       0    9.47      30    9.47      30    9.07      33    9.07      33    8.87
      40    9.02    46.8    9.05    46.8    9.25    49.8    9.25    51.4    8.59
    54.3    7.19    62.7    6.87    63.7    6.34    64.7    6.14    65.7    6.14
    66.7    6.34    67.7    6.96    73.7    6.92      75    7.02    79.8    9.44
    82.9    9.44    82.9    9.24    89.9    9.31    96.8    9.14    96.8    9.34
    99.7    9.49   132.7    9.49
#Mann= 3 , 0 , 0
       0     .03       0    49.8     .03       0    79.8     .03       0
Levee=-1,49.8,11,-1,79.8,11,,
Bank Sta=49.8,79.8
Exp/Cntr=0.3,0.1

Type RM Length L Ch R = 1 ,98.19   ,19,19,19
#Sta/Elev= 22
       0    9.34      30    9.34    36.6    8.74    43.5    8.91    50.6    8.77
    53.7    9.04    58.2    7.13    65.7    6.86    66.2    6.32    66.7    6.12
    69.7    6.12    70.5    6.32    71.2    6.71    78.8    7.05    83.7    9.24
    85.2    9.24    86.6    9.04    93.5    9.22   100.2    8.97   103.7     9.3
   110.6    9.74   140.6    9.74
#Mann= 3 , 0 , 0
       0     .03       0    53.7     .03       0    83.7     .03       0
Levee=-1,53.7,11,-1,83.7,11,,
Bank Sta=53.7,83.7
Exp/Cntr=0.3,0.1

Type RM Length L Ch R = 1 ,98      ,22,22,22
#Sta/Elev= 29
       0    9.01      30    9.01    55.9    8.87    62.5    8.76      63    8.76
      63    8.96      66    8.96    67.8    8.41      71    6.97    73.7    6.88
      78    6.91    79.5    6.29      81    6.09      82    6.09    83.6    6.29
    87.8    6.32    87.8    6.82    90.8    6.82    90.8    6.31    93.5    6.42
    93.5    6.62      95    6.62      95    9.02      96    9.32    99.2    9.32
    99.2    9.12   106.2    9.21     120    9.13     138     9.2
#Mann= 3 , 0 , 0
       0     .03       0      66     .03       0      96     .03       0
Levee=-1,66,11,-1,96,11,,
Bank Sta=66,96
Exp/Cntr=0.3,0.1

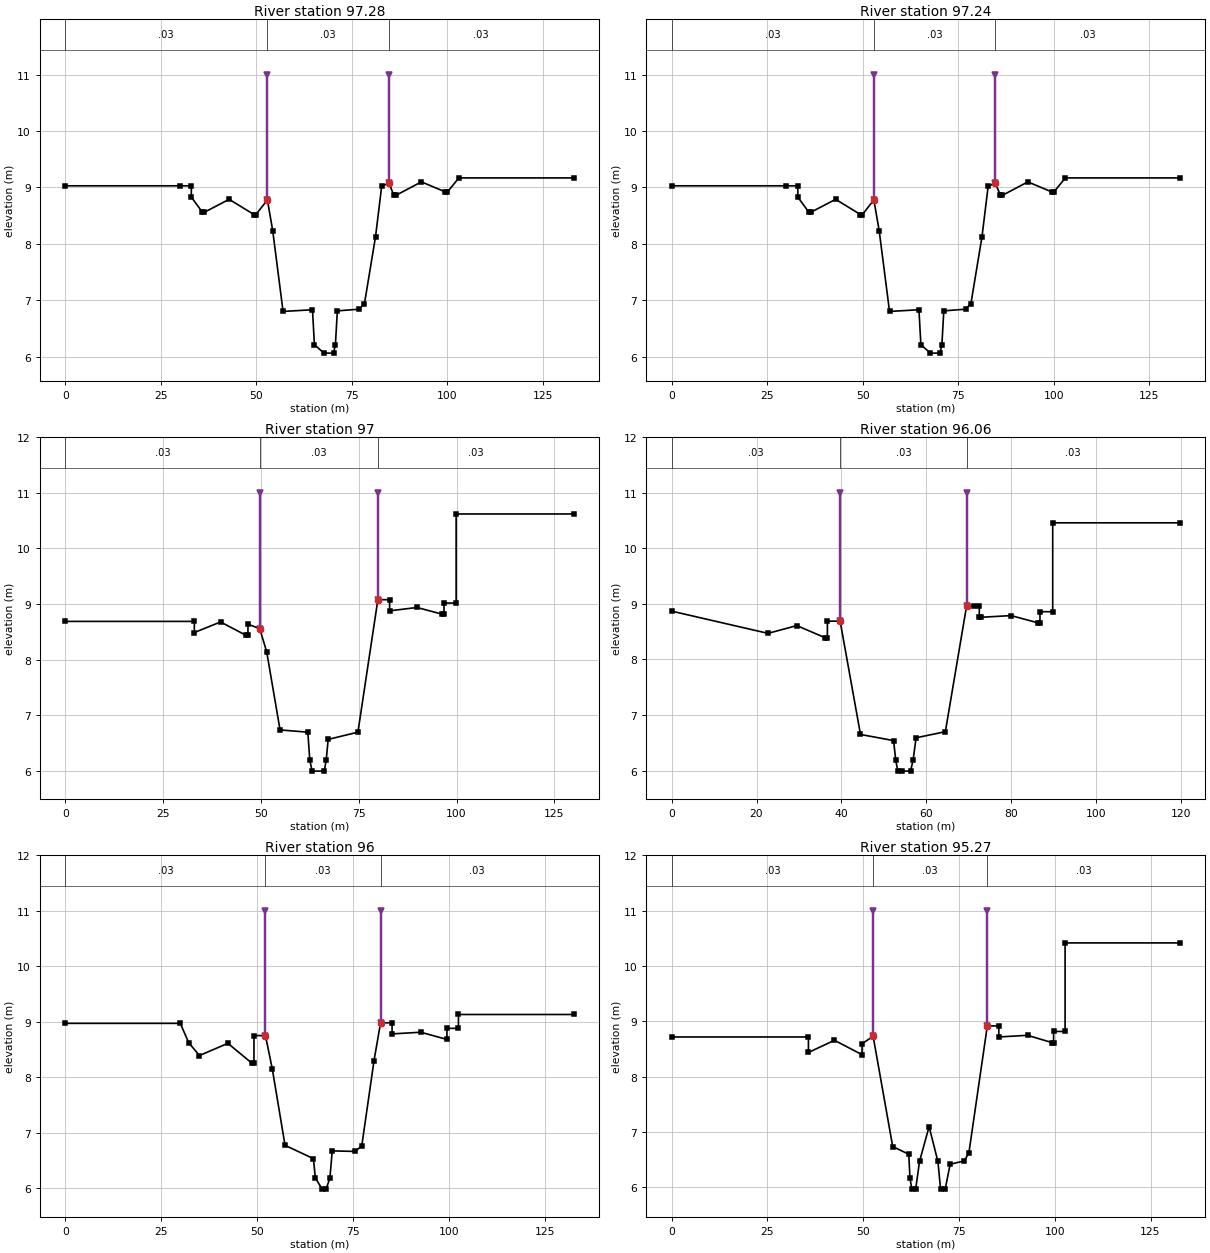
Type RM Length L Ch R = 1 ,97.28   ,4,4,4
#Sta/Elev= 30
       0    9.03      30    9.03      33    9.03      33    8.83    35.9    8.56
    36.4    8.56    42.9    8.79    49.4    8.52    49.9    8.52    52.9    8.78
    54.3    8.23      57     6.8    64.7    6.83    65.2    6.21    67.7    6.06
    70.2    6.06    70.7    6.21    71.2    6.81    76.9    6.84    78.3    6.94
    81.2    8.13    82.8    9.02    84.7    9.08      86    8.86    86.5    8.86
    93.2     9.1    99.5    8.92     100    8.92     103    9.17     133    9.17
#Mann= 3 , 0 , 0
       0     .03       0    52.9     .03       0    84.7     .03       0
Levee=-1,52.9,11,-1,84.7,11,,
Bank Sta=52.9,84.7
Exp/Cntr=0.3,0.1

Type RM Length L Ch R = 1 ,97.24   ,24,24,24
#Sta/Elev= 30
       0    9.03      30    9.03      33    9.03      33    8.83    35.9    8.56
    36.4    8.56    42.9    8.79    49.4    8.52    49.9    8.52    52.9    8.78
    54.3    8.23      57     6.8    64.7    6.83    65.2    6.21    67.7    6.06
    70.2    6.06    70.7    6.21    71.2    6.81    76.9    6.84    78.3    6.94
    81.2    8.13    82.8    9.02    84.7    9.08      86    8.86    86.5    8.86
    93.2     9.1    99.5    8.92     100    8.92     103    9.17     133    9.17
#Mann= 3 , 0 , 0
       0     .03       0    52.9     .03       0    84.7     .03       0
Levee=-1,52.9,11,-1,84.7,11,,
Bank Sta=52.9,84.7
Exp/Cntr=0.3,0.1

Type RM Length L Ch R = 1 ,97      ,44,44,44
#Sta/Elev= 27
       0    8.69      33    8.69      33    8.49    39.7    8.68    46.2    8.44
    46.7    8.44    46.7    8.64    49.7    8.56    51.5    8.14    54.9    6.74
      62     6.7    62.5     6.2    63.1       6    66.2       6    66.7     6.2
    67.2    6.57    74.8     6.7    79.9    9.08    82.9    9.08    82.9    8.88
    89.9    8.94    96.3    8.82    96.8    8.82    96.8    9.02    99.9    9.02
    99.9   10.62   129.9   10.62
#Mann= 3 , 0 , 0
       0     .03       0    49.7     .03       0    79.9     .03       0
Levee=-1,49.7,11,-1,79.9,11,,
Bank Sta=49.7,79.9
Exp/Cntr=0.3,0.1

Type RM Length L Ch R = 1 ,96.06   ,6,6,6
#Sta/Elev= 28
       0    8.87    22.7    8.47    29.5    8.61    36.2    8.39    36.7    8.39
    36.7    8.69    39.7    8.69    44.5    6.65    52.3    6.54    52.8    6.19
    53.3    5.99    54.3    5.99    56.3    5.99    56.9    6.19    57.6    6.59
    64.5     6.7    69.5    8.96    71.3    8.96    72.5    8.96    72.5    8.76
      73    8.76      80    8.79    86.3    8.66    86.8    8.66    86.8    8.86
    89.8    8.86    89.8   10.46   119.8   10.46
#Mann= 3 , 0 , 0
       0     .03       0    39.7     .03       0    69.5     .03       0
Levee=-1,39.7,11,-1,69.5,11,,
Bank Sta=39.7,69.5
Exp/Cntr=0.3,0.1

Type RM Length L Ch R = 1 ,96      ,23,23,23
#Sta/Elev= 29
       0    8.97      30    8.97    32.2    8.62      35    8.39    42.4    8.61
    48.7    8.25    49.2    8.25    49.2    8.75    52.2    8.75      54    8.14
    57.3    6.77    64.7    6.53    65.2    6.18      67    5.98      68    5.98
      69    6.18    69.6    6.67    75.6    6.66    77.3    6.76    80.5     8.3
    82.2    8.98    85.2    8.98    85.2    8.78    92.7    8.81    99.5    8.68
    99.5    8.88   102.5    8.88   102.5    9.13   132.5    9.13
#Mann= 3 , 0 , 0
       0     .03       0    52.2     .03       0    82.2     .03       0
Levee=-1,52.2,11,-1,82.2,11,,
Bank Sta=52.2,82.2
Exp/Cntr=0.3,0.1

Type RM Length L Ch R = 1 ,95.27   ,27,27,27
#Sta/Elev= 30
       0    8.72    35.7    8.72    35.7    8.44    42.5    8.66    49.7     8.4
    49.7     8.6    52.6    8.73    57.7    6.74    61.9     6.6    62.2    6.17
    62.7    5.97    63.7    5.97    64.7    6.47    67.2     7.1    69.5    6.47
    70.2    5.97    71.4    5.97    72.7    6.42    76.4    6.48    77.6    6.63
    82.4    8.92    85.4    8.92    85.4    8.72    92.9    8.75    99.2    8.62
    99.7    8.62    99.7    8.82   102.7    8.82   102.7   10.42   132.7   10.42
#Mann= 3 , 0 , 0
       0     .03       0    52.6     .03       0    82.4     .03       0
Levee=-1,52.6,11,-1,82.4,11,,
Bank Sta=52.6,82.4
Exp/Cntr=0.3,0.1

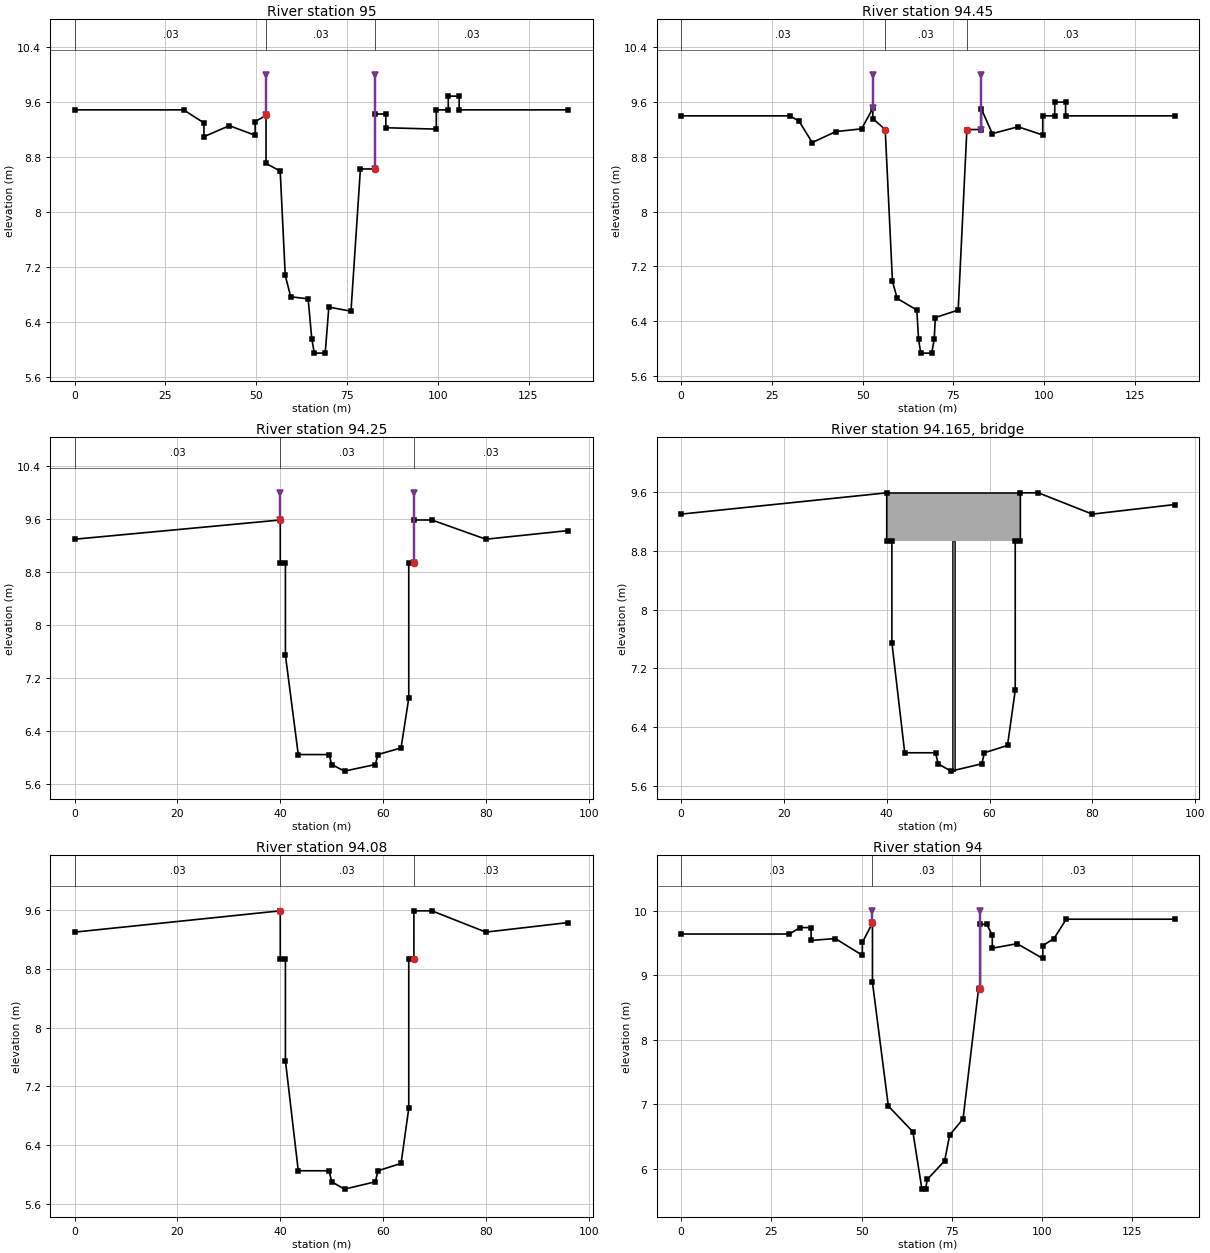
Type RM Length L Ch R = 1 ,95      ,5,5,5
#Sta/Elev= 30
       0    9.49      30    9.49    35.6     9.3    35.6     9.1    42.6    9.26
    49.7    9.12    49.7    9.32    52.7    9.41    52.7    8.71    56.6     8.6
      58    7.08    59.5    6.77    64.3    6.74    65.3    6.16      66    5.95
      69    5.95      70    6.62    76.1    6.56    78.7    8.63    82.7    8.63
    82.7    9.43    85.7    9.43    85.7    9.23    99.6    9.21    99.6    9.49
   102.9    9.49   102.9    9.69   105.9    9.69   105.9    9.49   135.9    9.49
#Mann= 3 , 0 , 0
       0     .03       0    52.7     .03       0    82.7     .03       0
Levee=-1,52.7,10,-1,82.7,10,,
Bank Sta=52.7,82.7
Exp/Cntr=0.3,0.1

Type RM Length L Ch R = 1 ,94.45   ,20,20,20
#Sta/Elev= 30
       0     9.4      30     9.4    32.5    9.32    36.1    9.01    42.6    9.17
    49.7    9.21    52.8    9.51    52.8    9.36    56.2     9.2    58.2    6.98
    59.5    6.73    64.9    6.56    65.4    6.13      66    5.93      69    5.93
    69.7    6.13      70    6.45    76.3    6.56    78.7     9.2    82.7     9.2
    82.7     9.5    85.7    9.14    92.8    9.24    99.6    9.12    99.6     9.4
   102.9     9.4   102.9     9.6   105.9     9.6   105.9     9.4   135.9     9.4
#Mann= 3 , 0 , 0
       0     .03       0    56.2     .03       0    78.7     .03       0
Levee=-1,52.8,10,-1,82.7,10,,
Bank Sta=56.2,78.7
Exp/Cntr=0.3,0.1

Type RM Length L Ch R = 1 ,94.25   ,17,17,17
#Sta/Elev= 19
       0     9.3      40    9.59      40    8.94      41    8.94      41    7.55
    43.5    6.05    49.5    6.05      50     5.9    52.5     5.8    58.5     5.9
      59    6.05    63.5    6.15      65     6.9      65    8.94      66    8.94
      66    9.59    69.5    9.59      80     9.3      96    9.43
#Mann= 3 , 0 , 0
       0     .03       0      40     .03       0      66     .03       0
Levee=-1,40,10,-1,66,10,,
Bank Sta=40,66
Exp/Cntr=0.5,0.3

Type RM Length L Ch R = 3 ,94.165  ,,,
BEGIN DESCRIPTION:
È­Á¤6±³
END DESCRIPTION:
Bridge Culvert--1,0,-1,-1, 0
Deck Dist Width WeirC Skew NumUp NumDn MinLoCord MaxHiCord MaxSubmerge Is_Ogee
0.1,15,1.44,0, 2, 2, , , 0.95, 0, 0,0,,
      40      66
    9.59    9.59
    8.94    8.94
      40      66
    9.59    9.59
    8.94    8.94
Pier Skew, UpSta & Num, DnSta & Num=  ,53, 2 ,53, 2 , 0 , 0 , 0 ,,
      .6      .6
       5      10
      .6      .6
       5      10
BR Coef=-1 , 0 , 0 ,, 0 ,,,0.8,-1,,0,
WSPro=,,,, 1 ,,,, 0 ,,,, 0 ,,,,-1 ,-1 ,-1 , 0 , 0 , 0 , 0 , 0
BC Design=,, 0 ,, 0 ,,,,,,

Type RM Length L Ch R = 1 ,94.08   ,8,8,8
#Sta/Elev= 19
       0     9.3      40    9.59      40    8.94      41    8.94      41    7.55
    43.5    6.05    49.5    6.05      50     5.9    52.5     5.8    58.5     5.9
      59    6.05    63.5    6.15      65     6.9      65    8.94      66    8.94
      66    9.59    69.5    9.59      80     9.3      96    9.43
#Mann= 3 , 0 , 0
       0     .03       0      40     .03       0      66     .03       0
Bank Sta=40,66
Exp/Cntr=0.5,0.3

Type RM Length L Ch R = 1 ,94      ,50,50,50
#Sta/Elev= 30
       0    9.64      30    9.64    32.9    9.74      36    9.74      36    9.54
    42.7    9.57    50.2    9.31    50.2    9.51      53    9.81      53    8.89
    57.4    6.97    64.2    6.57    66.7    5.68    67.7    5.68    68.2    5.83
      73    6.12    74.4    6.52    78.1    6.77    82.4    8.79    82.9    8.79
    82.9    9.79    84.7    9.79    86.2    9.62    86.2    9.42    93.1    9.49
   100.2    9.26   100.2    9.46   103.3    9.57   106.7    9.87   136.7    9.87
#Mann= 3 , 0 , 0
       0     .03       0      53     .03       0    82.9     .03       0
Levee=-1,53,10,-1,82.9,10,,
Bank Sta=53,82.9
Exp/Cntr=0.3,0.1

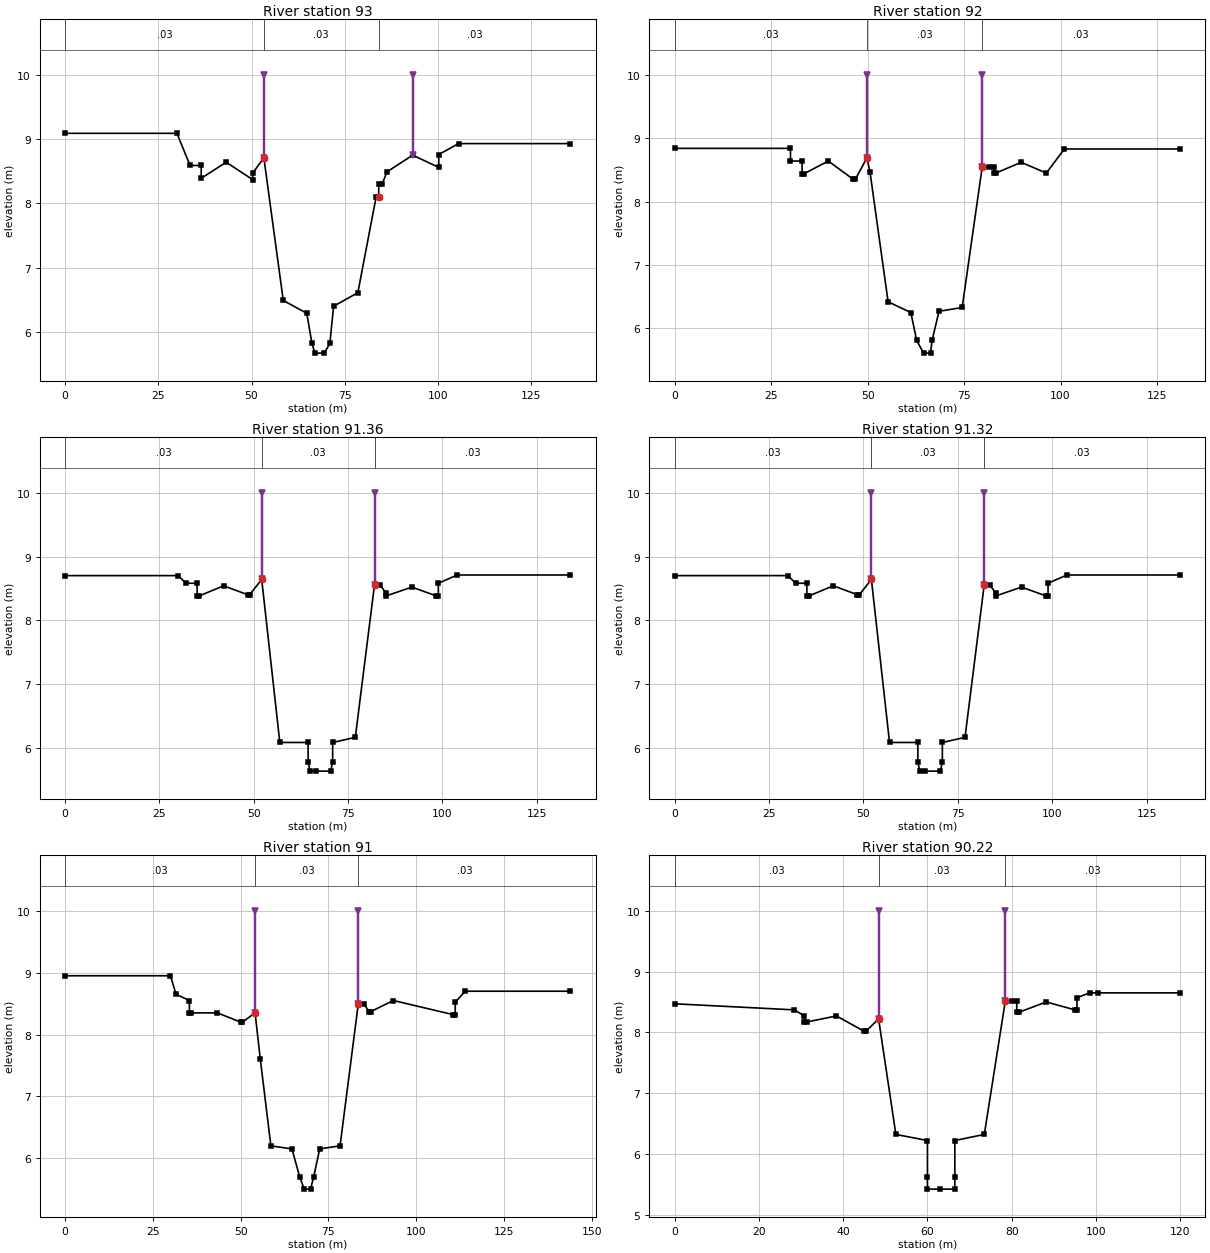
Type RM Length L Ch R = 1 ,93      ,50,50,50
#Sta/Elev= 27
       0    9.09      30    9.09    33.5    8.59    36.5    8.59    36.5    8.39
    43.2    8.64    50.3    8.37    50.3    8.47    53.3    8.71    58.5    6.49
    64.8    6.29    66.2    5.82      67    5.67    69.5    5.67      71    5.82
      72     6.4    78.5    6.61    83.4     8.1    84.1     8.1    84.1     8.3
      85     8.3    86.3    8.49    93.2    8.75   100.2    8.56   100.2    8.76
   105.5    8.93   135.5    8.93
#Mann= 3 , 0 , 0
       0     .03       0    53.3     .03       0    84.1     .03       0
Levee=-1,53.3,10,-1,93.2,10,,
Bank Sta=53.3,84.1
Exp/Cntr=0.3,0.1

Type RM Length L Ch R = 1 ,92      ,14,14,14
#Sta/Elev= 28
       0    8.84      30    8.84      30    8.64      33    8.64      33    8.44
    33.5    8.44    39.8    8.64    46.3    8.35    46.8    8.35    49.8    8.69
    50.6    8.47    55.3    6.42    61.2    6.25    62.7    5.81    64.5    5.61
    66.3    5.61    66.7    5.81    68.5    6.27    74.5    6.33    79.7    8.55
    81.5    8.55    82.7    8.55    82.7    8.45    83.2    8.45    89.8    8.62
    96.3    8.45     101    8.83     131    8.83
#Mann= 3 , 0 , 0
       0     .03       0    49.8     .03       0    79.7     .03       0
Levee=-1,49.8,10,-1,79.7,10,,
Bank Sta=49.8,79.7
Exp/Cntr=0.3,0.1

Type RM Length L Ch R = 1 ,91.36   ,4,4,4
#Sta/Elev= 29
       0     8.7      30     8.7      32    8.58      35    8.58      35    8.38
    35.5    8.38      42    8.54    48.4     8.4    48.9     8.4    52.1    8.64
    56.9    6.08    64.4    6.08    64.4    5.78    64.9    5.63    66.4    5.63
    70.4    5.63    70.9    5.78    70.9    6.08    76.9    6.16      82    8.56
    83.4    8.56      85    8.43      85    8.38    91.9    8.52    98.4    8.38
    98.9    8.38    98.9    8.58   103.9    8.71   133.9    8.71
#Mann= 3 , 0 , 0
       0     .03       0    52.1     .03       0      82     .03       0
Levee=-1,52.1,10,-1,82,10,,
Bank Sta=52.1,82
Exp/Cntr=0.3,0.1

Type RM Length L Ch R = 1 ,91.32   ,32,32,32
#Sta/Elev= 29
       0     8.7      30     8.7      32    8.58      35    8.58      35    8.38
    35.5    8.38      42    8.54    48.4     8.4    48.9     8.4    52.1    8.64
    56.9    6.08    64.4    6.08    64.4    5.78    64.9    5.63    66.4    5.63
    70.4    5.63    70.9    5.78    70.9    6.08    76.9    6.16      82    8.56
    83.4    8.56      85    8.43      85    8.38    91.9    8.52    98.4    8.38
    98.9    8.38    98.9    8.58   103.9    8.71   133.9    8.71
#Mann= 3 , 0 , 0
       0     .03       0    52.1     .03       0      82     .03       0
Levee=-1,52.1,10,-1,82,10,,
Bank Sta=52.1,82
Exp/Cntr=0.3,0.1

Type RM Length L Ch R = 1 ,91      ,28,28,28
#Sta/Elev= 29
       0    8.95      30    8.95    31.6    8.65    35.4    8.55    35.4    8.35
    35.9    8.35    43.4    8.35      50     8.2    50.5     8.2    54.1    8.35
    55.6     7.6    58.6     6.2    64.6    6.15    66.8     5.7    68.1     5.5
    69.9     5.5    70.8     5.7    72.5    6.15    78.3     6.2    83.5     8.5
    85.1     8.5    86.5    8.37      87    8.37    93.5    8.55   110.6    8.32
   111.1    8.32   111.1    8.52   113.9     8.7   143.9     8.7
#Mann= 3 , 0 , 0
       0     .03       0    54.1     .03       0    83.5     .03       0
Levee=-1,54.1,10,-1,83.5,10,,
Bank Sta=54.1,83.5
Exp/Cntr=0.3,0.1

Type RM Length L Ch R = 1 ,90.22   ,5,5,5
#Sta/Elev= 30
       0    8.47    28.4    8.37    30.8    8.27    30.8    8.17    31.3    8.17
    38.4    8.27    44.9    8.02    45.4    8.02    48.4    8.22    52.5    6.32
      60    6.22      60    5.62      60    5.42      63    5.42    66.5    5.42
    66.5    5.62    66.5    6.22    73.5    6.32    78.5    8.52      80    8.52
    81.2    8.52    81.2    8.33    81.7    8.33    88.2     8.5      95    8.37
    95.5    8.37    95.5    8.57    98.5    8.65   100.5    8.65     120    8.65
#Mann= 3 , 0 , 0
       0     .03       0    48.4     .03       0    78.5     .03       0
Levee=-1,48.4,10,-1,78.5,10,,
Bank Sta=48.4,78.5
Exp/Cntr=0.3,0.1