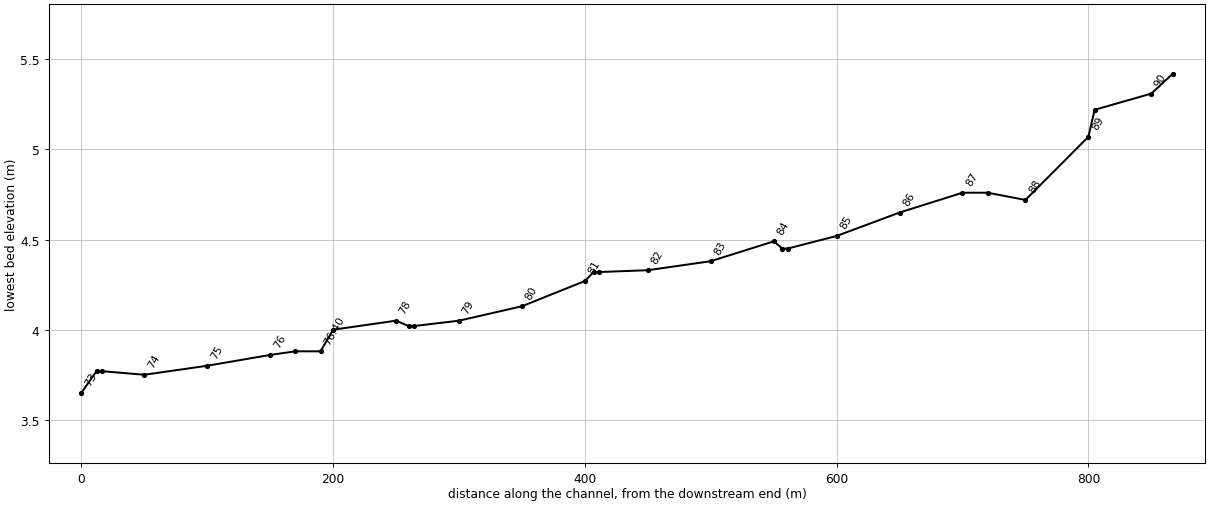
HEC-RAS study Hwajung.prj: Hwajung

--- Hwajung.g01 (geometry) --- (continued)

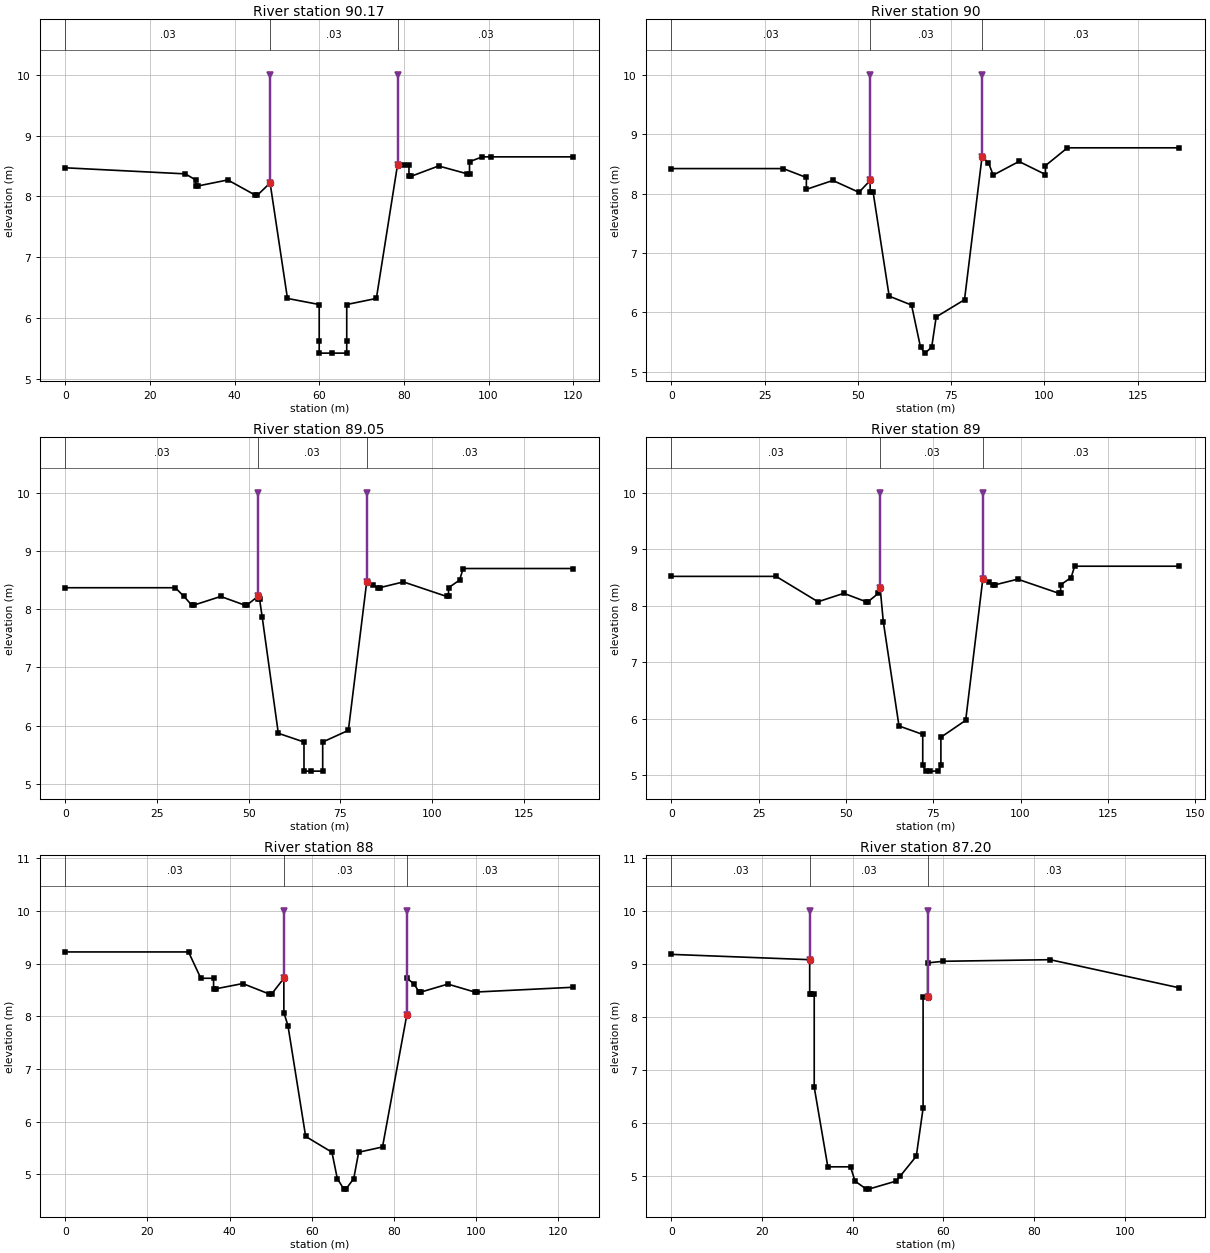
Type RM Length L Ch R = 1 ,90.17   ,17,17,17
#Sta/Elev= 30
       0    8.47    28.4    8.37    30.8    8.27    30.8    8.17    31.3    8.17
    38.4    8.27    44.9    8.02    45.4    8.02    48.4    8.22    52.5    6.32
      60    6.22      60    5.62      60    5.42      63    5.42    66.5    5.42
    66.5    5.62    66.5    6.22    73.5    6.32    78.5    8.52      80    8.52
    81.2    8.52    81.2    8.33    81.7    8.33    88.2     8.5      95    8.37
    95.5    8.37    95.5    8.57    98.5    8.65   100.5    8.65     120    8.65
#Mann= 3 , 0 , 0
       0     .03       0    48.4     .03       0    78.5     .03       0
Levee=-1,48.4,10,-1,78.5,10,,
Bank Sta=48.4,78.5
Exp/Cntr=0.3,0.1

Type RM Length L Ch R = 1 ,90      ,45,45,45
#Sta/Elev= 24
       0    8.42      30    8.42    36.2    8.27    36.2    8.07    43.3    8.22
    50.3    8.02    53.3    8.22    53.3    8.02    54.1    8.02    58.4    6.27
    64.4    6.12    66.8    5.41      68    5.31    69.8    5.41      71    5.92
    78.6    6.21    83.3    8.62      85    8.52    86.3    8.31    93.2    8.54
   100.3    8.32   100.3    8.47   106.2    8.77   136.2    8.77
#Mann= 3 , 0 , 0
       0     .03       0    53.3     .03       0    83.3     .03       0
Levee=-1,53.3,10,-1,83.3,10,,
Bank Sta=53.3,83.3
Exp/Cntr=0.3,0.1

Type RM Length L Ch R = 1 ,89.05   ,5,5,5
#Sta/Elev= 30
       0    8.37      30    8.37    32.4    8.22    34.5    8.07      35    8.07
    42.4    8.22      49    8.07    49.5    8.07    52.5    8.22    52.5    8.17
      53    8.17    53.7    7.87    58.1    5.87    65.1    5.72    65.1    5.22
      67    5.22    70.2    5.22    70.2    5.72    77.2    5.92    82.2    8.47
      84    8.42    85.2    8.37    85.7    8.37    92.2    8.47     104    8.22
   104.5    8.22   104.5    8.37   107.5     8.5   108.5     8.7   138.5     8.7
#Mann= 3 , 0 , 0
       0     .03       0    52.5     .03       0    82.2     .03       0
Levee=-1,52.5,10,-1,82.2,10,,
Bank Sta=52.5,82.2
Exp/Cntr=0.3,0.1

Type RM Length L Ch R = 1 ,89      ,50,50,50
#Sta/Elev= 29
       0    8.52      30    8.52      42    8.07    49.4    8.22    55.8    8.07
    56.3    8.07    59.3    8.22    59.8    8.32    60.7    7.72    65.2    5.87
      72    5.72      72    5.17      73    5.07      74    5.07    76.5    5.07
    77.2    5.17    77.2    5.67    84.3    5.97    89.2    8.47      91    8.42
    92.2    8.37    92.7    8.37    99.2    8.47     111    8.22   111.5    8.22
   111.5    8.37   114.5     8.5   115.5     8.7   145.5     8.7
#Mann= 3 , 0 , 0
       0     .03       0    59.8     .03       0    89.2     .03       0
Levee=-1,59.8,10,-1,89.2,10,,
Bank Sta=59.8,89.2
Exp/Cntr=0.3,0.1

Type RM Length L Ch R = 1 ,88      ,30,30,30
#Sta/Elev= 29
       0    9.22      30    9.22      33    8.72    36.1    8.72    36.1    8.52
    36.6    8.52    43.2    8.62    49.7    8.42    50.2    8.42    53.2    8.72
    53.2    8.07    54.2    7.82    58.5    5.72    64.9    5.42    66.2    4.92
    67.8    4.72    68.3    4.72    70.2    4.92    71.4    5.42    77.2    5.52
    83.1    8.02    83.1    8.72    84.8    8.62    86.1    8.46    86.6    8.46
    93.1    8.61    99.6    8.46   100.1    8.46   123.6    8.55
#Mann= 3 , 0 , 0
       0     .03       0    53.2     .03       0    83.1     .03       0
Levee=-1,53.2,10,-1,83.1,10,,
Bank Sta=53.2,83.1
Exp/Cntr=0.3,0.1

Type RM Length L Ch R = 1 ,87.20   ,20,20,20
#Sta/Elev= 21
       0    9.18    30.5    9.08    30.5    8.43   30.71    8.43    31.5    8.43
    31.5    6.68    34.5    5.18    39.5    5.18    40.5    4.91      43    4.76
    43.5    4.76    49.5    4.91    50.5    5.01      54    5.38    55.5    6.28
    55.5    8.37    56.5    8.37    56.5    9.02      60    9.05    83.5    9.08
     112    8.55
#Mann= 3 , 0 , 0
       0     .03       0    30.5     .03       0    56.5     .03       0
Levee=-1,30.5,10,-1,56.5,10,,
Bank Sta=30.5,56.5
Exp/Cntr=0.5,0.3

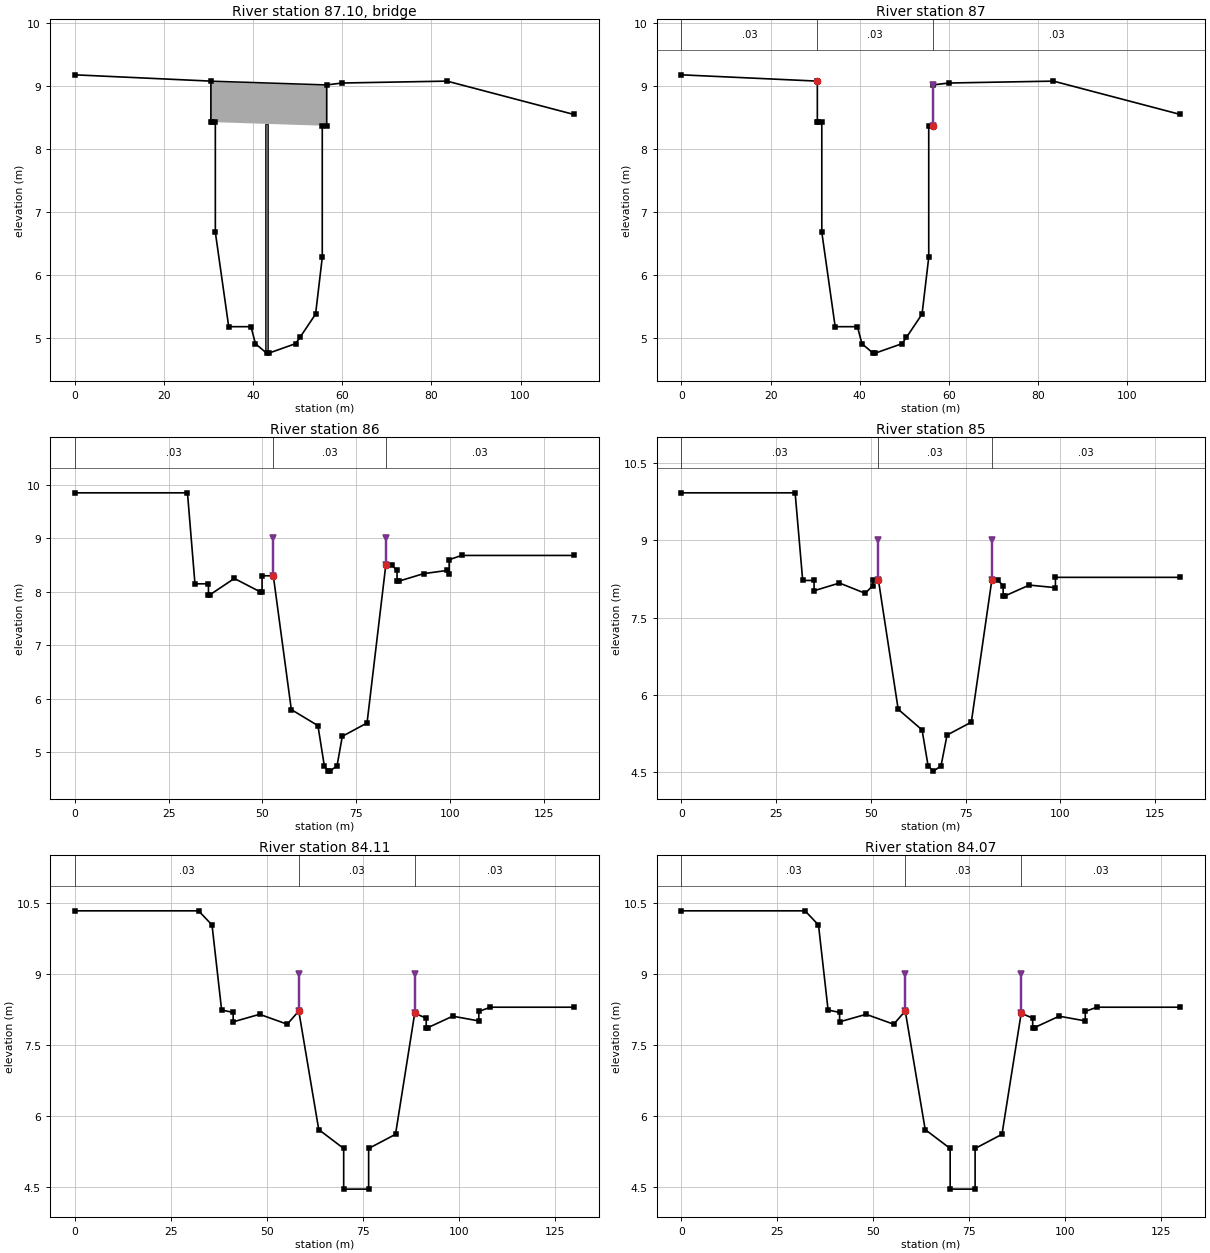
Type RM Length L Ch R = 3 ,87.10   ,,,
BEGIN DESCRIPTION:
È­Á¤5±³
END DESCRIPTION:
Bridge Culvert--1,0,-1,-1, 0
Deck Dist Width WeirC Skew NumUp NumDn MinLoCord MaxHiCord MaxSubmerge Is_Ogee
0.1,19,1.44,0, 2, 2, , , 0.95, 0, 0,0,,
    30.5    56.5
    9.08    9.02
    8.43    8.37
    30.5    56.5
    9.08    9.02
    8.43    8.37
Pier Skew, UpSta & Num, DnSta & Num=  ,43, 2 ,43, 2 , 0 , 0 , 0 ,,
      .6      .6
       4     9.5
      .6      .6
       4     9.5
BR Coef=-1 , 0 , 0 ,, 0 ,,,0.8,-1,,0,
WSPro=,,,, 1 ,,,, 0 ,,,, 0 ,,,,-1 ,-1 ,-1 , 0 , 0 , 0 , 0 , 0
BC Design=,, 0 ,, 0 ,,,,,,

Type RM Length L Ch R = 1 ,87      ,50,50,50
#Sta/Elev= 21
       0    9.18    30.5    9.08    30.5    8.43   30.71    8.43    31.5    8.43
    31.5    6.68    34.5    5.18    39.5    5.18    40.5    4.91      43    4.76
    43.5    4.76    49.5    4.91    50.5    5.01      54    5.38    55.5    6.28
    55.5    8.37    56.5    8.37    56.5    9.02      60    9.05    83.5    9.08
     112    8.55
#Mann= 3 , 0 , 0
       0     .03       0    30.5     .03       0    56.5     .03       0
Levee=0,,,-1,56.5,9.02,,
Bank Sta=30.5,56.5
Exp/Cntr=0.5,0.3

Type RM Length L Ch R = 1 ,86      ,50,50,50
#Sta/Elev= 30
       0    9.85      30    9.85      32    8.15    35.6    8.15    35.6    7.95
    36.1    7.95    42.5    8.25    49.4       8    49.9       8    49.9     8.3
    52.9     8.3    57.7     5.8    64.8     5.5    66.5    4.75    67.5    4.65
      68    4.65    69.9    4.75    71.3     5.3    77.9    5.55    82.9     8.5
    84.5     8.5    85.9     8.4    85.9     8.2    86.4     8.2      93    8.34
    99.3     8.4    99.8    8.34    99.8     8.6   103.1    8.68   133.1    8.68
#Mann= 3 , 0 , 0
       0     .03       0    52.9     .03       0    82.9     .03       0
Levee=-1,52.9,9,-1,82.9,9,,
Bank Sta=52.9,82.9
Exp/Cntr=0.3,0.1

Type RM Length L Ch R = 1 ,85      ,39,39,39
#Sta/Elev= 26
       0    9.92      30    9.92      32    8.22      35    8.22      35    8.02
    41.7    8.17    48.5    7.97    50.5    8.12    50.5    8.22      52    8.22
    57.2    5.72    63.5    5.32    65.1    4.62    66.5    4.52    68.5    4.62
    70.1    5.22    76.5    5.47    81.9    8.22    83.5    8.22    84.9    8.12
    84.9    7.92    85.4    7.92    91.8    8.13    98.7    8.08    98.7    8.28
   131.7    8.28
#Mann= 3 , 0 , 0
       0     .03       0      52     .03       0    81.9     .03       0
Levee=-1,52,9,-1,81.9,9,,
Bank Sta=52,81.9
Exp/Cntr=0.3,0.1

Type RM Length L Ch R = 1 ,84.11   ,4,4,4
#Sta/Elev= 24
       0   10.34    32.2   10.34    35.7   10.04    38.2    8.24    41.2    8.19
    41.2    7.99    48.1    8.15    55.3    7.94    58.3    8.22    63.5    5.71
      70    5.31      70    4.45    76.5    4.45    76.5    5.31    83.5    5.61
    88.5    8.17    91.5    8.07    91.5    7.87      92    7.87    98.4    8.11
   105.2    8.01   105.2    8.21   108.2     8.3     130     8.3
#Mann= 3 , 0 , 0
       0     .03       0    58.3     .03       0    88.5     .03       0
Levee=-1,58.3,9,-1,88.5,9,,
Bank Sta=58.3,88.5
Exp/Cntr=0.3,0.1

Type RM Length L Ch R = 1 ,84.07   ,7,7,7
#Sta/Elev= 24
       0   10.34    32.2   10.34    35.7   10.04    38.2    8.24    41.2    8.19
    41.2    7.99    48.1    8.15    55.3    7.94    58.3    8.22    63.5    5.71
      70    5.31      70    4.45    76.5    4.45    76.5    5.31    83.5    5.61
    88.5    8.17    91.5    8.07    91.5    7.87      92    7.87    98.4    8.11
   105.2    8.01   105.2    8.21   108.2     8.3     130     8.3
#Mann= 3 , 0 , 0
       0     .03       0    58.3     .03       0    88.5     .03       0
Levee=-1,58.3,9,-1,88.5,9,,
Bank Sta=58.3,88.5
Exp/Cntr=0.3,0.1

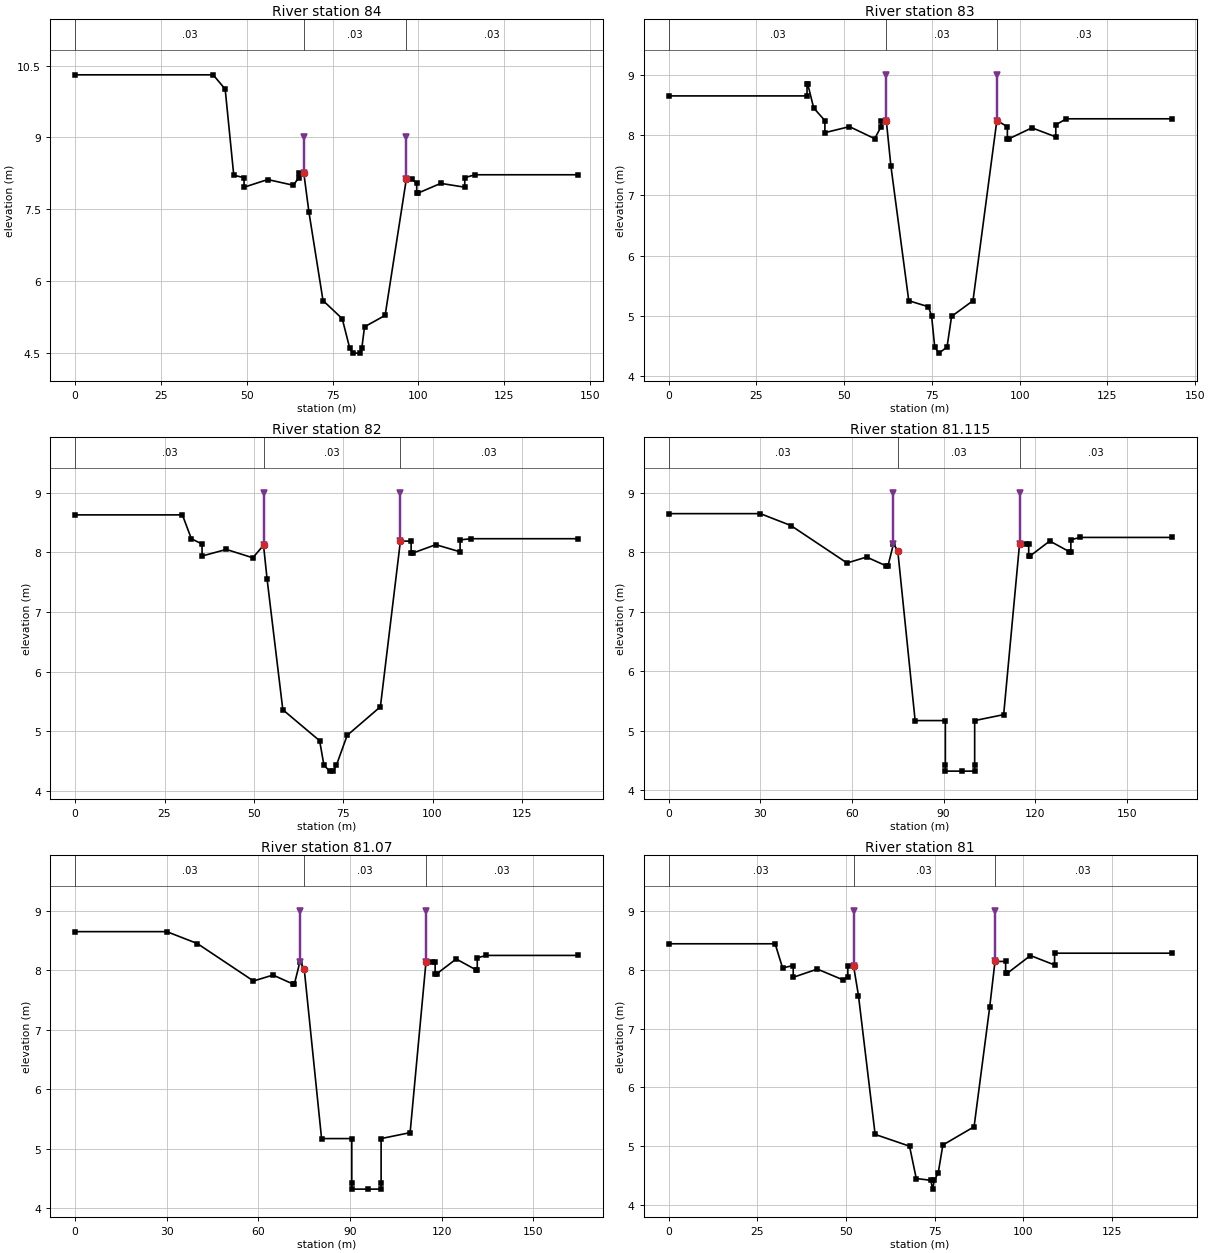
Type RM Length L Ch R = 1 ,84      ,50,50,50
#Sta/Elev= 30
       0   10.31    40.2   10.31    43.7   10.01    46.2    8.21    49.2    8.16
    49.2    7.96    56.1    8.12    63.6       8    65.1    8.16    65.1    8.26
    66.6    8.26    68.1    7.44    72.2    5.59    77.8    5.21      80    4.59
      81    4.49      83    4.49    83.5    4.59    84.3    5.04    90.3    5.28
    96.5    8.14      98    8.14    99.5    8.04    99.5    7.84     100    7.84
   106.5    8.04   113.5    7.96   113.5    8.16   116.5    8.22   146.5    8.22
#Mann= 3 , 0 , 0
       0     .03       0    66.6     .03       0    96.5     .03       0
Levee=-1,66.6,9,-1,96.5,9,,
Bank Sta=66.6,96.5
Exp/Cntr=0.3,0.1

Type RM Length L Ch R = 1 ,83      ,50,50,50
#Sta/Elev= 30
       0    8.65    39.4    8.65    39.4    8.85    39.6    8.85    41.3    8.45
    44.5    8.24    44.5    8.04    51.5    8.14    58.7    7.94    60.5    8.14
    60.5    8.24      62    8.24    63.3    7.49    68.4    5.25      74    5.15
    74.9       5    75.8    4.48      77    4.38    79.3    4.48    80.6    4.99
    86.7    5.25    93.5    8.24    96.5    8.14    96.5    7.94      97    7.94
   103.5    8.12   110.3    7.97   110.3    8.17   113.3    8.27   143.3    8.27
#Mann= 3 , 0 , 0
       0     .03       0      62     .03       0    93.5     .03       0
Levee=-1,62,9,-1,93.5,9,,
Bank Sta=62,93.5
Exp/Cntr=0.3,0.1

Type RM Length L Ch R = 1 ,82      ,38.5,38.5,38.5
#Sta/Elev= 26
       0    8.63      30    8.63    32.5    8.23    35.5    8.14    35.5    7.94
    42.3    8.05    49.7    7.91    52.7    8.12    53.7    7.55    58.1    5.36
    68.4    4.84    69.6    4.43    71.2    4.33    72.2    4.33    73.1    4.43
    76.1    4.93    85.4    5.41      91    8.19      94    8.19      94    7.99
    94.5    7.99   100.9    8.13   107.7    8.01   107.7    8.21   110.7    8.23
   140.7    8.23
#Mann= 3 , 0 , 0
       0     .03       0    52.7     .03       0      91     .03       0
Levee=-1,52.7,9,-1,91,9,,
Bank Sta=52.7,91
Exp/Cntr=0.3,0.1

Type RM Length L Ch R = 1 ,81.115  ,4.5,4.5,4.5
#Sta/Elev= 29
       0    8.65      30    8.65      40    8.45    58.4    7.82    64.8    7.92
    71.3    7.77    71.8    7.77    73.6    8.14      75    8.03    80.7    5.17
    90.6    5.17    90.6    4.42    90.6    4.32      96    4.32   100.2    4.32
   100.2    4.42   100.2    5.17   109.7    5.27   114.9    8.14     117    8.14
   117.9    8.14   117.9    7.94   118.4    7.94   124.8    8.19   131.2    8.01
   131.7    8.01   131.7    8.21   134.7    8.25   164.7    8.25
#Mann= 3 , 0 , 0
       0     .03       0      75     .03       0   114.9     .03       0
Levee=-1,73.6,9,-1,114.9,9,,
Bank Sta=75,114.9
Exp/Cntr=0.3,0.1

Type RM Length L Ch R = 1 ,81.07   ,7,7,7
#Sta/Elev= 29
       0    8.65      30    8.65      40    8.45    58.4    7.82    64.8    7.92
    71.3    7.77    71.8    7.77    73.6    8.14      75    8.03    80.7    5.17
    90.6    5.17    90.6    4.42    90.6    4.32      96    4.32   100.2    4.32
   100.2    4.42   100.2    5.17   109.7    5.27   114.9    8.14     117    8.14
   117.9    8.14   117.9    7.94   118.4    7.94   124.8    8.19   131.2    8.01
   131.7    8.01   131.7    8.21   134.7    8.25   164.7    8.25
#Mann= 3 , 0 , 0
       0     .03       0      75     .03       0   114.9     .03       0
Levee=-1,73.6,9,-1,114.9,9,,
Bank Sta=75,114.9
Exp/Cntr=0.3,0.1

Type RM Length L Ch R = 1 ,81      ,50,50,50
#Sta/Elev= 29
       0    8.44      30    8.44    32.1    8.03    35.1    8.07    35.1    7.87
    41.9    8.01      49    7.83    50.5    7.87    50.5    8.07    52.1    8.07
    53.5    7.56    58.2     5.2    67.9       5    69.8    4.45    73.9    4.42
    74.4    4.27    74.9    4.42      76    4.55    77.3    5.02    86.1    5.33
    90.5    7.36      92    8.14      95    8.14      95    7.94    95.5    7.94
     102    8.24   108.8    8.08   108.8    8.28   141.8    8.28
#Mann= 3 , 0 , 0
       0     .03       0    52.1     .03       0      92     .03       0
Levee=-1,52.1,9,-1,92,9,,
Bank Sta=52.1,92
Exp/Cntr=0.3,0.1

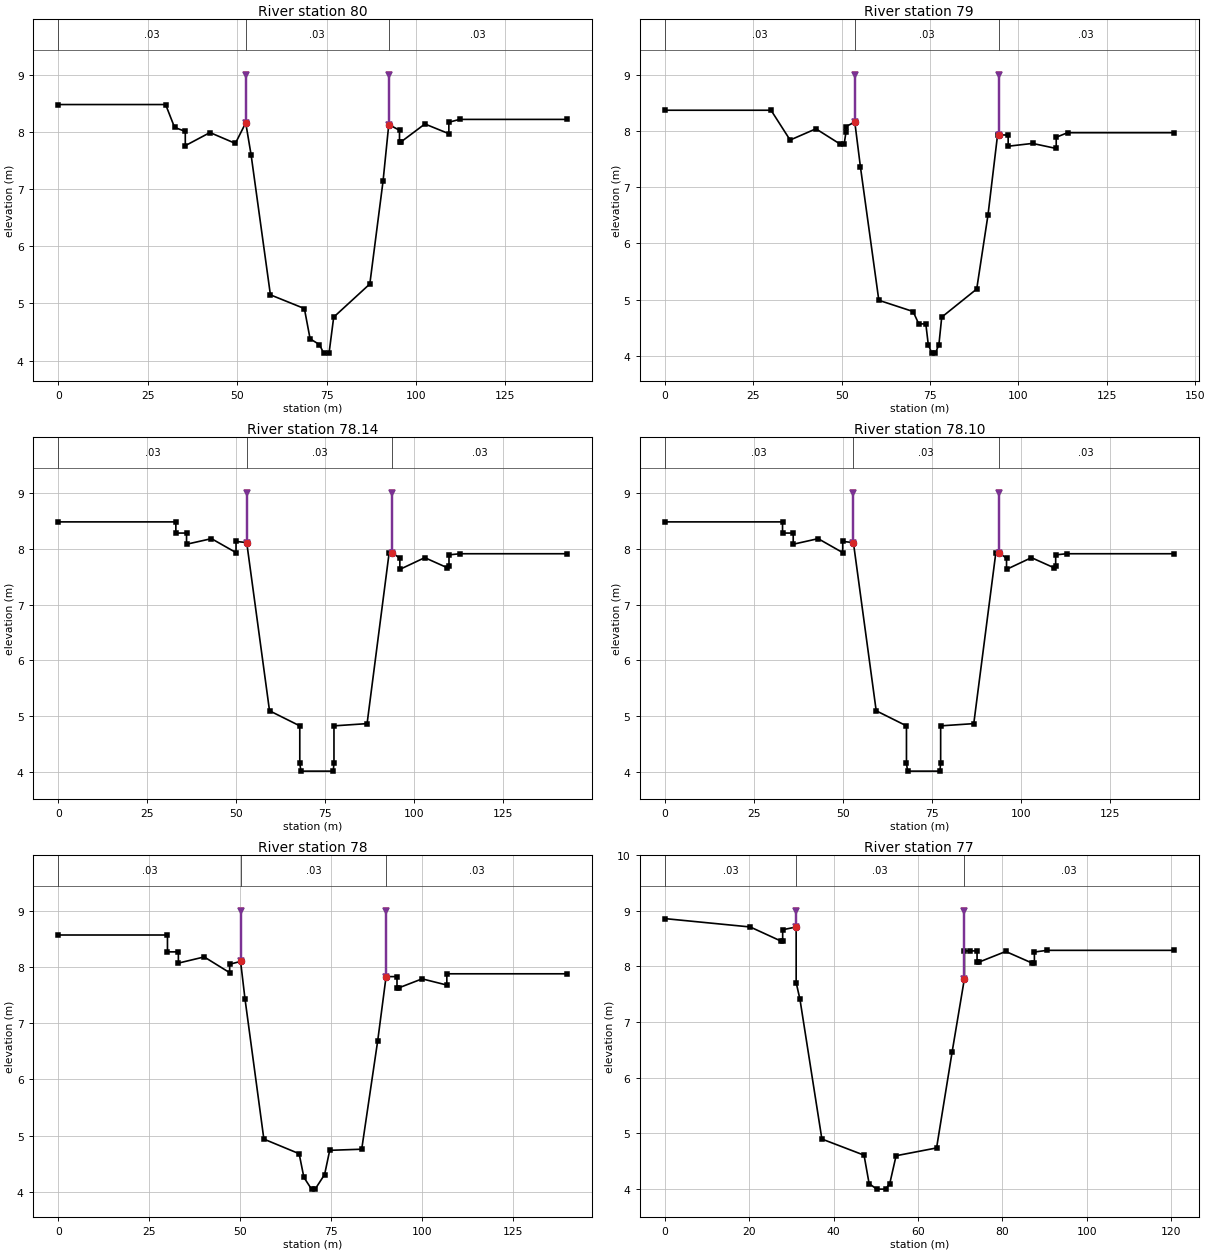
Type RM Length L Ch R = 1 ,80      ,50,50,50
#Sta/Elev= 27
       0    8.48      30    8.48    32.5    8.08    35.5    8.01    35.5    7.76
    42.4    7.99    49.5     7.8    52.4    8.16    53.9     7.6    59.3    5.15
    68.8    4.91    70.4    4.38      73    4.28    74.2    4.13    75.7    4.13
      77    4.76    87.1    5.34    90.8    7.14    92.4    8.13    95.4    8.03
    95.4    7.83    95.9    7.83   102.5    8.14   109.2    7.97   109.2    8.17
   112.2    8.22   142.2    8.22
#Mann= 3 , 0 , 0
       0     .03       0    52.4     .03       0    92.4     .03       0
Levee=-1,52.4,9,-1,92.4,9,,
Bank Sta=52.4,92.4
Exp/Cntr=0.3,0.1

Type RM Length L Ch R = 1 ,79      ,36,36,36
#Sta/Elev= 30
       0    8.37      30    8.37    35.4    7.84    42.7    8.04    49.5    7.77
    50.7    7.77    51.2    7.98    51.2    8.08    53.7    8.16    55.3    7.36
    60.5    4.99    70.2    4.79    71.8    4.57    73.8    4.57    74.5     4.2
    75.5    4.05    76.5    4.05    77.5     4.2    78.3    4.69    88.2    5.19
    91.4    6.51    94.1    7.93    94.5    7.93    97.1    7.93    97.1    7.73
     104    7.78   110.7    7.69   110.7    7.89   113.9    7.97   143.9    7.97
#Mann= 3 , 0 , 0
       0     .03       0    53.7     .03       0    94.5     .03       0
Levee=-1,53.7,9,-1,94.5,9,,
Bank Sta=53.7,94.5
Exp/Cntr=0.3,0.1

Type RM Length L Ch R = 1 ,78.14   ,4,4,4
#Sta/Elev= 27
       0    8.48      33    8.48      33    8.28      36    8.28      36    8.08
      43    8.18    49.9    7.93    49.9    8.13    52.9    8.11    59.3     5.1
    67.8    4.83    67.8    4.17    68.1    4.02    77.2    4.02    77.4    4.17
    77.4    4.83    86.7    4.87    92.9    7.93    93.7    7.93    95.9    7.83
    95.9    7.63   102.9    7.84   109.2    7.66   109.7    7.69   109.7    7.89
   112.8    7.91   142.8    7.91
#Mann= 3 , 0 , 0
       0     .03       0    52.9     .03       0    93.7     .03       0
Levee=-1,52.9,9,-1,93.7,9,,
Bank Sta=52.9,93.7
Exp/Cntr=0.3,0.1

Type RM Length L Ch R = 1 ,78.10   ,10,10,10
#Sta/Elev= 27
       0    8.48      33    8.48      33    8.28      36    8.28      36    8.08
      43    8.18    49.9    7.93    49.9    8.13    52.9    8.11    59.3     5.1
    67.8    4.83    67.8    4.17    68.1    4.02    77.2    4.02    77.4    4.17
    77.4    4.83    86.7    4.87    92.9    7.93    93.7    7.93    95.9    7.83
    95.9    7.63   102.9    7.84   109.2    7.66   109.7    7.69   109.7    7.89
   112.8    7.91   142.8    7.91
#Mann= 3 , 0 , 0
       0     .03       0    52.9     .03       0    93.7     .03       0
Levee=-1,52.9,9,-1,93.7,9,,
Bank Sta=52.9,93.7
Exp/Cntr=0.3,0.1

Type RM Length L Ch R = 1 ,78      ,50,50,50
#Sta/Elev= 27
       0    8.57      30    8.57      30    8.27      33    8.27      33    8.07
    40.1    8.18    47.1     7.9    47.1    8.05    50.1     8.1    51.3    7.44
    56.5    4.94    66.2    4.68    67.5    4.26    69.6    4.05    70.6    4.05
    73.2    4.31    74.6    4.74    83.4    4.76    87.8    6.69    90.1    7.83
    93.1    7.83    93.1    7.63    93.6    7.63     100    7.79   106.8    7.68
   106.8    7.88   139.8    7.88
#Mann= 3 , 0 , 0
       0     .03       0    50.1     .03       0    90.1     .03       0
Levee=-1,50.1,9,-1,90.1,9,,
Bank Sta=50.1,90.1
Exp/Cntr=0.3,0.1

Type RM Length L Ch R = 1 ,77      ,10,10,10
#Sta/Elev= 29
       0    8.86    20.2    8.71    27.4    8.46    27.9    8.46    27.9    8.66
    31.1    8.71    31.1    7.71      32    7.41    37.2     4.9    47.2    4.61
    48.4     4.1    50.2       4    52.3       4    53.3     4.1    54.8     4.6
    64.4    4.74    68.1    6.47      71    7.78      71    8.28    72.3    8.28
      74    8.28      74    8.08    74.5    8.08    80.8    8.27    87.1    8.06
    87.6    8.06    87.6    8.26    90.6    8.29   120.6    8.29
#Mann= 3 , 0 , 0
       0     .03       0    31.1     .03       0      71     .03       0
Levee=-1,31.1,9,-1,71,9,,
Bank Sta=31.1,71
Exp/Cntr=0.3,0.1

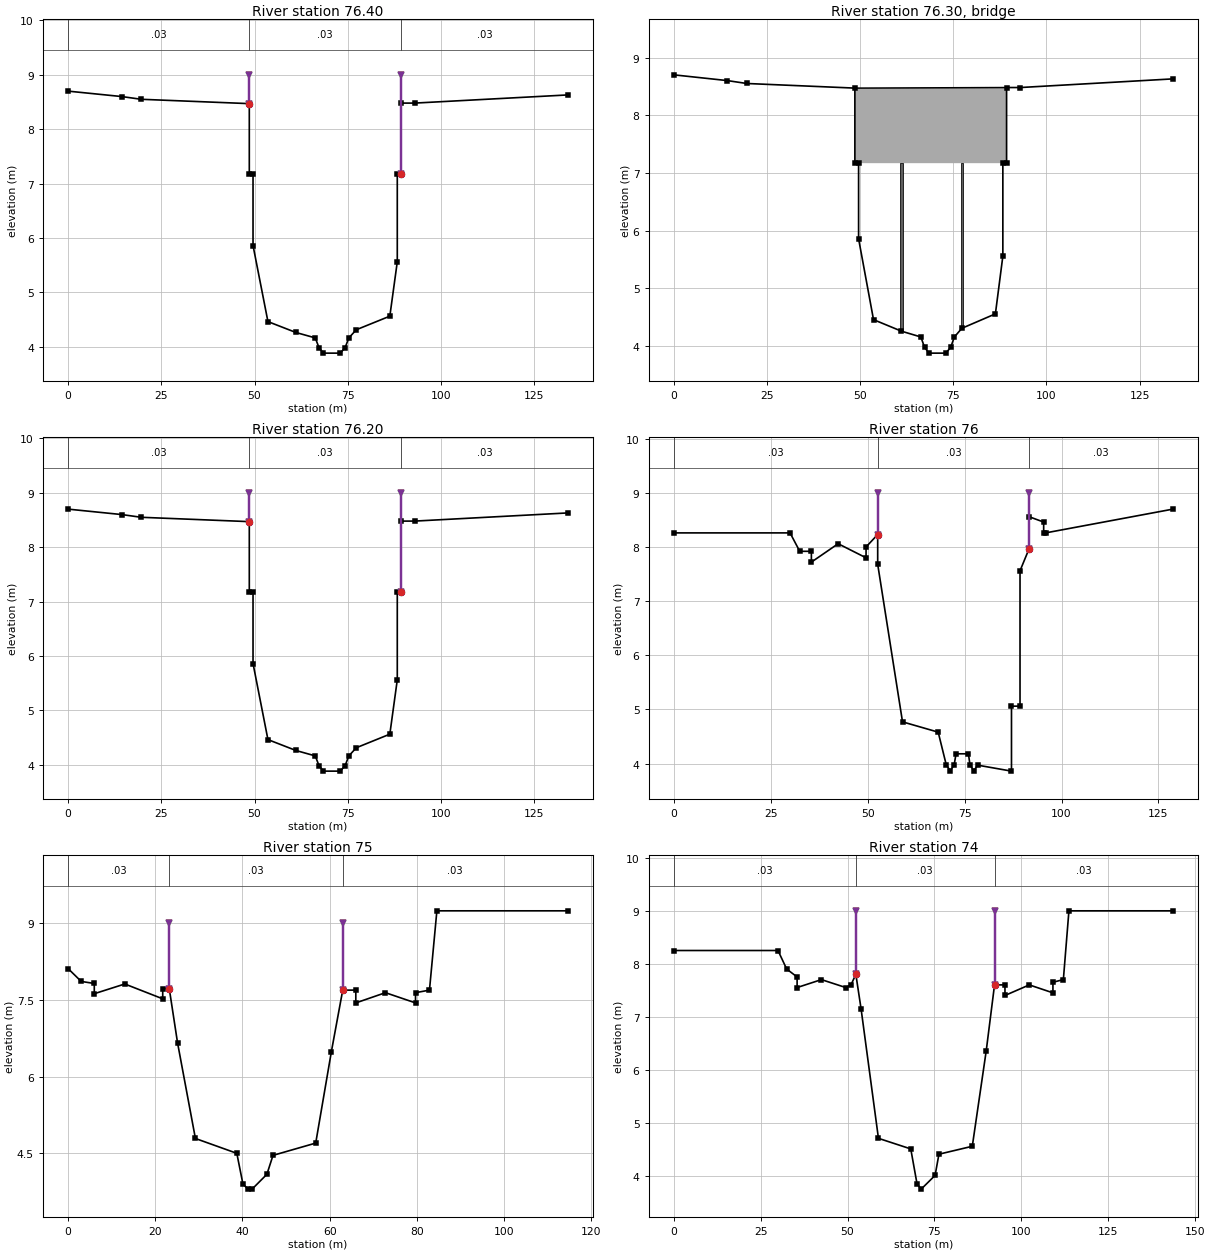
Type RM Length L Ch R = 1 ,76.40   ,20,20,20
#Sta/Elev= 23
       0     8.7    14.4     8.6    19.6    8.55    48.6    8.47    48.6    7.17
    49.6    7.17    49.6    5.86    53.6    4.46    61.1    4.26    66.3    4.16
    67.3    3.98    68.5    3.88      73    3.88    74.3    3.98    75.3    4.16
    77.3    4.31    86.3    4.56    88.3    5.56    88.3    7.18    89.3    7.18
    89.3    8.48      93    8.48     134    8.63
#Mann= 3 , 0 , 0
       0     .03       0    48.6     .03       0    89.3     .03       0
Levee=-1,48.6,9,-1,89.3,9,,
Bank Sta=48.6,89.3
Exp/Cntr=0.5,0.3

Type RM Length L Ch R = 3 ,76.30   ,,,
BEGIN DESCRIPTION:
È­Á¤4±³
END DESCRIPTION:
Bridge Culvert--1,0,-1,-1, 0
Deck Dist Width WeirC Skew NumUp NumDn MinLoCord MaxHiCord MaxSubmerge Is_Ogee
0.1,19,1.44,0, 2, 2, , , 0.95, 0, 0,0,,
    48.6    89.3
    8.47    8.48
    7.17    7.17
    48.6    89.3
    8.47    8.48
    7.17    7.17
Pier Skew, UpSta & Num, DnSta & Num=  ,61.1, 2 ,61.1, 2 , 0 , 0 , 0 ,,
      .6      .6
     3.5       9
      .6      .6
     3.5       9
Pier Skew, UpSta & Num, DnSta & Num=  ,77.3, 2 ,77.3, 2 , 0 , 0 , 0 ,,
      .6      .6
     3.5       9
      .6      .6
     3.5       9
BR Coef=-1 , 0 , 0 ,, 0 ,,,0.8,-1,,0,
WSPro=,,,, 1 ,,,, 0 ,,,, 0 ,,,,-1 ,-1 ,-1 , 0 , 0 , 0 , 0 , 0
BC Design=,, 0 ,, 0 ,,,,,,

Type RM Length L Ch R = 1 ,76.20   ,20,20,20
#Sta/Elev= 23
       0     8.7    14.4     8.6    19.6    8.55    48.6    8.47    48.6    7.17
    49.6    7.17    49.6    5.86    53.6    4.46    61.1    4.26    66.3    4.16
    67.3    3.98    68.5    3.88      73    3.88    74.3    3.98    75.3    4.16
    77.3    4.31    86.3    4.56    88.3    5.56    88.3    7.18    89.3    7.18
    89.3    8.48      93    8.48     134    8.63
#Mann= 3 , 0 , 0
       0     .03       0    48.6     .03       0    89.3     .03       0
Levee=-1,48.6,9,-1,89.3,9,,
Bank Sta=48.6,89.3
Exp/Cntr=0.5,0.3

Type RM Length L Ch R = 1 ,76      ,50,50,50
#Sta/Elev= 30
       0    8.26      30    8.26    32.5    7.92    35.5    7.92    35.5    7.72
    42.4    8.06    49.6     7.8    49.6       8    52.6    8.23    52.6    7.68
      59    4.77    68.2    4.58    70.3    3.97    71.3    3.87    72.3    3.97
    72.8    4.18      76    4.18    76.4    3.97    77.4    3.87    78.4    3.97
    87.1    3.86    87.1    5.06    89.3    5.06    89.3    7.56    91.6    7.96
    91.6    8.56    95.4    8.46    95.4    8.26    95.9    8.26   128.8     8.7
#Mann= 3 , 0 , 0
       0     .03       0    52.6     .03       0    91.6     .03       0
Levee=-1,52.6,9,-1,91.6,9,,
Bank Sta=52.6,91.6
Exp/Cntr=0.3,0.1

Type RM Length L Ch R = 1 ,75      ,50,50,50
#Sta/Elev= 27
       0    8.11       3    7.86       6    7.82       6    7.62      13    7.81
    21.7    7.52    21.7    7.72    23.2    7.72    25.1    6.66    29.2    4.79
    38.7     4.5    40.1     3.9    41.3     3.8    42.2     3.8    45.6    4.09
      47    4.46    56.8     4.7    60.4    6.49      63    7.69      66    7.69
      66    7.44    72.8    7.64    79.7    7.44    79.7    7.64    82.9    7.69
    84.6    9.24   114.6    9.24
#Mann= 3 , 0 , 0
       0     .03       0    23.2     .03       0      63     .03       0
Levee=-1,23.2,9,-1,63,9,,
Bank Sta=23.2,63
Exp/Cntr=0.3,0.1

Type RM Length L Ch R = 1 ,74      ,34,34,34
#Sta/Elev= 27
       0    8.26      30    8.26    32.5    7.91    35.5    7.76    35.5    7.56
    42.5    7.71    49.5    7.56      51    7.61    52.4    7.81    53.9    7.16
    58.9    4.71    68.2    4.51      70    3.85    71.2    3.75    75.2    4.01
    76.3    4.41    85.9    4.56    89.9    6.36    92.3    7.61    95.3    7.61
    95.3    7.41   102.3    7.61   109.1    7.46   109.1    7.66   112.1    7.71
   113.7    9.01   143.7    9.01
#Mann= 3 , 0 , 0
       0     .03       0    52.4     .03       0    92.3     .03       0
Levee=-1,52.4,9,-1,92.3,9,,
Bank Sta=52.4,92.3
Exp/Cntr=0.3,0.1

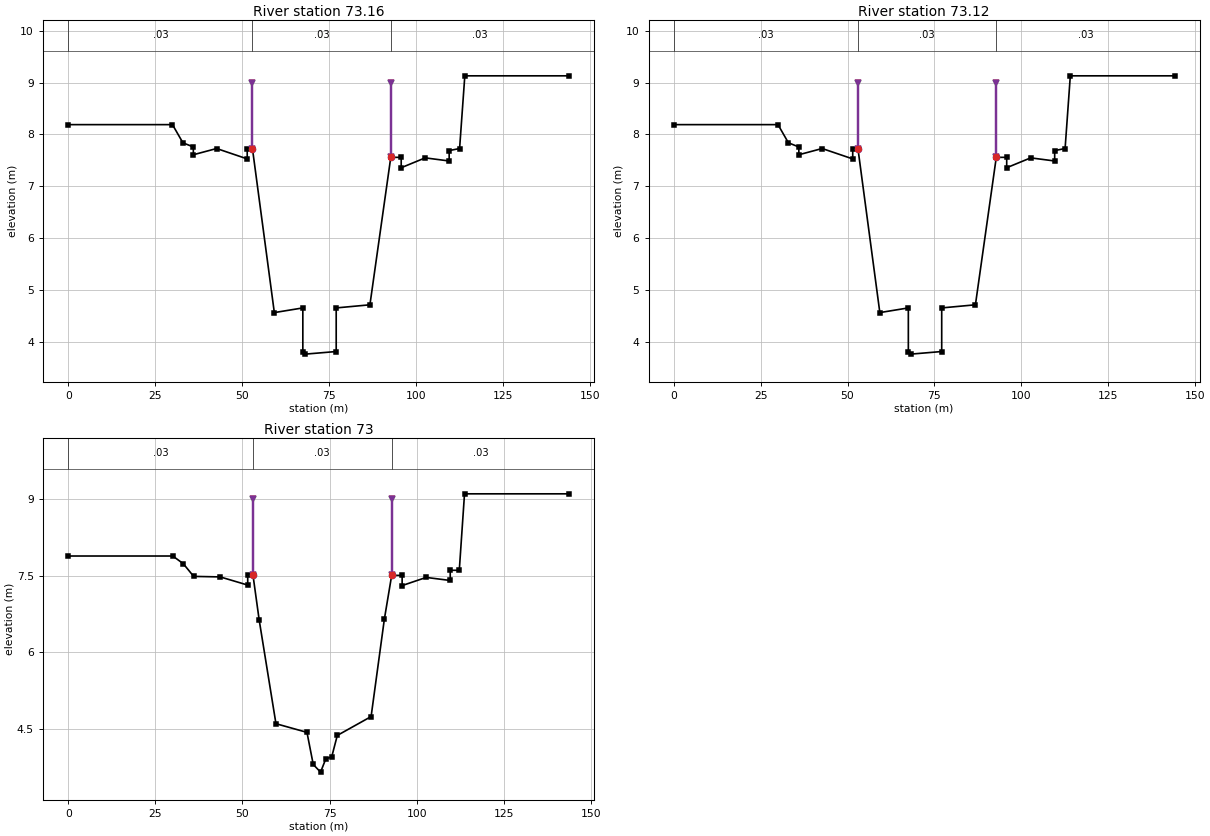
Type RM Length L Ch R = 1 ,73.16   ,4,4,4
#Sta/Elev= 25
       0    8.19      30    8.19      33    7.84      36    7.76      36    7.61
    42.7    7.73    51.5    7.53    51.5    7.73      53    7.73    59.3    4.57
    67.5    4.66    67.5    3.82    68.2    3.77    77.1    3.82    77.1    4.66
    86.8    4.72    92.8    7.56    95.8    7.56    95.8    7.36   102.7    7.55
   109.6    7.49   109.6    7.69   112.6    7.73   114.1    9.13   144.1    9.13
#Mann= 3 , 0 , 0
       0     .03       0      53     .03       0    92.8     .03       0
Levee=-1,53,9,-1,92.8,9,,
Bank Sta=53,92.8
Exp/Cntr=0.3,0.1

Type RM Length L Ch R = 1 ,73.12   ,12,12,12
#Sta/Elev= 25
       0    8.19      30    8.19      33    7.84      36    7.76      36    7.61
    42.7    7.73    51.5    7.53    51.5    7.73      53    7.73    59.3    4.57
    67.5    4.66    67.5    3.82    68.2    3.77    77.1    3.82    77.1    4.66
    86.8    4.72    92.8    7.56    95.8    7.56    95.8    7.36   102.7    7.55
   109.6    7.49   109.6    7.69   112.6    7.73   114.1    9.13   144.1    9.13
#Mann= 3 , 0 , 0
       0     .03       0      53     .03       0    92.8     .03       0
Levee=-1,53,9,-1,92.8,9,,
Bank Sta=53,92.8
Exp/Cntr=0.3,0.1

Type RM Length L Ch R = 1 ,73      ,50,50,50
#Sta/Elev= 27
       0    7.89      30    7.89      33    7.74      36    7.49    43.6    7.48
    51.5    7.32    51.5    7.52      53    7.52    54.8    6.63    59.6     4.6
    68.5    4.43    70.3     3.8    72.4    3.65    73.9    3.91    75.6    3.95
    77.2    4.37    86.9    4.74    90.7    6.65    92.8    7.51    95.8    7.51
    95.8    7.31   102.7    7.47   109.6    7.41   109.6    7.61   112.2    7.61
   113.7    9.11   143.7    9.11
#Mann= 3 , 0 , 0
       0     .03       0      53     .03       0    92.8     .03       0
Levee=-1,53,9,-1,92.8,9,,
Bank Sta=53,92.8
Exp/Cntr=0.3,0.1