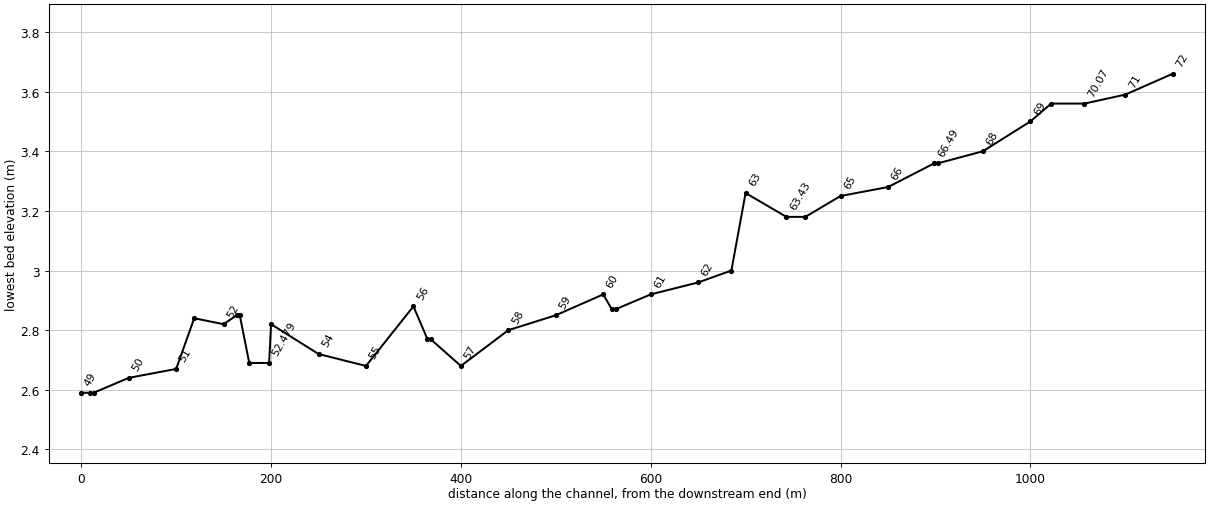
HEC-RAS study Hwajung.prj: Hwajung

--- Hwajung.g01 (geometry) --- (continued)

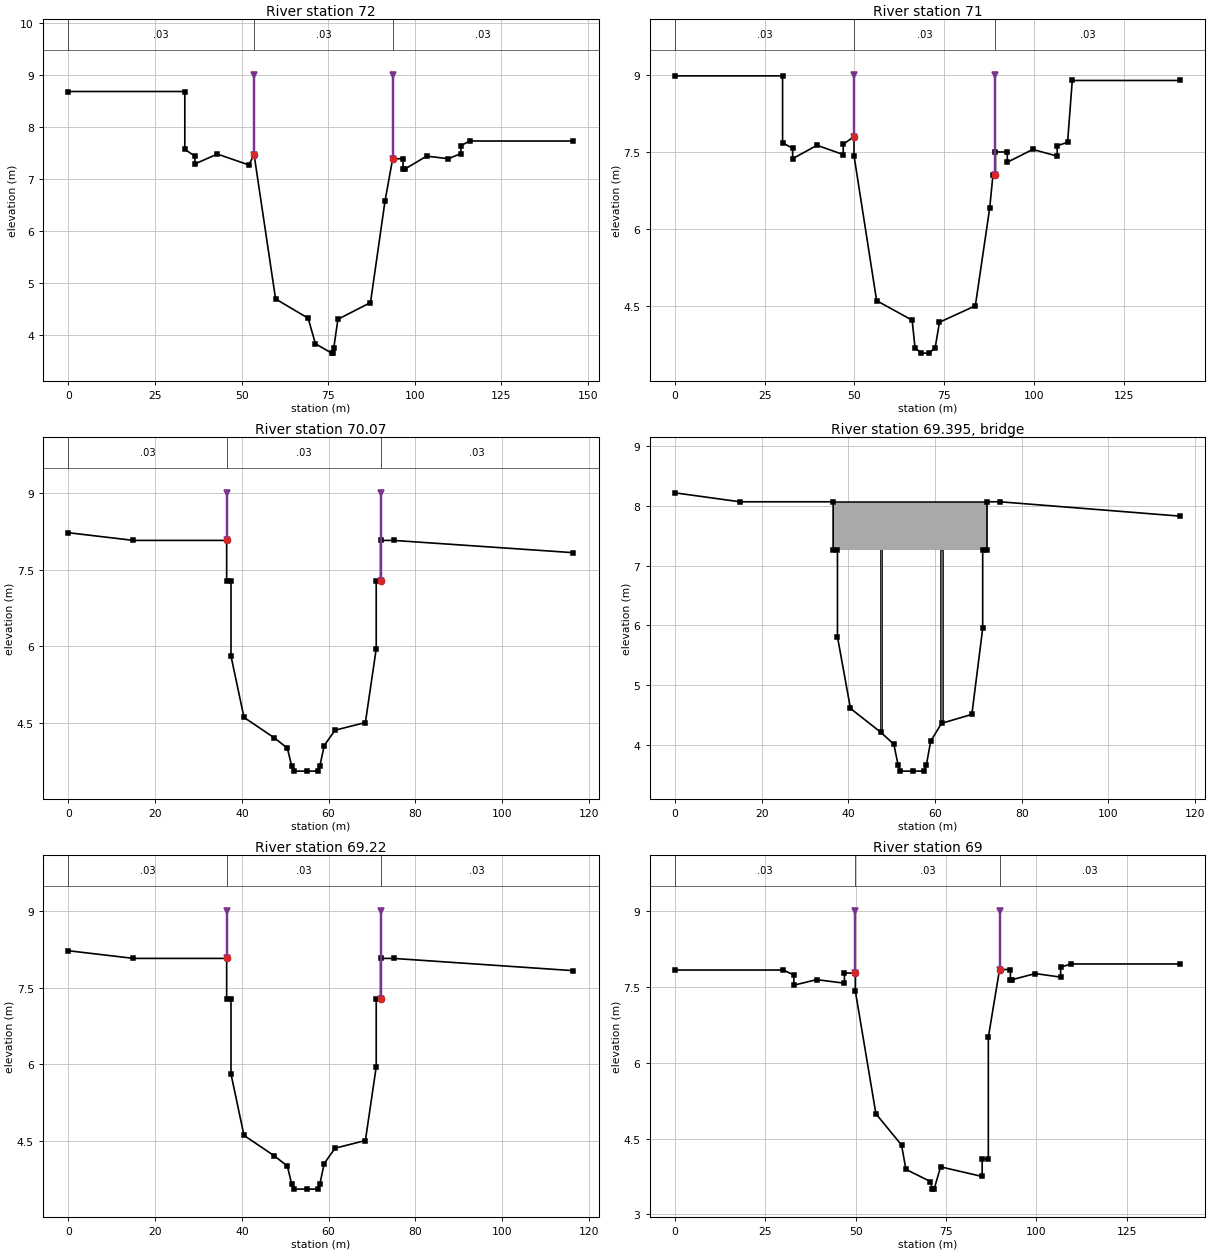
Type RM Length L Ch R = 1 ,72      ,50,50,50
#Sta/Elev= 27
       0    8.68    33.6    8.68    33.6    7.57    36.5    7.44    36.5    7.29
      43    7.48    52.1    7.27    53.6    7.47    59.8     4.7    69.2    4.33
    71.3    3.84      76    3.66    76.5    3.66    76.6    3.76    77.8    4.31
    87.2    4.63    91.4    6.58    93.6    7.39    96.6    7.39    96.6    7.19
    97.1    7.19   103.4    7.44   109.7    7.39   113.3    7.49   113.3    7.64
   115.8    7.73   145.8    7.73
#Mann= 3 , 0 , 0
       0     .03       0    53.6     .03       0    93.6     .03       0
Levee=-1,53.6,9,-1,93.6,9,,
Bank Sta=53.6,93.6
Exp/Cntr=0.3,0.1

Type RM Length L Ch R = 1 ,71      ,43,43,43
#Sta/Elev= 30
       0    8.98      30    8.98      30    7.68    32.8    7.57    32.8    7.37
    39.6    7.63    46.9    7.45    46.9    7.65    49.9     7.8    49.9    7.43
    56.2    4.61    66.1    4.23    66.9    3.69    68.7    3.59    70.7    3.59
    72.5    3.69    73.7    4.19    83.7    4.51    87.7    6.41    88.6    7.05
    89.3    7.05    89.3     7.5    92.6     7.5    92.6     7.3    99.7    7.55
   106.5    7.42   106.5    7.62   109.4    7.69   110.7    8.89   140.7    8.89
#Mann= 3 , 0 , 0
       0     .03       0    49.9     .03       0    89.3     .03       0
Levee=-1,49.9,9,-1,89.3,9,,
Bank Sta=49.9,89.3
Exp/Cntr=0.3,0.1

Type RM Length L Ch R = 1 ,70.07   ,35,35,35
#Sta/Elev= 23
       0    8.22      15    8.07    36.5    8.07    36.5    7.27    37.5    7.27
    37.5    5.81    40.5    4.61    47.5    4.21    50.5    4.01    51.5    3.66
      52    3.56      55    3.56    57.5    3.56      58    3.66      59    4.06
    61.5    4.36    68.5    4.51      71    5.95      71    7.27      72    7.27
      72    8.07      75    8.07   116.5    7.83
#Mann= 3 , 0 , 0
       0     .03       0    36.5     .03       0      72     .03       0
Levee=-1,36.5,9,-1,72,9,,
Bank Sta=36.5,72
Exp/Cntr=0.5,0.3

Type RM Length L Ch R = 3 ,69.395  ,,,
BEGIN DESCRIPTION:
È­Á¤3±³
END DESCRIPTION:
Bridge Culvert--1,0,-1,-1, 0
Deck Dist Width WeirC Skew NumUp NumDn MinLoCord MaxHiCord MaxSubmerge Is_Ogee
0.1,34,1.44,0, 2, 2, , , 0.95, 0, 0,0,,
    36.5      72
    8.07    8.07
    7.27    7.27
    36.5      72
    8.07    8.07
    7.27    7.27
Pier Skew, UpSta & Num, DnSta & Num=  ,47.5, 2 ,47.5, 2 , 0 , 0 , 0 ,,
      .6      .6
     3.5       8
      .6      .6
     3.5       8
Pier Skew, UpSta & Num, DnSta & Num=  ,61.5, 2 ,61.5, 2 , 0 , 0 , 0 ,,
      .6      .6
     3.5       8
      .6      .6
     3.5       8
BR Coef=-1 , 0 , 0 ,, 0 ,,,0.8,-1,,0,
WSPro=,,,, 1 ,,,, 0 ,,,, 0 ,,,,-1 ,-1 ,-1 , 0 , 0 , 0 , 0 , 0
BC Design=,, 0 ,, 0 ,,,,,,

Type RM Length L Ch R = 1 ,69.22   ,22,22,22
#Sta/Elev= 23
       0    8.22      15    8.07    36.5    8.07    36.5    7.27    37.5    7.27
    37.5    5.81    40.5    4.61    47.5    4.21    50.5    4.01    51.5    3.66
      52    3.56      55    3.56    57.5    3.56      58    3.66      59    4.06
    61.5    4.36    68.5    4.51      71    5.95      71    7.27      72    7.27
      72    8.07      75    8.07   116.5    7.83
#Mann= 3 , 0 , 0
       0     .03       0    36.5     .03       0      72     .03       0
Levee=-1,36.5,9,-1,72,9,,
Bank Sta=36.5,72
Exp/Cntr=0.5,0.3

Type RM Length L Ch R = 1 ,69      ,50,50,50
#Sta/Elev= 29
       0    7.83      30    7.83    32.9    7.73    32.9    7.53    39.2    7.64
    46.9    7.57    46.9    7.77    49.9    7.77    49.9    7.42    55.6    4.99
    62.7    4.37    63.9    3.89    70.7    3.65    71.2     3.5    71.7     3.5
    73.5    3.94      85    3.75      85     4.1    86.7     4.1    86.7     6.5
    89.8    7.84    92.8    7.84    92.8    7.64    93.3    7.64    99.7    7.76
   106.7    7.69   106.7    7.89   109.7    7.95   139.7    7.95
#Mann= 3 , 0 , 0
       0     .03       0    49.9     .03       0    89.8     .03       0
Levee=-1,49.9,9,-1,89.8,9,,
Bank Sta=49.9,89.8
Exp/Cntr=0.3,0.1

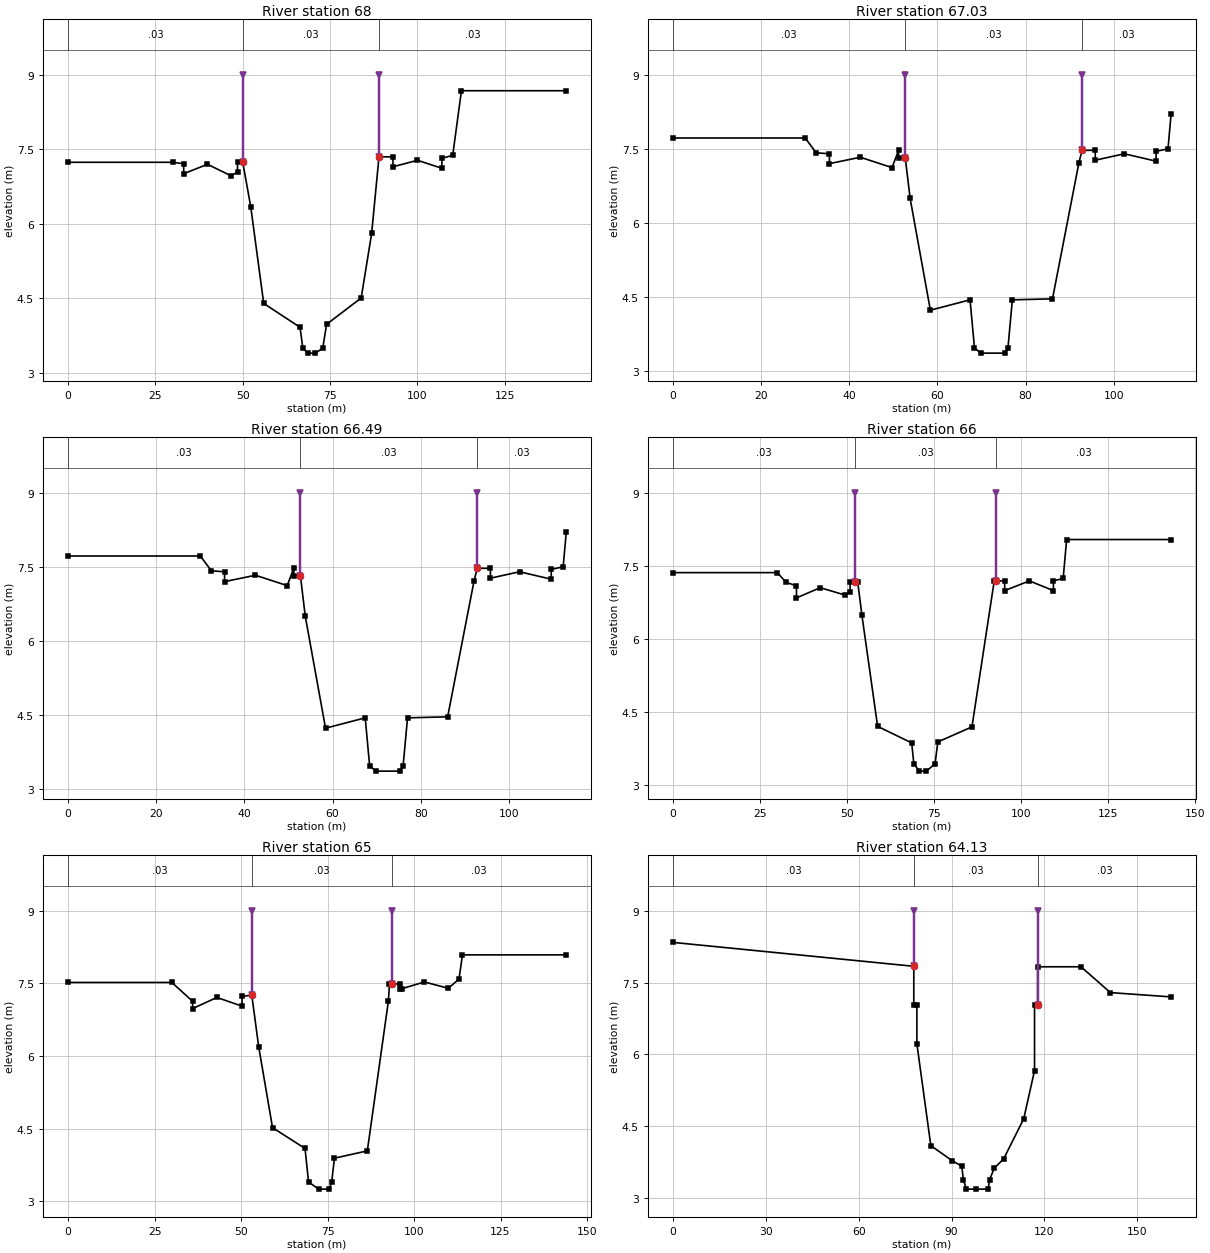
Type RM Length L Ch R = 1 ,68      ,47,47,47
#Sta/Elev= 28
       0    7.24      30    7.24    33.1    7.21    33.1    7.01    39.9     7.2
    46.6    6.97    48.5    7.04    48.5    7.24      50    7.24    52.3    6.34
      56     4.4    66.4    3.92    67.2     3.5    68.6     3.4    70.8     3.4
    72.9     3.5      74    3.98    83.9    4.51    86.9    5.81      89    7.35
      93    7.35      93    7.15     100    7.28     107    7.12     107    7.32
   110.1    7.38   112.6    8.68   142.6    8.68
#Mann= 3 , 0 , 0
       0     .03       0      50     .03       0      89     .03       0
Levee=-1,50,9,-1,89,9,,
Bank Sta=50,89
Exp/Cntr=0.3,0.1

Type RM Length L Ch R = 1 ,67.03   ,4,4,4
#Sta/Elev= 28
       0    7.72      30    7.72    32.5    7.42    35.5     7.4    35.5     7.2
    42.5    7.33    49.7    7.12    51.2    7.47    51.2    7.32    52.7    7.32
    53.8     6.5    58.4    4.23    67.4    4.44    68.4    3.47    69.8    3.36
    75.3    3.36      76    3.47      77    4.44    86.1    4.46    92.1    7.22
    92.8    7.47    95.8    7.47    95.8    7.27   102.4     7.4   109.6    7.25
   109.6    7.45   112.3     7.5     113     8.2
#Mann= 3 , 0 , 0
       0     .03       0    52.7     .03       0    92.8     .03       0
Levee=-1,52.7,9,-1,92.8,9,,
Bank Sta=52.7,92.8
Exp/Cntr=0.3,0.1

Type RM Length L Ch R = 1 ,66.49   ,49,49,49
#Sta/Elev= 28
       0    7.72      30    7.72    32.5    7.42    35.5     7.4    35.5     7.2
    42.5    7.33    49.7    7.12    51.2    7.47    51.2    7.32    52.7    7.32
    53.8     6.5    58.4    4.23    67.4    4.44    68.4    3.47    69.8    3.36
    75.3    3.36      76    3.47      77    4.44    86.1    4.46    92.1    7.22
    92.8    7.47    95.8    7.47    95.8    7.27   102.4     7.4   109.6    7.25
   109.6    7.45   112.3     7.5     113     8.2
#Mann= 3 , 0 , 0
       0     .03       0    52.7     .03       0    92.8     .03       0
Levee=-1,52.7,9,-1,92.8,9,,
Bank Sta=52.7,92.8
Exp/Cntr=0.3,0.1

Type RM Length L Ch R = 1 ,66      ,50,50,50
#Sta/Elev= 30
       0    7.36      30    7.36    32.5    7.16    35.5    7.09    35.5    6.84
    42.3    7.05    49.4     6.9    50.9    6.96    50.9    7.16    52.4    7.16
    53.1    7.16    54.3    6.48    58.8     4.2    68.6    3.86    69.2    3.43
    70.8    3.28    72.8    3.28    75.3    3.43    76.1    3.88    85.9    4.19
    92.3    7.19    92.8    7.19    95.3    7.19    95.3    6.99   102.4    7.19
   109.3    6.99   109.3    7.19   112.1    7.24   113.1    8.04   143.1    8.04
#Mann= 3 , 0 , 0
       0     .03       0    52.4     .03       0    92.8     .03       0
Levee=-1,52.4,9,-1,92.8,9,,
Bank Sta=52.4,92.8
Exp/Cntr=0.3,0.1

Type RM Length L Ch R = 1 ,65      ,37,37,37
#Sta/Elev= 28
       0    7.52      30    7.52      36    7.13      36    6.98      43    7.21
    50.3    7.03    50.3    7.23    53.1    7.26    55.1    6.19    59.1    4.52
    68.5    4.09    69.5     3.4    72.4    3.25    75.5    3.25    76.2     3.4
      77    3.89    86.5    4.04    92.6    7.14    92.9    7.49    93.6    7.49
    95.9    7.49    95.9    7.39    96.4    7.39     103    7.53   109.9     7.4
     113    7.59     114    8.09     144    8.09
#Mann= 3 , 0 , 0
       0     .03       0    53.1     .03       0    93.6     .03       0
Levee=-1,53.1,9,-1,93.6,9,,
Bank Sta=53.1,93.6
Exp/Cntr=0.3,0.1

Type RM Length L Ch R = 1 ,64.13   ,20,20,20
#Sta/Elev= 23
       0    8.34    77.8    7.84    77.8    7.04    78.8    7.04    78.8    6.22
    83.3    4.09    90.3    3.77    93.3    3.66    93.8    3.38    94.8    3.18
    97.8    3.18   101.8    3.18   102.3    3.38   103.8    3.62   106.8    3.81
   113.3    4.65   116.8    5.66   116.8    7.03   117.8    7.03   117.8    7.83
   131.8    7.83   141.3    7.29   160.9     7.2
#Mann= 3 , 0 , 0
       0     .03       0    77.8     .03       0   117.8     .03       0
Levee=-1,77.8,9,-1,117.8,9,,
Bank Sta=77.8,117.8
Exp/Cntr=0.5,0.3

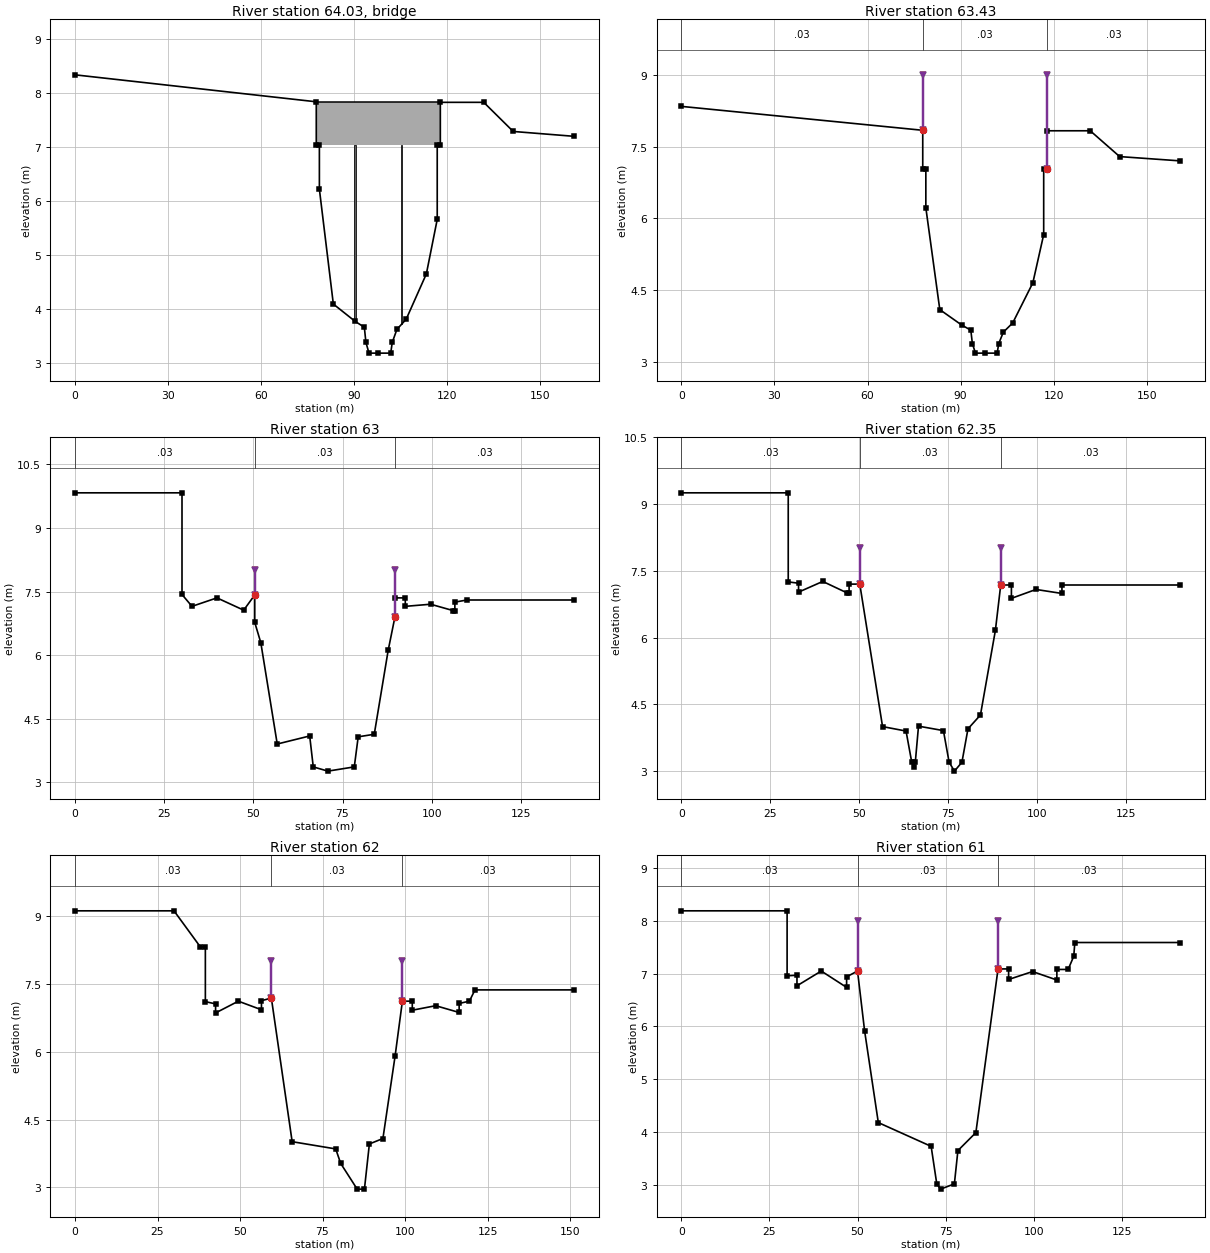
Type RM Length L Ch R = 3 ,64.03   ,,,
BEGIN DESCRIPTION:
È­Á¤2±³
END DESCRIPTION:
Bridge Culvert--1,0,-1,-1, 0
Deck Dist Width WeirC Skew NumUp NumDn MinLoCord MaxHiCord MaxSubmerge Is_Ogee
0.1,19,1.44,0, 2, 2, , , 0.95, 0, 0,0,,
    77.8   117.8
    7.84    7.84
    7.04    7.04
    77.8   117.8
    7.84    7.84
    7.04    7.04
Pier Skew, UpSta & Num, DnSta & Num=  ,90.3, 2 ,90.3, 2 , 0 , 0 , 0 ,,
      .6      .6
       3     8.7
      .6      .6
       3     8.7
Pier Skew, UpSta & Num, DnSta & Num=  ,105.3, 2 ,105.3, 2 , 0 , 0 , 0 ,,
      .6      .6
       3     8.7
      .6      .6
       3     8.7
BR Coef=-1 , 0 , 0 ,, 0 ,,,0.8,-1,,0,
WSPro=,,,, 1 ,,,, 0 ,,,, 0 ,,,,-1 ,-1 ,-1 , 0 , 0 , 0 , 0 , 0
BC Design=,, 0 ,, 0 ,,,,,,

Type RM Length L Ch R = 1 ,63.43   ,43,43,43
#Sta/Elev= 23
       0    8.34    77.8    7.84    77.8    7.04    78.8    7.04    78.8    6.22
    83.3    4.09    90.3    3.77    93.3    3.66    93.8    3.38    94.8    3.18
    97.8    3.18   101.8    3.18   102.3    3.38   103.8    3.62   106.8    3.81
   113.3    4.65   116.8    5.66   116.8    7.03   117.8    7.03   117.8    7.83
   131.8    7.83   141.3    7.29   160.9     7.2
#Mann= 3 , 0 , 0
       0     .03       0    77.8     .03       0   117.8     .03       0
Levee=-1,77.8,9,-1,117.8,9,,
Bank Sta=77.8,117.8
Exp/Cntr=0.5,0.3

Type RM Length L Ch R = 1 ,63      ,15,15,15
#Sta/Elev= 27
       0    9.83      30    9.83      30    7.43    32.8    7.15    39.8    7.35
    47.3    7.06    50.4    7.42    50.4    6.77    52.1    6.29    56.7     3.9
    65.8    4.09    66.8    3.36    70.9    3.26    78.3    3.36    79.4    4.07
    83.9    4.13    87.8    6.11    89.7     6.9    89.7    7.35    92.6    7.35
    92.6    7.15    99.7     7.2     106    7.05   106.5    7.05   106.5    7.25
   109.9     7.3   139.9     7.3
#Mann= 3 , 0 , 0
       0     .03       0    50.4     .03       0    89.7     .03       0
Levee=-1,50.4,8,-1,89.7,8,,
Bank Sta=50.4,89.7
Exp/Cntr=0.3,0.1

Type RM Length L Ch R = 1 ,62.35   ,35,35,35
#Sta/Elev= 30
       0    9.25      30    9.25      30    7.25    32.9    7.22    32.9    7.02
    39.7    7.26    46.6       7    47.1       7    47.1     7.2    50.1     7.2
    56.5       4    63.1     3.9    64.7     3.2    65.2     3.1    65.7     3.2
    66.6    4.01    73.6    3.91    75.2     3.2    76.7       3    78.8     3.2
    80.5    3.95      84    4.26    88.2    6.16    89.7    7.18    92.7    7.18
    92.7    6.88    99.6    7.08   106.9    6.99   106.9    7.18   140.2    7.18
#Mann= 3 , 0 , 0
       0     .03       0    50.1     .03       0    89.7     .03       0
Levee=-1,50.1,8,-1,89.7,8,,
Bank Sta=50.1,89.7
Exp/Cntr=0.3,0.1

Type RM Length L Ch R = 1 ,62      ,50,50,50
#Sta/Elev= 28
       0    9.12      30    9.12      38    8.32    39.5    8.32    39.5    7.11
    42.6    7.06    42.6    6.86    49.5    7.12    56.5    6.93    56.5    7.13
    59.5    7.19    65.8    4.01      79    3.85    80.5    3.53    85.5    2.96
    87.7    2.96    89.2    3.96    93.3    4.08      97    5.91    99.2    7.12
   102.2    7.12   102.2    6.92   109.3    7.02   116.4    6.87   116.4    7.07
   119.5    7.12   121.2    7.37   151.2    7.37
#Mann= 3 , 0 , 0
       0     .03       0    59.5     .03       0    99.2     .03       0
Levee=-1,59.5,8,-1,99.2,8,,
Bank Sta=59.5,99.2
Exp/Cntr=0.3,0.1

Type RM Length L Ch R = 1 ,61      ,37,37,37
#Sta/Elev= 27
       0    8.19      30    8.19      30    6.96    32.8    6.97    32.8    6.77
    39.7    7.05    46.9    6.74    46.9    6.94      50    7.05      52    5.92
    55.9    4.18    70.9    3.73    72.5    3.02    73.6    2.92    77.5    3.02
    78.5    3.65    83.6    3.99    89.9    7.09    92.9    7.09    92.9    6.89
    99.7    7.04   106.6    6.88   106.6    7.08   109.8    7.08   111.4    7.33
   111.7    7.59   141.7    7.59
#Mann= 3 , 0 , 0
       0     .03       0      50     .03       0    89.9     .03       0
Levee=-1,50,8,-1,89.9,8,,
Bank Sta=50,89.9
Exp/Cntr=0.3,0.1

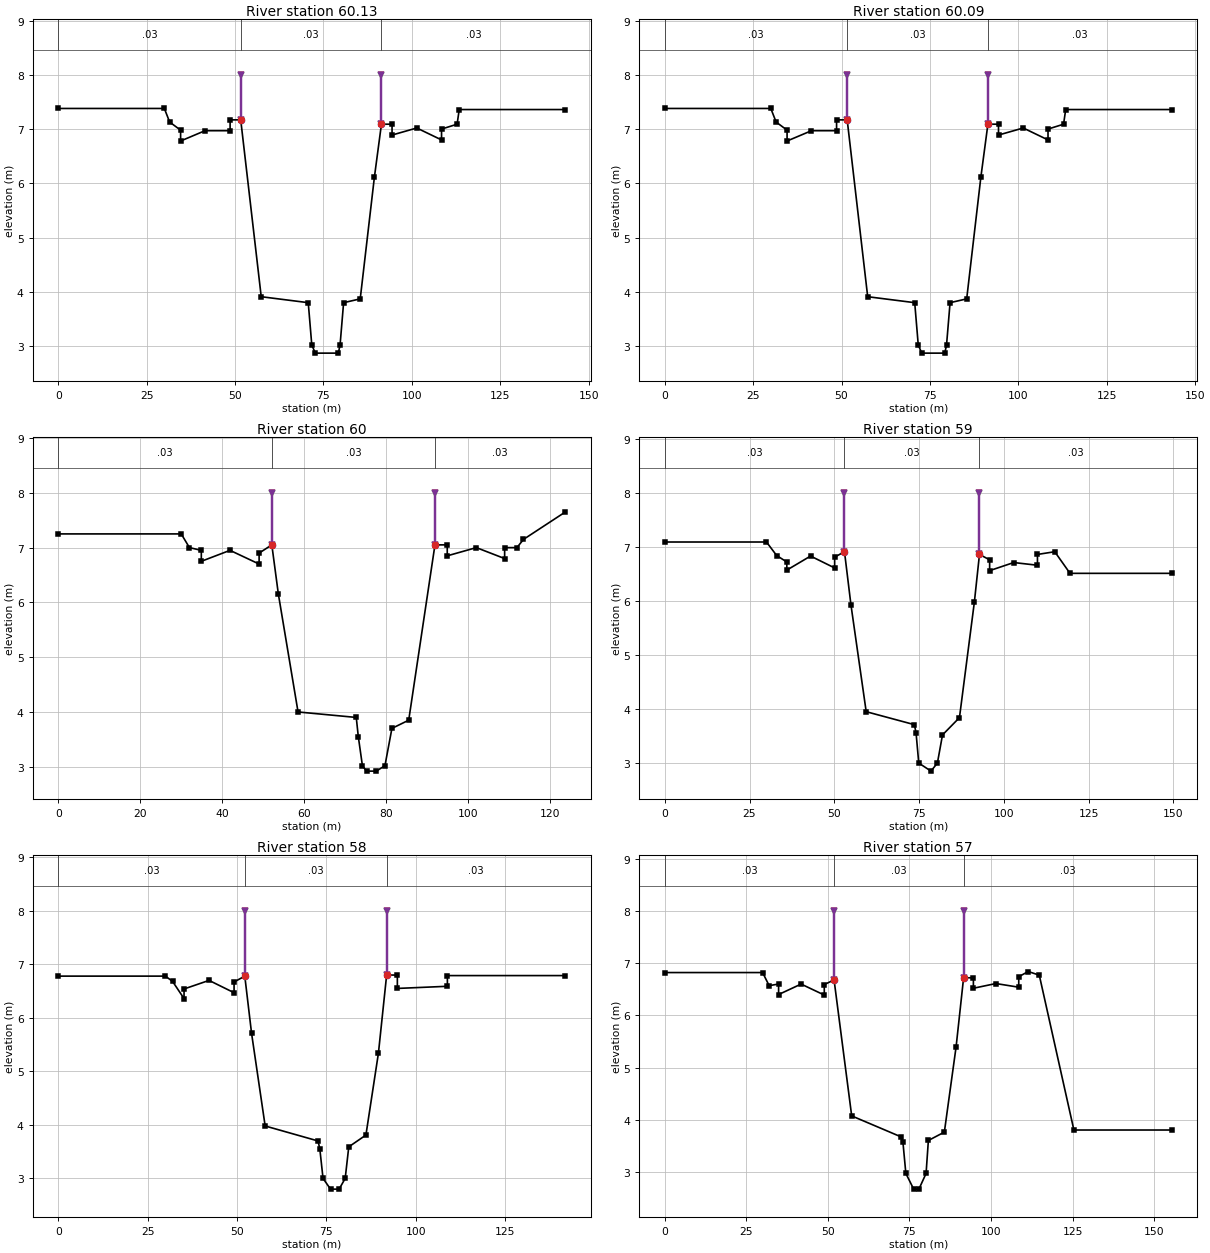
Type RM Length L Ch R = 1 ,60.13   ,4,4,4
#Sta/Elev= 27
       0    7.38      30    7.38    31.5    7.13    34.6    6.98    34.6    6.78
    41.5    6.97    48.6    6.97    48.6    7.17    51.6    7.17    57.4    3.91
    70.7     3.8    71.7    3.02    72.7    2.87    79.2    2.87    79.7    3.02
    80.7     3.8    85.4    3.87    89.4    6.11    91.4    7.09    94.4    7.09
    94.4    6.89   101.4    7.02   108.4     6.8   108.4       7   112.8    7.09
   113.4    7.36   143.4    7.36
#Mann= 3 , 0 , 0
       0     .03       0    51.6     .03       0    91.4     .03       0
Levee=-1,51.6,8,-1,91.4,8,,
Bank Sta=51.6,91.4
Exp/Cntr=0.3,0.1

Type RM Length L Ch R = 1 ,60.09   ,9,9,9
#Sta/Elev= 27
       0    7.38      30    7.38    31.5    7.13    34.6    6.98    34.6    6.78
    41.5    6.97    48.6    6.97    48.6    7.17    51.6    7.17    57.4    3.91
    70.7     3.8    71.7    3.02    72.7    2.87    79.2    2.87    79.7    3.02
    80.7     3.8    85.4    3.87    89.4    6.11    91.4    7.09    94.4    7.09
    94.4    6.89   101.4    7.02   108.4     6.8   108.4       7   112.8    7.09
   113.4    7.36   143.4    7.36
#Mann= 3 , 0 , 0
       0     .03       0    51.6     .03       0    91.4     .03       0
Levee=-1,51.6,8,-1,91.4,8,,
Bank Sta=51.6,91.4
Exp/Cntr=0.3,0.1

Type RM Length L Ch R = 1 ,60      ,50,50,50
#Sta/Elev= 28
       0    7.25      30    7.25      32       7    34.9    6.95    34.9    6.75
    41.9    6.95      49     6.7      49     6.9    52.1    7.05    53.7    6.15
    58.5       4    72.7     3.9    73.2    3.55    74.2    3.02    75.2    2.92
    77.6    2.92    79.7    3.02    81.4     3.7    85.5    3.85    91.9    7.05
    94.9    7.05    94.9    6.85     102       7   108.9     6.8   108.9       7
   111.9       7   113.5    7.15   123.7    7.65
#Mann= 3 , 0 , 0
       0     .03       0    52.1     .03       0    91.9     .03       0
Levee=-1,52.1,8,-1,91.9,8,,
Bank Sta=52.1,91.9
Exp/Cntr=0.3,0.1

Type RM Length L Ch R = 1 ,59      ,50,50,50
#Sta/Elev= 28
       0    7.09      30    7.09      33    6.84      36    6.72      36    6.57
      43    6.83    50.1    6.61    50.1    6.81      53    6.91    54.9    5.93
    59.4    3.95    73.6    3.71    74.1    3.56    74.9       3    78.5    2.85
    80.4       3    81.9    3.52    86.9    3.84    91.3    5.98    92.8    6.86
    95.8    6.76    95.8    6.56   102.9    6.71   109.9    6.66   109.9    6.86
     115    6.91   119.5    6.51   149.5    6.51
#Mann= 3 , 0 , 0
       0     .03       0      53     .03       0    92.8     .03       0
Levee=-1,53,8,-1,92.8,8,,
Bank Sta=53,92.8
Exp/Cntr=0.3,0.1

Type RM Length L Ch R = 1 ,58      ,50,50,50
#Sta/Elev= 26
       0    6.78      30    6.78      32    6.68    35.2    6.36    35.2    6.54
    42.2     6.7    49.2    6.47    49.2    6.67    52.2    6.78    54.1    5.71
    57.9    3.98    72.7     3.7    73.2    3.55    74.1       3    76.2     2.8
    78.6     2.8    80.3       3    81.3    3.59    86.1    3.81    89.6    5.34
    91.9     6.8    94.9     6.8    94.9    6.55   108.9    6.59   108.9    6.79
   141.9    6.79
#Mann= 3 , 0 , 0
       0     .03       0    52.2     .03       0    91.9     .03       0
Levee=-1,52.2,8,-1,91.9,8,,
Bank Sta=52.2,91.9
Exp/Cntr=0.3,0.1

Type RM Length L Ch R = 1 ,57      ,32,32,32
#Sta/Elev= 29
       0    6.82      30    6.82      32    6.57    34.9     6.6    34.9     6.4
    41.8     6.6    48.9    6.39    48.9    6.59    51.9    6.68    57.3    4.08
    72.4    3.68      73    3.58    73.9    2.98    76.3    2.68    77.9    2.68
    80.1    2.98    80.8    3.61    85.7    3.77    89.3     5.4    91.6    6.72
    94.6    6.72    94.6    6.52   101.5    6.61   108.5    6.54   108.5    6.74
   111.4    6.84   114.8    6.77   125.4    3.81   155.4    3.81
#Mann= 3 , 0 , 0
       0     .03       0    51.9     .03       0    91.6     .03       0
Levee=-1,51.9,8,-1,91.6,8,,
Bank Sta=51.9,91.6
Exp/Cntr=0.3,0.1

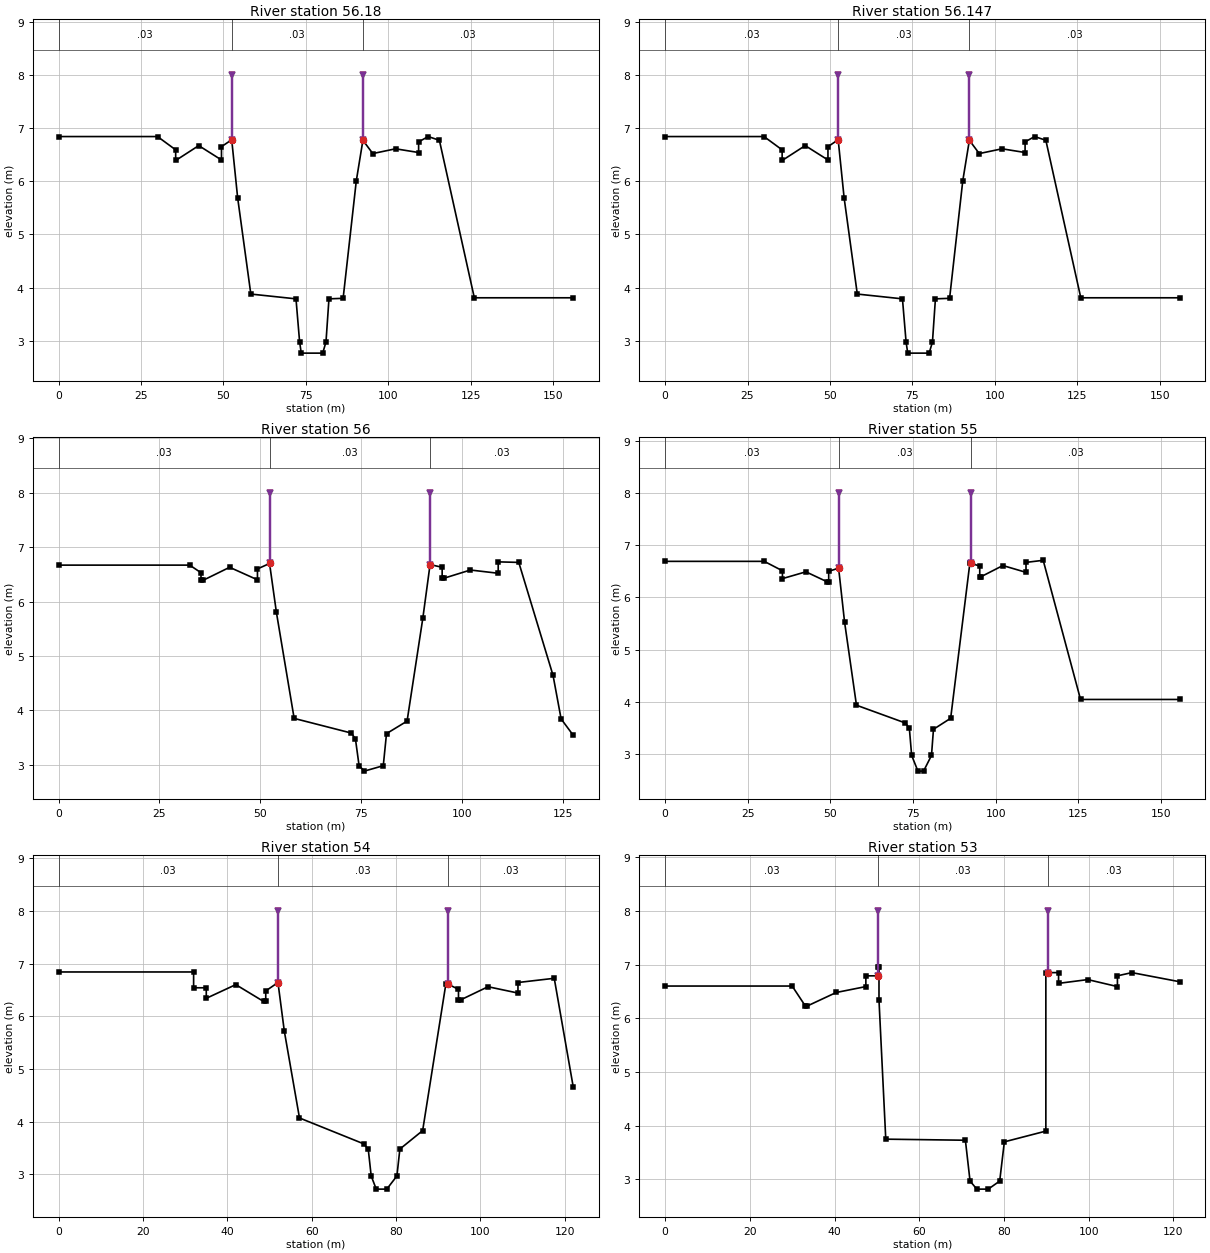
Type RM Length L Ch R = 1 ,56.18   ,3.3,3.3,3.3
#Sta/Elev= 27
       0    6.84      30    6.84    35.5    6.59    35.5    6.39    42.5    6.67
    49.4     6.4    49.4    6.65    52.5    6.78    54.3    5.69    58.3    3.88
      72    3.79    73.1    2.98    73.6    2.77    80.1    2.77    81.1    2.98
      82    3.79    86.3     3.8    90.3    6.01    92.3    6.77    95.3    6.52
   102.2    6.61   109.2    6.54   109.2    6.74   112.1    6.84   115.5    6.77
   126.1    3.81   156.1    3.81
#Mann= 3 , 0 , 0
       0     .03       0    52.5     .03       0    92.3     .03       0
Levee=-1,52.5,8,-1,92.3,8,,
Bank Sta=52.5,92.3
Exp/Cntr=0.3,0.1

Type RM Length L Ch R = 1 ,56.147  ,14.7,14.7,14.7
#Sta/Elev= 27
       0    6.84      30    6.84    35.5    6.59    35.5    6.39    42.5    6.67
    49.4     6.4    49.4    6.65    52.5    6.78    54.3    5.69    58.3    3.88
      72    3.79    73.1    2.98    73.6    2.77    80.1    2.77    81.1    2.98
      82    3.79    86.3     3.8    90.3    6.01    92.3    6.77    95.3    6.52
   102.2    6.61   109.2    6.54   109.2    6.74   112.1    6.84   115.5    6.77
   126.1    3.81   156.1    3.81
#Mann= 3 , 0 , 0
       0     .03       0    52.5     .03       0    92.3     .03       0
Levee=-1,52.5,8,-1,92.3,8,,
Bank Sta=52.5,92.3
Exp/Cntr=0.3,0.1

Type RM Length L Ch R = 1 ,56      ,50,50,50
#Sta/Elev= 30
       0    6.67    32.5    6.67    35.3    6.53    35.3    6.39    35.8    6.39
    42.4    6.63    49.3     6.4    49.3     6.6    52.3     6.7      54     5.8
    58.4    3.85    72.6    3.58    73.6    3.47    74.5    2.98    75.8    2.88
    80.5    2.98    81.3    3.57    86.4     3.8    90.3    5.69    92.1    6.68
    95.1    6.63    95.1    6.43    95.6    6.43   102.1    6.58     109    6.52
     109    6.73   114.1    6.72   122.6    4.64   124.6    3.84   127.6    3.54
#Mann= 3 , 0 , 0
       0     .03       0    52.3     .03       0    92.1     .03       0
Levee=-1,52.3,8,-1,92.1,8,,
Bank Sta=52.3,92.1
Exp/Cntr=0.3,0.1

Type RM Length L Ch R = 1 ,55      ,50,50,50
#Sta/Elev= 30
       0    6.69      30    6.69    35.5    6.51    35.5    6.36    42.6    6.49
      49     6.3    49.5     6.3    49.5     6.5    52.5    6.56    54.3    5.53
    57.9    3.94    72.7     3.6    73.9     3.5    74.6    2.98    76.5    2.68
    78.2    2.68    80.6    2.98    81.2    3.48    86.4    3.69    92.2    6.65
    92.7    6.65    95.2     6.6    95.2     6.4    95.7     6.4   102.2    6.61
   109.2    6.48   109.2    6.67   114.4    6.71   125.7    4.05   155.7    4.05
#Mann= 3 , 0 , 0
       0     .03       0    52.5     .03       0    92.7     .03       0
Levee=-1,52.5,8,-1,92.7,8,,
Bank Sta=52.5,92.7
Exp/Cntr=0.3,0.1

Type RM Length L Ch R = 1 ,54      ,50,50,50
#Sta/Elev= 30
       0    6.84      32    6.84      32    6.54      35    6.54      35    6.34
      42     6.6    48.6    6.28    49.1    6.28    49.1    6.48      52    6.64
    53.5    5.72    57.1    4.07    72.3    3.58    73.4    3.48    74.1    2.97
    75.3    2.72    77.8    2.72    80.2    2.97    80.9    3.48    86.3    3.83
    91.8    6.61    92.3    6.61    94.8    6.51    94.8    6.31    95.3    6.31
   101.8    6.56   108.9    6.44   108.9    6.64   117.5    6.72     122    4.66
#Mann= 3 , 0 , 0
       0     .03       0      52     .03       0    92.3     .03       0
Levee=-1,52,8,-1,92.3,8,,
Bank Sta=52,92.3
Exp/Cntr=0.3,0.1

Type RM Length L Ch R = 1 ,53      ,2.1,2.1,2.1
#Sta/Elev= 28
       0     6.6      30     6.6    33.1    6.23    33.6    6.23    40.4    6.48
    47.4    6.59    47.4    6.79    50.3    6.79    50.3    6.95    50.5    6.95
    50.5    6.34    52.1    3.75    70.9    3.73      72    2.97    73.6    2.82
    76.3    2.82      79    2.97    80.1     3.7    89.9     3.9    89.9    6.85
    90.4    6.85    92.9    6.85    92.9    6.65    99.8    6.72   106.8    6.59
   106.8    6.79   110.2    6.85   121.5    6.68
#Mann= 3 , 0 , 0
       0     .03       0    50.3     .03       0    90.4     .03       0
Levee=-1,50.3,8,-1,90.4,8,,
Bank Sta=50.3,90.4
Exp/Cntr=0.3,0.1

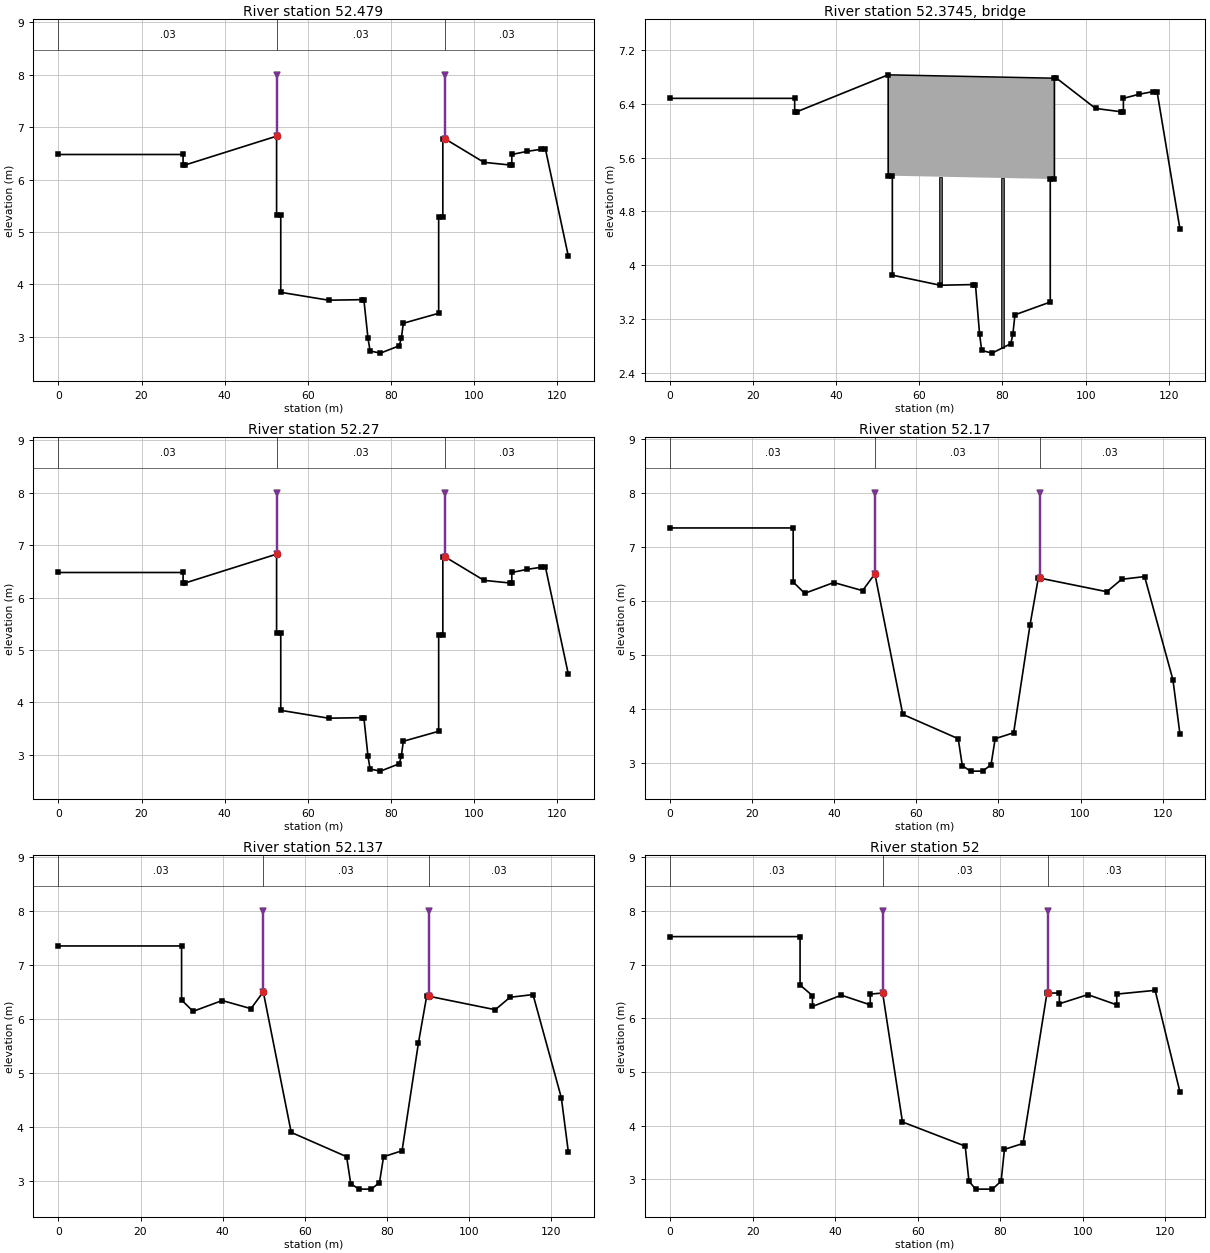
Type RM Length L Ch R = 1 ,52.479  ,20.9,20.9,20.9
#Sta/Elev= 30
       0    6.48      30    6.48      30    6.28    30.5    6.28    52.5    6.83
    52.5    5.33    53.5    5.33    53.5    3.85      65     3.7      73    3.71
    73.5    3.71    74.5    2.97      75    2.73    77.5    2.69      82    2.83
    82.5    2.97      83    3.26    91.5    3.45    91.5    5.28    92.5    5.28
    92.5    6.78      93    6.78   102.4    6.33   108.6    6.28   109.1    6.28
   109.1    6.48   112.8    6.54   116.2    6.58   117.2    6.58   122.7    4.54
#Mann= 3 , 0 , 0
       0     .03       0    52.5     .03       0      93     .03       0
Levee=-1,52.5,8,-1,93,8,,
Bank Sta=52.5,93
Exp/Cntr=0.5,0.3

Type RM Length L Ch R = 3 ,52.3745 ,,,
BEGIN DESCRIPTION:
È­¶û±³
END DESCRIPTION:
Bridge Culvert--1,0,-1,-1, 0
Deck Dist Width WeirC Skew NumUp NumDn MinLoCord MaxHiCord MaxSubmerge Is_Ogee
0.1,20,1.44,0, 2, 2, , , 0.95, 0, 0,0,,
    52.5    92.5
    6.83    6.78
    5.33    5.28
    52.5    92.5
    6.83    6.78
    5.33    5.28
Pier Skew, UpSta & Num, DnSta & Num=  ,65, 2 ,65, 2 , 0 , 0 , 0 ,,
      .7      .7
       2       7
      .7      .7
       2       7
Pier Skew, UpSta & Num, DnSta & Num=  ,80, 2 ,80, 2 , 0 , 0 , 0 ,,
      .7      .7
       2       7
      .7      .7
       2       7
BR Coef=-1 , 0 , 0 ,, 0 ,,,0.8,-1,,0,
WSPro=,,,, 1 ,,,, 0 ,,,, 0 ,,,,-1 ,-1 ,-1 , 0 , 0 , 0 , 0 , 0
BC Design=,, 0 ,, 0 ,,,,,,

Type RM Length L Ch R = 1 ,52.27   ,10,10,10
#Sta/Elev= 30
       0    6.48      30    6.48      30    6.28    30.5    6.28    52.5    6.83
    52.5    5.33    53.5    5.33    53.5    3.85      65     3.7      73    3.71
    73.5    3.71    74.5    2.97      75    2.73    77.5    2.69      82    2.83
    82.5    2.97      83    3.26    91.5    3.45    91.5    5.28    92.5    5.28
    92.5    6.78      93    6.78   102.4    6.33   108.6    6.28   109.1    6.28
   109.1    6.48   112.8    6.54   116.2    6.58   117.2    6.58   122.7    4.54
#Mann= 3 , 0 , 0
       0     .03       0    52.5     .03       0      93     .03       0
Levee=-1,52.5,8,-1,93,8,,
Bank Sta=52.5,93
Exp/Cntr=0.5,0.3

Type RM Length L Ch R = 1 ,52.17   ,3.3,3.3,3.3
#Sta/Elev= 23
       0    7.35      30    7.35      30    6.35    32.8    6.14    39.9    6.34
    46.9    6.19    49.9     6.5    56.7     3.9    70.2    3.45    71.2    2.95
    73.2    2.85    76.2    2.85    78.2    2.97    79.2    3.45    83.7    3.56
    87.7    5.56    89.7    6.42    90.2    6.42   106.4    6.17     110     6.4
   115.6    6.45   122.5    4.54   124.2    3.54
#Mann= 3 , 0 , 0
       0     .03       0    49.9     .03       0    90.2     .03       0
Levee=-1,49.9,8,-1,90.2,8,,
Bank Sta=49.9,90.2
Exp/Cntr=0.3,0.1

Type RM Length L Ch R = 1 ,52.137  ,13.7,13.7,13.7
#Sta/Elev= 23
       0    7.35      30    7.35      30    6.35    32.8    6.14    39.9    6.34
    46.9    6.19    49.9     6.5    56.7     3.9    70.2    3.45    71.2    2.95
    73.2    2.85    76.2    2.85    78.2    2.97    79.2    3.45    83.7    3.56
    87.7    5.56    89.7    6.42    90.2    6.42   106.4    6.17     110     6.4
   115.6    6.45   122.5    4.54   124.2    3.54
#Mann= 3 , 0 , 0
       0     .03       0    49.9     .03       0    90.2     .03       0
Levee=-1,49.9,8,-1,90.2,8,,
Bank Sta=49.9,90.2
Exp/Cntr=0.3,0.1

Type RM Length L Ch R = 1 ,52      ,31,31,31
#Sta/Elev= 26
       0    7.52    31.5    7.52    31.5    6.62    34.5    6.42    34.5    6.22
    41.5    6.43    48.5    6.25    48.5    6.45    51.5    6.47    56.3    4.07
    71.5    3.62    72.4    2.97      74    2.82    78.1    2.82    80.2    2.97
      81    3.56    85.5    3.67    91.3    6.47    91.5    6.47    94.3    6.47
    94.3    6.27   101.2    6.44   108.2    6.25   108.2    6.45   117.5    6.52
   123.5    4.63
#Mann= 3 , 0 , 0
       0     .03       0    51.5     .03       0    91.5     .03       0
Levee=-1,51.5,8,-1,91.5,8,,
Bank Sta=51.5,91.5
Exp/Cntr=0.3,0.1

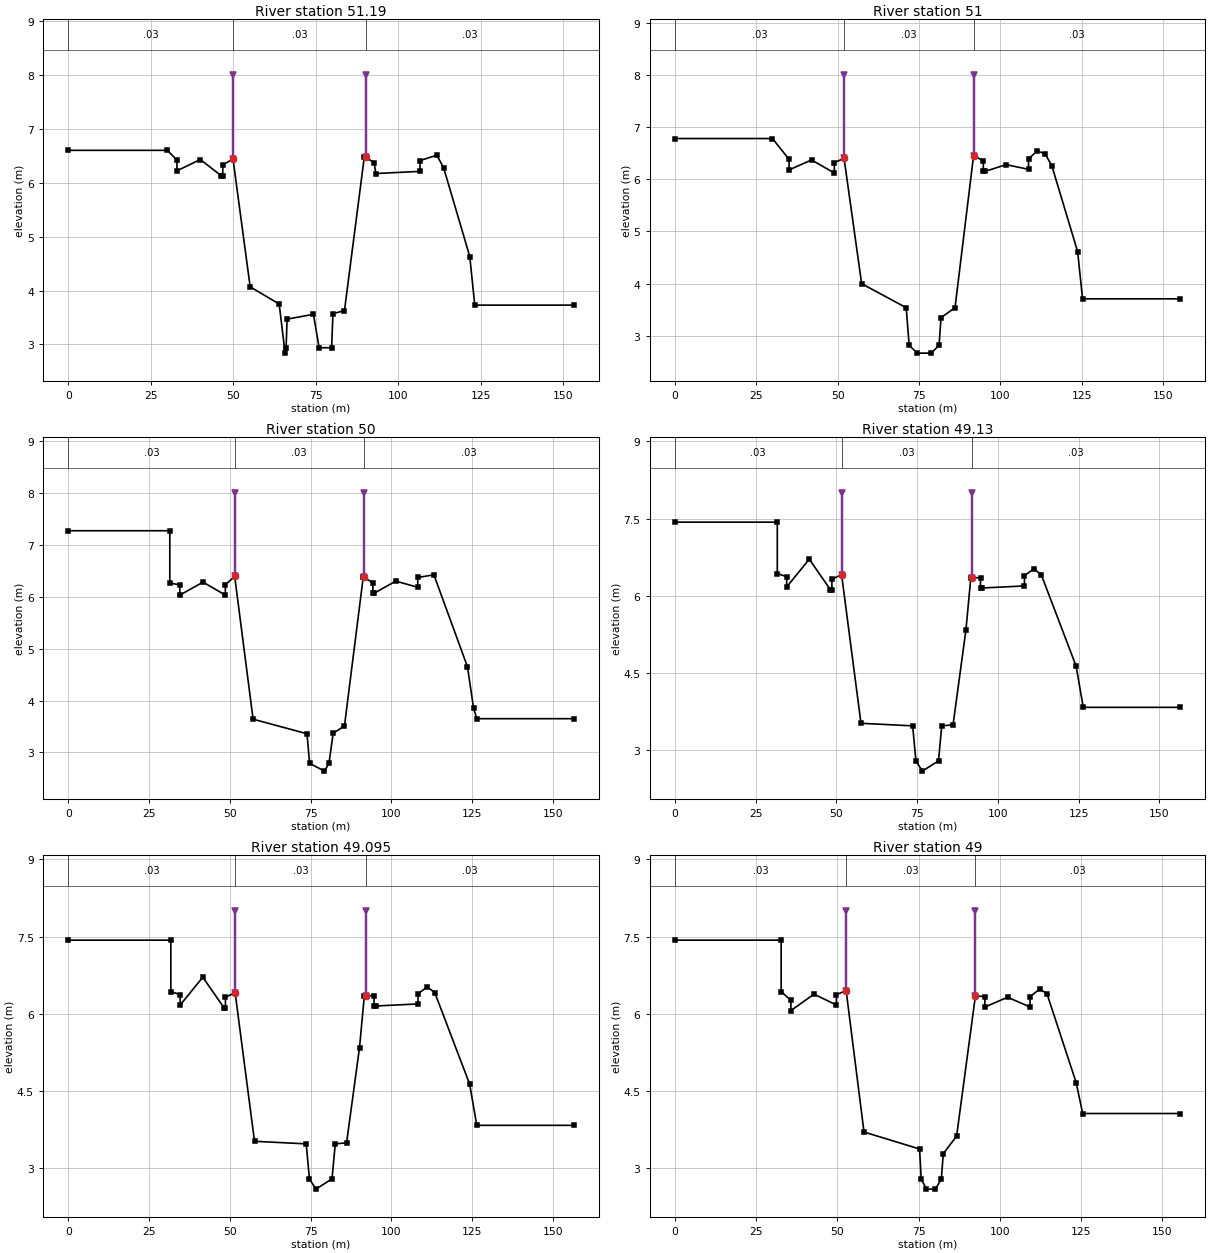
Type RM Length L Ch R = 1 ,51.19   ,19,19,19
#Sta/Elev= 30
       0     6.6      30     6.6    32.9    6.42    32.9    6.22      40    6.43
    46.3    6.13    46.8    6.13    46.8    6.33    49.9    6.44    55.1    4.07
    63.9    3.75    65.7    2.84      66    2.94    66.3    3.47    74.3    3.56
      76    2.94    79.8    2.94    80.2    3.57    83.7    3.63    89.7    6.47
    90.2    6.47    92.7    6.37    93.2    6.17   106.6    6.21   106.6    6.41
   111.7    6.51   113.8    6.27   121.7    4.63   123.2    3.73   153.2    3.73
#Mann= 3 , 0 , 0
       0     .03       0    49.9     .03       0    90.2     .03       0
Levee=-1,49.9,8,-1,90.2,8,,
Bank Sta=49.9,90.2
Exp/Cntr=0.3,0.1

Type RM Length L Ch R = 1 ,51      ,50,50,50
#Sta/Elev= 30
       0    6.78      30    6.78    35.1    6.38    35.1    6.18      42    6.37
      49    6.12      49    6.32      52     6.4    57.4       4    71.1    3.54
      72    2.82    74.5    2.67    78.8    2.67    81.2    2.82    81.8    3.35
    86.1    3.54    91.8    6.45      92    6.45    94.8    6.35    94.8    6.15
    95.3    6.15   101.8    6.28   108.7    6.19   108.7    6.39   111.3    6.54
   113.8    6.49   115.9    6.25   123.8    4.61   125.3    3.71   155.3    3.71
#Mann= 3 , 0 , 0
       0     .03       0      52     .03       0      92     .03       0
Levee=-1,52,8,-1,92,8,,
Bank Sta=52,92
Exp/Cntr=0.3,0.1

Type RM Length L Ch R = 1 ,50      ,37,37,37
#Sta/Elev= 29
       0    7.27    31.4    7.27    31.4    6.26    34.5    6.23    34.5    6.03
    41.7    6.28    48.6    6.03    48.6    6.23    51.5    6.39    57.2    3.64
    73.9    3.36    74.7    2.79    79.3    2.64    80.7    2.79      82    3.37
    85.5    3.51    91.3    6.37    91.5    6.37    94.3    6.27    94.3    6.07
    94.8    6.07   101.4     6.3   108.2    6.18   108.2    6.37   113.2    6.42
   123.6    4.65   125.5    3.85   126.5    3.65   156.5    3.65
#Mann= 3 , 0 , 0
       0     .03       0    51.5     .03       0    91.5     .03       0
Levee=-1,51.5,8,-1,91.5,8,,
Bank Sta=51.5,91.5
Exp/Cntr=0.3,0.1

Type RM Length L Ch R = 1 ,49.13   ,3.5,3.5,3.5
#Sta/Elev= 30
       0    7.43    31.7    7.43    31.7    6.43    34.6    6.37    34.6    6.17
    41.6    6.71    48.1    6.12    48.6    6.12    48.6    6.32    51.6    6.41
    57.6    3.52    73.6    3.47    74.6    2.79    76.6    2.59    81.6    2.79
    82.6    3.47    86.1    3.49    90.1    5.34    91.6    6.35    92.1    6.35
    94.6    6.35    94.6    6.15    95.1    6.15   108.2    6.19   108.2    6.39
   111.1    6.52   113.4    6.41   124.2    4.63   126.4    3.83   156.4    3.83
#Mann= 3 , 0 , 0
       0     .03       0    51.6     .03       0    92.1     .03       0
Levee=-1,51.6,8,-1,92.1,8,,
Bank Sta=51.6,92.1
Exp/Cntr=0.3,0.1

Type RM Length L Ch R = 1 ,49.095  ,9.5,9.5,9.5
#Sta/Elev= 30
       0    7.43    31.7    7.43    31.7    6.43    34.6    6.37    34.6    6.17
    41.6    6.71    48.1    6.12    48.6    6.12    48.6    6.32    51.6    6.41
    57.6    3.52    73.6    3.47    74.6    2.79    76.6    2.59    81.6    2.79
    82.6    3.47    86.1    3.49    90.1    5.34    91.6    6.35    92.1    6.35
    94.6    6.35    94.6    6.15    95.1    6.15   108.2    6.19   108.2    6.39
   111.1    6.52   113.4    6.41   124.2    4.63   126.4    3.83   156.4    3.83
#Mann= 3 , 0 , 0
       0     .03       0    51.6     .03       0    92.1     .03       0
Levee=-1,51.6,8,-1,92.1,8,,
Bank Sta=51.6,92.1
Exp/Cntr=0.3,0.1

Type RM Length L Ch R = 1 ,49      ,50,50,50
#Sta/Elev= 28
       0    7.43    32.7    7.43    32.7    6.43    35.7    6.26    35.7    6.06
    42.8    6.38    49.7    6.17    49.7    6.37    52.7    6.45    58.2     3.7
    75.3    3.37    75.8    2.79    77.4    2.59    80.2    2.59      82    2.79
    82.6    3.28    86.7    3.62    92.5    6.35    95.4    6.33    95.4    6.13
   102.4    6.32   109.3    6.13   109.3    6.33   112.3    6.48   114.5    6.39
   123.5    4.66   125.5    4.06   155.5    4.06
#Mann= 3 , 0 , 0
       0     .03       0    52.7     .03       0    92.5     .03       0
Levee=-1,52.7,8,-1,92.5,8,,
Bank Sta=52.7,92.5
Exp/Cntr=0.3,0.1