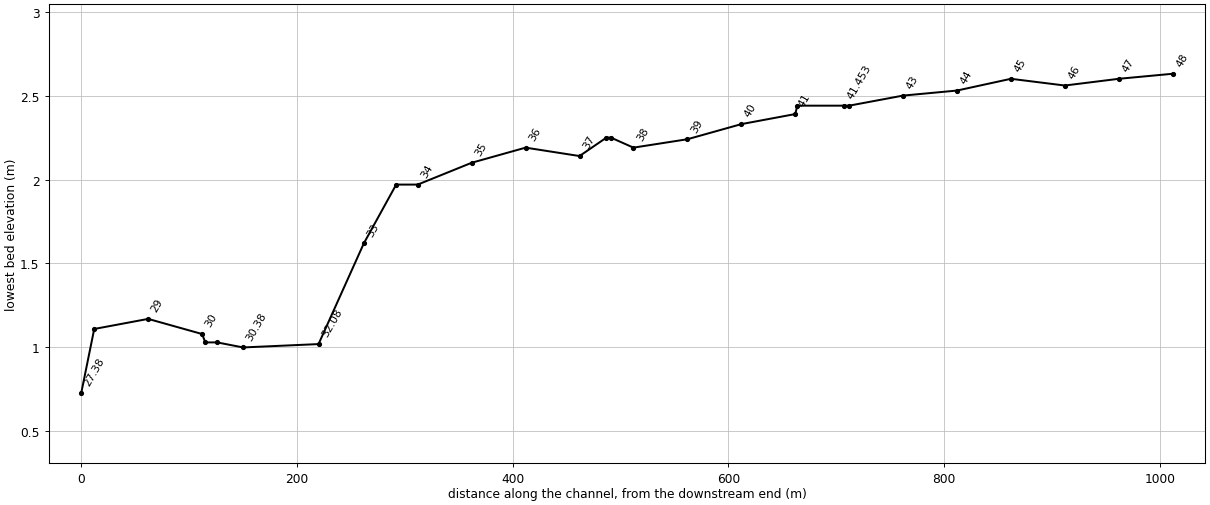
HEC-RAS study Hwajung.prj: Hwajung

--- Hwajung.g01 (geometry) --- (continued)

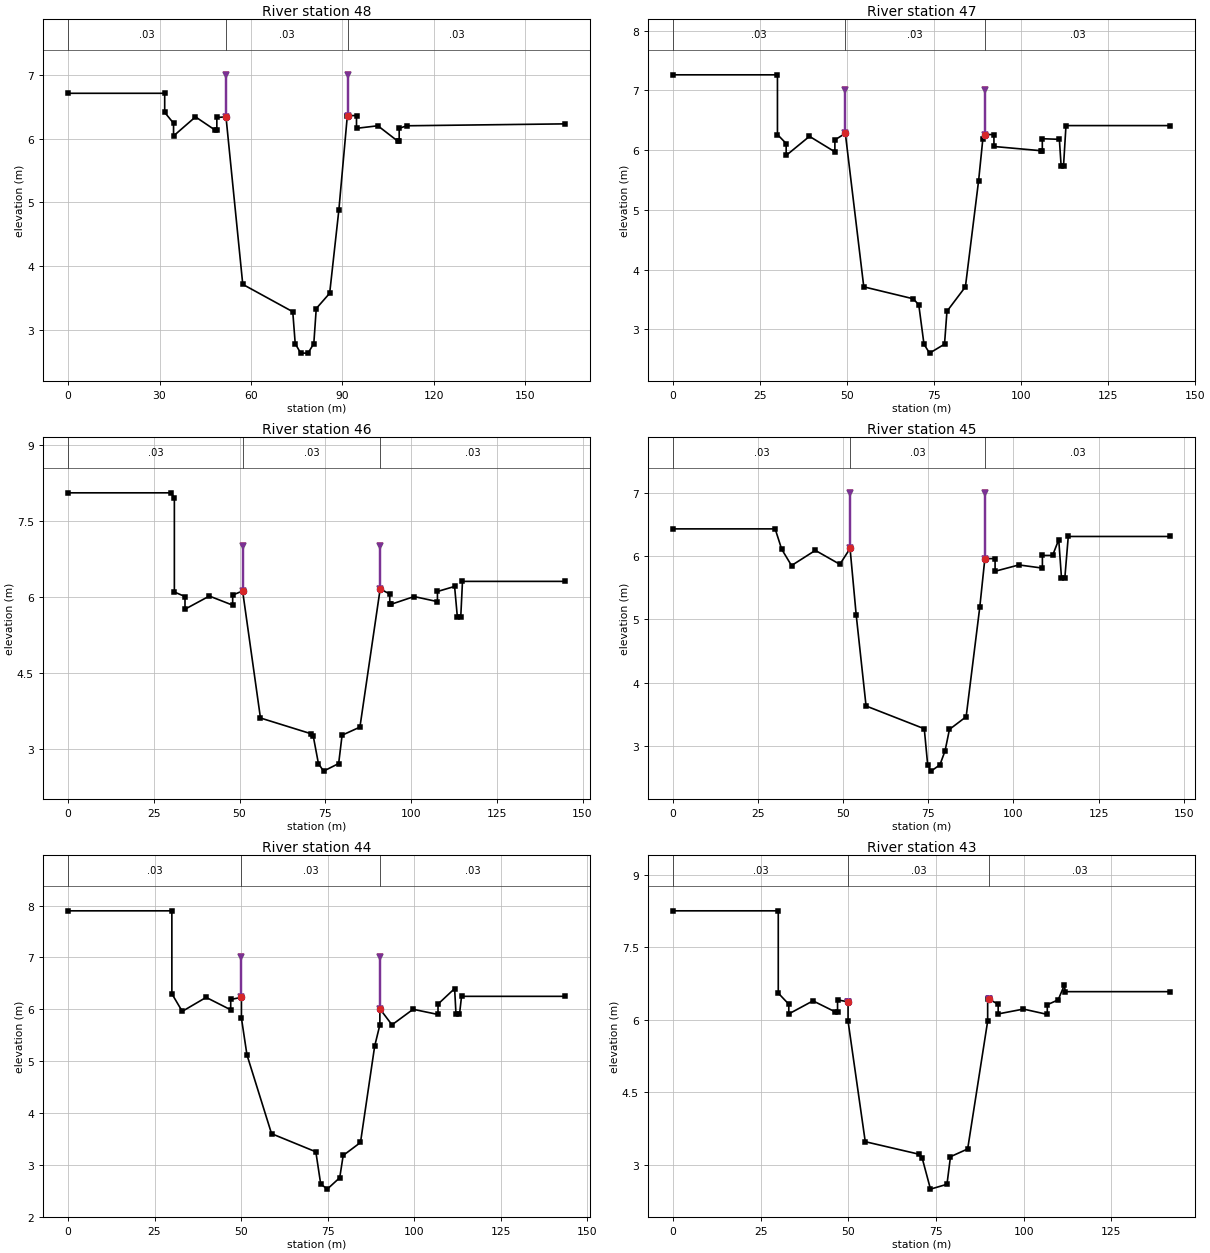
Type RM Length L Ch R = 1 ,48      ,50,50,50
#Sta/Elev= 29
       0    6.71    31.7    6.71    31.7    6.41    34.6    6.24    34.6    6.04
    41.8    6.34    48.3    6.13    48.8    6.13    48.8    6.33    51.8    6.34
    57.3    3.71    73.7    3.28    74.5    2.78    76.3    2.63    78.7    2.63
    80.6    2.78    81.4    3.33    85.8    3.57    88.8    4.87    91.6    6.36
    91.8    6.36    94.6    6.36    94.6    6.16   101.6     6.2   108.1    5.96
   108.6    5.96   108.6    6.16   111.1     6.2   163.1    6.23
#Mann= 3 , 0 , 0
       0     .03       0    51.8     .03       0    91.8     .03       0
Levee=-1,51.8,7,-1,91.8,7,,
Bank Sta=51.8,91.8
Exp/Cntr=0.3,0.1

Type RM Length L Ch R = 1 ,47      ,50,50,50
#Sta/Elev= 30
       0    7.26      30    7.26      30    6.26    32.5    6.11    32.5    5.91
    39.2    6.23    46.5    5.97    46.5    6.17    49.5    6.28    54.8    3.71
      69    3.51    70.6    3.41    72.1    2.75    73.7     2.6      78    2.75
    78.7     3.3      84    3.71    87.8    5.49      89    6.18    89.7    6.26
    92.2    6.26    92.2    6.06   105.6    5.99   106.1    5.99   106.1    6.19
     111    6.18   111.5    5.74   112.2    5.74   112.9    6.41   142.9    6.41
#Mann= 3 , 0 , 0
       0     .03       0    49.5     .03       0    89.7     .03       0
Levee=-1,49.5,7,-1,89.7,7,,
Bank Sta=49.5,89.7
Exp/Cntr=0.3,0.1

Type RM Length L Ch R = 1 ,46      ,50,50,50
#Sta/Elev= 30
       0    8.06      30    8.06      31    7.96      31     6.1    34.1    6.01
    34.1    5.76    41.2    6.02      48    5.84      48    6.04    50.9    6.12
    56.1    3.61    70.8     3.3    71.5    3.25      73    2.71    74.5    2.56
    78.9    2.71    79.9    3.27    85.1    3.43      91    6.16    93.8    6.06
    93.8    5.86    94.3    5.86   100.9    6.01   107.7    5.91   107.7    6.11
   112.7    6.21   113.5    5.61   114.5    5.61     115    6.31     145    6.31
#Mann= 3 , 0 , 0
       0     .03       0    50.9     .03       0      91     .03       0
Levee=-1,50.9,7,-1,91,7,,
Bank Sta=50.9,91
Exp/Cntr=0.3,0.1

Type RM Length L Ch R = 1 ,45      ,50,50,50
#Sta/Elev= 29
       0    6.43      30    6.43    31.9    6.11    34.8    5.85    41.8    6.09
      49    5.87      52    6.12    53.8    5.07    56.7    3.63    73.8    3.27
    74.8     2.7    75.8     2.6    78.4     2.7    79.9    2.92    81.2    3.26
    86.1    3.46    90.1    5.19    91.6    5.96    94.6    5.96    94.6    5.76
   101.6    5.86   108.5    5.81   108.5    6.01   111.5    6.01   113.3    6.26
   114.1    5.66   115.1    5.66   116.1    6.31   146.1    6.31
#Mann= 3 , 0 , 0
       0     .03       0      52     .03       0    91.6     .03       0
Levee=-1,52,7,-1,91.6,7,,
Bank Sta=52,91.6
Exp/Cntr=0.3,0.1

Type RM Length L Ch R = 1 ,44      ,50,50,50
#Sta/Elev= 30
       0     7.9      30     7.9      30     6.3      33    5.96    39.9    6.23
      47    5.99      47    6.19    50.1    6.23    50.1    5.83    51.7    5.12
    58.8     3.6    71.6    3.25      73    2.63    74.9    2.53    78.5    2.75
    79.5    3.18    84.5    3.43    88.6    5.29    90.1     5.7    90.1       6
    90.2       6    93.6     5.7    99.7       6   106.9     5.9   106.9     6.1
   111.7     6.4   112.1     5.9   113.1     5.9   113.7    6.25   143.7    6.25
#Mann= 3 , 0 , 0
       0     .03       0    50.1     .03       0    90.2     .03       0
Levee=-1,50.1,7,-1,90.2,7,,
Bank Sta=50.1,90.2
Exp/Cntr=0.3,0.1

Type RM Length L Ch R = 1 ,43      ,50,50,50
#Sta/Elev= 30
       0    8.25      30    8.25      30    6.55      33    6.32      33    6.12
    39.9    6.39    46.3    6.16    46.9    6.16    46.9    6.41    49.9    6.37
    49.9    5.97    54.8    3.48    70.2    3.22      71    3.15    73.4     2.5
    78.1     2.6    79.1    3.17      84    3.33    89.7    5.97    89.7    6.42
    90.2    6.42    92.7    6.32    92.7    6.12    99.9    6.22   106.7    6.11
   106.7    6.31   109.8    6.41   111.6    6.72   111.8    6.58   141.8    6.58
#Mann= 3 , 0 , 0
       0     .03       0    49.9     .03       0    90.2     .03       0
Levee=-1,49.9,6.37,-1,90.2,6.42,,
Bank Sta=49.9,90.2
Exp/Cntr=0.3,0.1

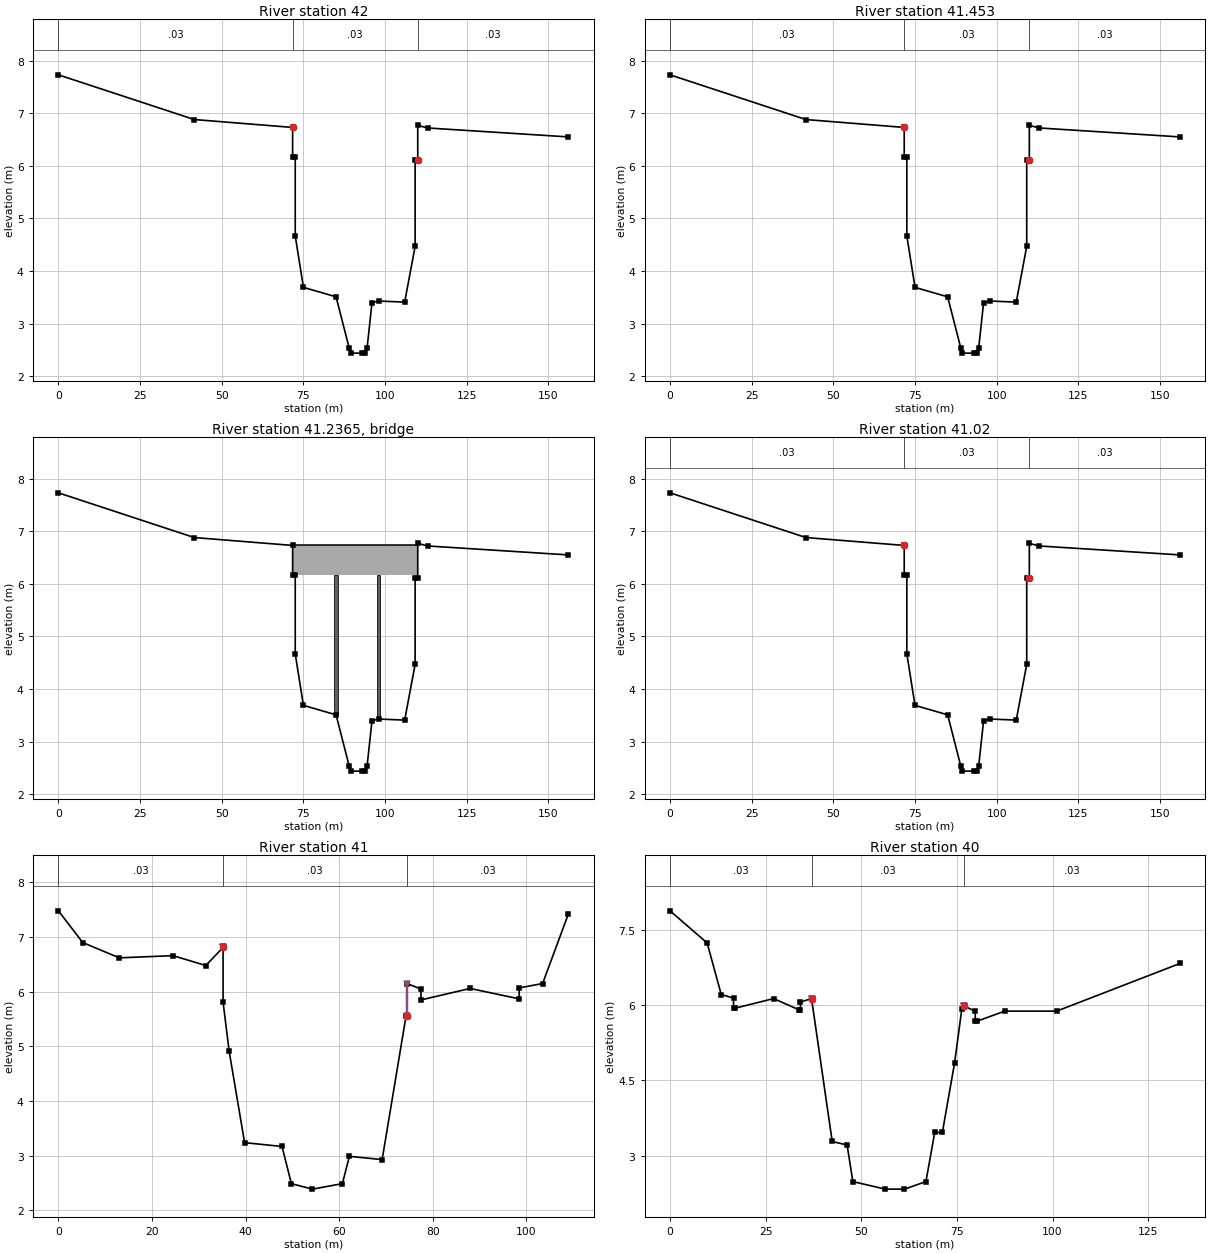
Type RM Length L Ch R = 1 ,42      ,4.7,4.7,4.7
#Sta/Elev= 22
       0    7.73    41.6    6.88    71.7    6.73    71.7    6.17    72.5    6.17
    72.5    4.67      75    3.69      85    3.51      89    2.54    89.5    2.44
      93    2.44      94    2.45    94.5    2.54      96     3.4      98    3.43
     106    3.41   109.2    4.47   109.2    6.12     110    6.12     110    6.77
     113    6.72   156.1    6.55
#Mann= 3 , 0 , 0
       0     .03       0    71.7     .03       0     110     .03       0
Bank Sta=71.7,110
Exp/Cntr=0.3,0.1

Type RM Length L Ch R = 1 ,41.453  ,43.3,43.3,43.3
#Sta/Elev= 22
       0    7.73    41.6    6.88    71.7    6.73    71.7    6.17    72.5    6.17
    72.5    4.67      75    3.69      85    3.51      89    2.54    89.5    2.44
      93    2.44      94    2.45    94.5    2.54      96     3.4      98    3.43
     106    3.41   109.2    4.47   109.2    6.12     110    6.12     110    6.77
     113    6.72   156.1    6.55
#Mann= 3 , 0 , 0
       0     .03       0    71.7     .03       0     110     .03       0
Bank Sta=71.7,110
Exp/Cntr=0.5,0.3

Type RM Length L Ch R = 3 ,41.2365 ,,,
BEGIN DESCRIPTION:
È­Á¤1±³
END DESCRIPTION:
Bridge Culvert--1,0,-1,-1, 0
Deck Dist Width WeirC Skew NumUp NumDn MinLoCord MaxHiCord MaxSubmerge Is_Ogee
0.1,43,1.44,0, 2, 2, , , 0.95, 0, 0,0,,
    71.7     110
    6.73    6.73
    6.17    6.17
    71.7     110
    6.73    6.73
    6.17    6.17
Pier Skew, UpSta & Num, DnSta & Num=  ,85, 2 ,85, 2 , 0 , 0 , 0 ,,
       1       1
       2       7
       1       1
       2       7
Pier Skew, UpSta & Num, DnSta & Num=  ,98, 2 ,98, 2 , 0 , 0 , 0 ,,
       1       1
       2       7
       1       1
       2       7
BR Coef=-1 , 0 , 0 ,, 0 ,,,0.8,-1,,0,
WSPro=,,,, 1 ,,,, 0 ,,,, 0 ,,,,-1 ,-1 ,-1 , 0 , 0 , 0 , 0 , 0
BC Design=,, 0 ,, 0 ,,,,,,

Type RM Length L Ch R = 1 ,41.02   ,2,2,2
#Sta/Elev= 22
       0    7.73    41.6    6.88    71.7    6.73    71.7    6.17    72.5    6.17
    72.5    4.67      75    3.69      85    3.51      89    2.54    89.5    2.44
      93    2.44      94    2.45    94.5    2.54      96     3.4      98    3.43
     106    3.41   109.2    4.47   109.2    6.12     110    6.12     110    6.77
     113    6.72   156.1    6.55
#Mann= 3 , 0 , 0
       0     .03       0    71.7     .03       0     110     .03       0
Bank Sta=71.7,110
Exp/Cntr=0.5,0.3

Type RM Length L Ch R = 1 ,41      ,50,50,50
#Sta/Elev= 25
       0    7.48     5.2     6.9      13    6.62    24.5    6.66    31.5    6.48
    35.2    6.81    35.2    5.81    36.5    4.91    39.8    3.24    47.8    3.17
    49.8    2.49    54.3    2.39    60.7    2.49    62.2    2.99    69.2    2.93
    74.3    5.55    74.5    5.55    74.5    6.15    77.5    6.05    77.5    5.85
      88    6.06    98.5    5.87    98.5    6.07   103.5    6.15     109    7.42
#Mann= 3 , 0 , 0
       0     .03       0    35.2     .03       0    74.5     .03       0
Levee=-1,35.2,6.81,-1,74.5,6.15,,
Bank Sta=35.2,74.5
Exp/Cntr=0.3,0.1

Type RM Length L Ch R = 1 ,40      ,50,50,50
#Sta/Elev= 28
       0    7.88     9.7    7.24    13.4    6.21    16.6    6.14    16.6    5.94
    17.1    5.94    27.1    6.13    33.6    5.91    34.1    5.91    34.1    6.06
      37    6.13    42.4    3.28    46.3    3.21    47.8    2.48    56.3    2.33
    61.3    2.33    66.9    2.48    69.2    3.46    71.2    3.46    74.4    4.85
    76.3    5.93    76.8    5.98    79.8    5.88    79.8    5.68    80.3    5.68
    87.5    5.88   101.1    5.88   133.3    6.83
#Mann= 3 , 0 , 0
       0     .03       0      37     .03       0    76.8     .03       0
Levee=-1,37,6.13,-1,76.8,5.98,,
Bank Sta=37,76.8
Exp/Cntr=0.3,0.1

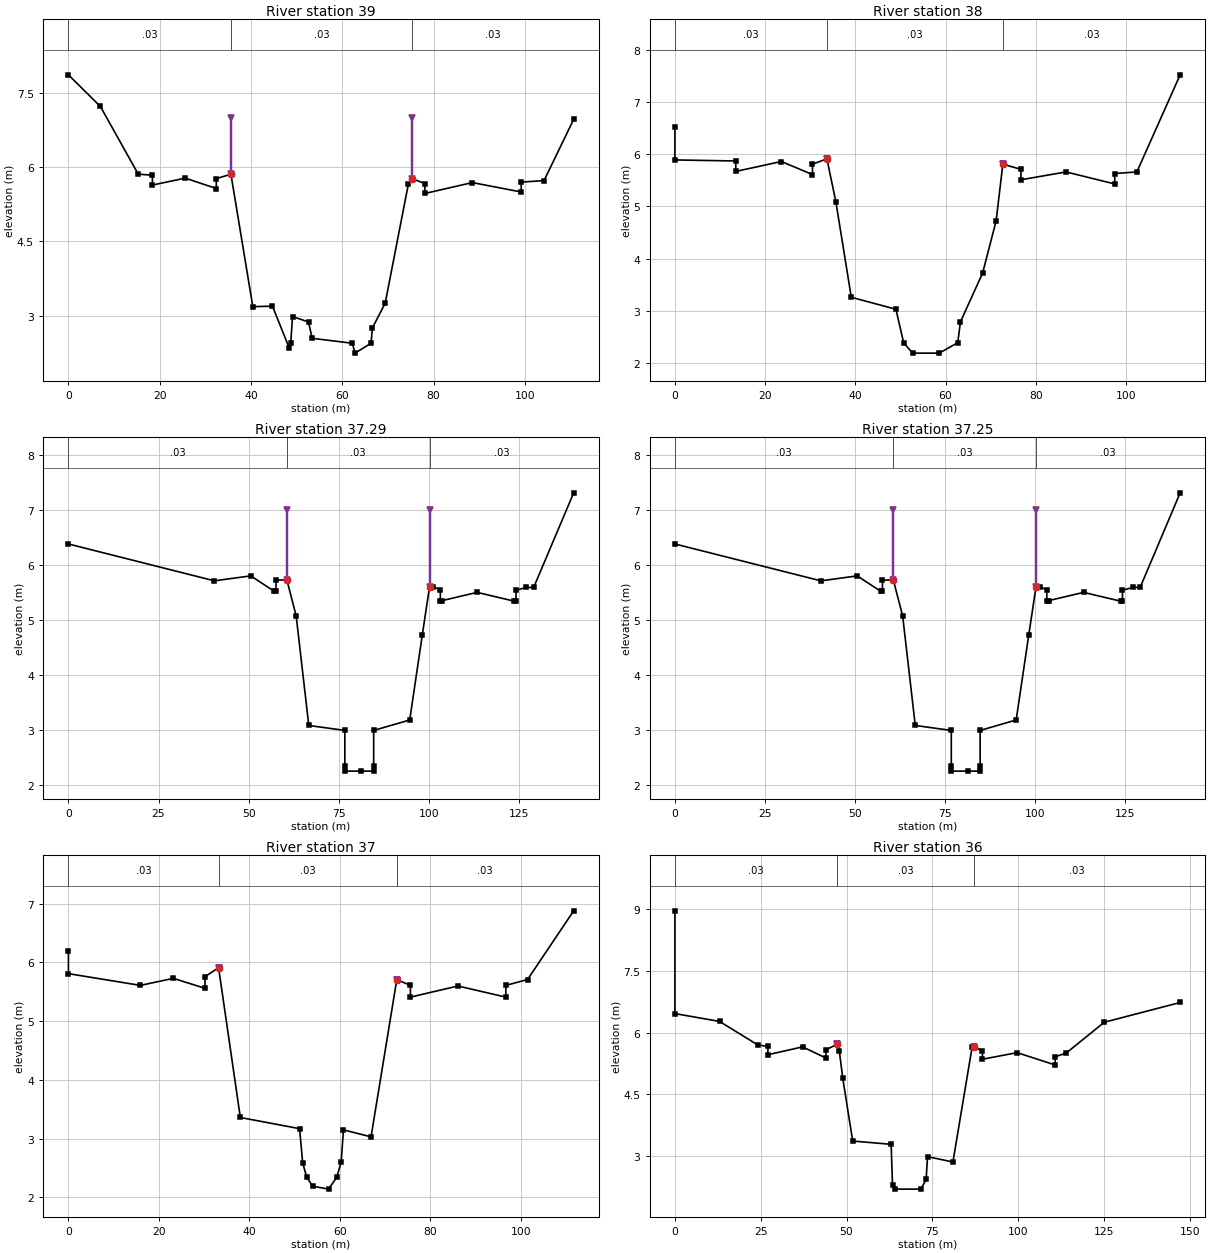
Type RM Length L Ch R = 1 ,39      ,50,50,50
#Sta/Elev= 30
       0    7.87       7    7.23    15.3    5.86    18.4    5.84    18.4    5.64
    25.6    5.78    32.4    5.57    32.4    5.77    35.6    5.86    40.4    3.18
    44.7    3.19    48.4    2.34    48.7    2.44    49.1    2.98    52.6    2.87
    53.4    2.54    62.2    2.44    62.8    2.24    66.3    2.44    66.6    2.75
    69.4    3.25    74.5    5.67    75.3    5.77    78.1    5.67    78.1    5.47
    88.5    5.69    99.2     5.5    99.2     5.7   104.2    5.73   110.7    6.97
#Mann= 3 , 0 , 0
       0     .03       0    35.6     .03       0    75.3     .03       0
Levee=-1,35.6,7,-1,75.3,7,,
Bank Sta=35.6,75.3
Exp/Cntr=0.3,0.1

Type RM Length L Ch R = 1 ,38      ,21,21,21
#Sta/Elev= 26
       0    6.53       0    5.89    13.5    5.87    13.5    5.67    23.6    5.86
    30.5    5.61    30.5    5.81    33.7    5.91    35.7    5.08    39.1    3.26
      49    3.03    50.7    2.39    52.7    2.19    58.6    2.19    62.7    2.39
    63.3    2.79    68.2    3.72    71.2    4.72    72.7    5.81    76.7    5.71
    76.7    5.51    86.7    5.66    97.5    5.43    97.5    5.63   102.4    5.66
     112    7.52
#Mann= 3 , 0 , 0
       0     .03       0    33.7     .03       0    72.7     .03       0
Levee=-1,33.7,5.91,-1,72.7,5.81,,
Bank Sta=33.7,72.7
Exp/Cntr=0.3,0.1

Type RM Length L Ch R = 1 ,37.29   ,4,4,4
#Sta/Elev= 30
       0    6.38    40.5    5.71    50.6     5.8    57.1    5.52    57.6    5.52
    57.6    5.72    60.6    5.73    63.2    5.07    66.7    3.08    76.7    2.99
    76.7    2.35    76.7    2.25    81.2    2.25    84.7    2.25    84.7    2.35
    84.7    2.99    94.7    3.18    98.2    4.73   100.2     5.6   101.2     5.6
   103.2    5.55   103.2    5.35   103.7    5.35   113.4     5.5   123.7    5.34
   124.2    5.34   124.2    5.54   127.1    5.59   129.1    5.59   140.2    7.31
#Mann= 3 , 0 , 0
       0     .03       0    60.6     .03       0   100.2     .03       0
Levee=-1,60.6,7,-1,100.2,7,,
Bank Sta=60.6,100.2
Exp/Cntr=0.3,0.1

Type RM Length L Ch R = 1 ,37.25   ,25,25,25
#Sta/Elev= 30
       0    6.38    40.5    5.71    50.6     5.8    57.1    5.52    57.6    5.52
    57.6    5.72    60.6    5.73    63.2    5.07    66.7    3.08    76.7    2.99
    76.7    2.35    76.7    2.25    81.2    2.25    84.7    2.25    84.7    2.35
    84.7    2.99    94.7    3.18    98.2    4.73   100.2     5.6   101.2     5.6
   103.2    5.55   103.2    5.35   103.7    5.35   113.4     5.5   123.7    5.34
   124.2    5.34   124.2    5.54   127.1    5.59   129.1    5.59   140.2    7.31
#Mann= 3 , 0 , 0
       0     .03       0    60.6     .03       0   100.2     .03       0
Levee=-1,60.6,7,-1,100.2,7,,
Bank Sta=60.6,100.2
Exp/Cntr=0.3,0.1

Type RM Length L Ch R = 1 ,37      ,50,50,50
#Sta/Elev= 25
       0    6.19       0    5.81    15.9    5.61    23.2    5.73    30.2    5.56
    30.2    5.76    33.2    5.91      38    3.36    51.1    3.17    51.8    2.58
    52.7    2.34      54    2.19    57.5    2.14    59.3    2.34    60.3     2.6
    60.8    3.15    66.9    3.03    72.6    5.71    75.6    5.61    75.6    5.41
    86.1     5.6    96.7    5.41    96.7    5.61   101.5    5.71   111.7    6.88
#Mann= 3 , 0 , 0
       0     .03       0    33.2     .03       0    72.6     .03       0
Levee=-1,33.2,5.91,-1,72.6,5.71,,
Bank Sta=33.2,72.6
Exp/Cntr=0.3,0.1

Type RM Length L Ch R = 1 ,36      ,50,50,50
#Sta/Elev= 30
       0    8.96       0    6.46      13    6.27    24.1     5.7    27.1    5.66
    27.1    5.46    37.2    5.65      44    5.38      44    5.58    47.2    5.71
    47.9    5.55    48.9    4.89    51.8    3.36      63    3.28    63.4    2.29
    64.2    2.19    71.7    2.19    73.2    2.43    73.6    2.98      81    2.85
    86.6    5.65    87.2    5.65    89.6    5.55    89.6    5.35    99.7    5.51
   110.8    5.21   110.8    5.41     114     5.5   125.1    6.25   147.2    6.73
#Mann= 3 , 0 , 0
       0     .03       0    47.2     .03       0    87.2     .03       0
Levee=-1,47.2,5.71,-1,87.2,5.65,,
Bank Sta=47.2,87.2
Exp/Cntr=0.3,0.1

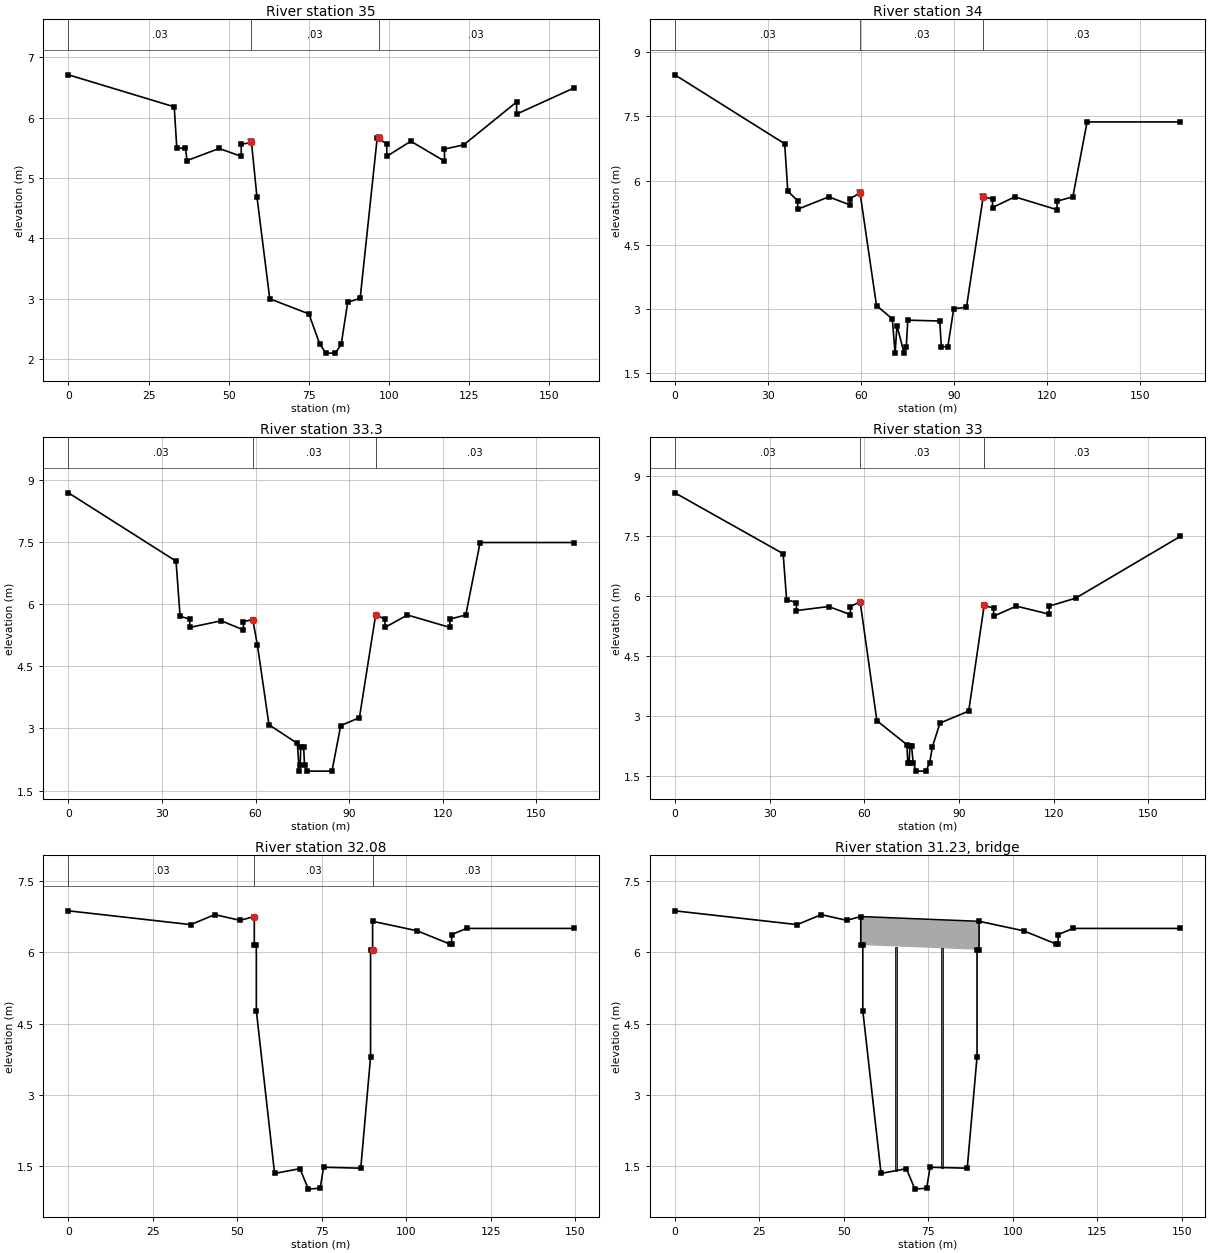
Type RM Length L Ch R = 1 ,35      ,50,50,50
#Sta/Elev= 29
       0    6.71      33    6.18    33.8     5.5    36.5    5.49      37    5.29
      47    5.49    53.9    5.36    53.9    5.56    57.1    5.59    58.8    4.69
    62.8       3      75    2.75    78.4    2.25    80.3     2.1    83.3     2.1
    85.1    2.25    87.1    2.94      91    3.01    96.3    5.66    96.8    5.66
    99.3    5.56    99.3    5.36   106.8    5.61   117.3    5.28   117.3    5.48
   123.3    5.55   139.8    6.26   139.8    6.06   157.6    6.49
#Mann= 3 , 0 , 0
       0     .03       0    57.1     .03       0    96.8     .03       0
Levee=-1,57.1,5.59,-1,96.8,5.66,,
Bank Sta=57.1,96.8
Exp/Cntr=0.3,0.1

Type RM Length L Ch R = 1 ,34      ,20,20,20
#Sta/Elev= 30
       0    8.47    35.4    6.86    36.4    5.75    39.6    5.53    39.6    5.33
    49.6    5.62    56.5    5.43    56.5    5.58    59.7    5.71      65    3.08
    70.1    2.77      71    1.97    71.6    2.61    73.9    1.97    74.6    2.12
    75.1    2.74    85.4    2.72    85.9    2.12      88    2.12    89.9    3.01
      94    3.04    99.4    5.62   102.4    5.57   102.4    5.37   109.6    5.62
   123.2    5.32   123.2    5.52   128.3    5.62   132.9    7.37   162.9    7.37
#Mann= 3 , 0 , 0
       0     .03       0    59.7     .03       0    99.4     .03       0
Levee=-1,59.7,5.71,-1,99.4,5.62,,
Bank Sta=59.7,99.4
Exp/Cntr=0.3,0.1

Type RM Length L Ch R = 1 ,33.3    ,30,30,30
#Sta/Elev= 30
       0    8.69    34.5    7.04    35.8    5.71    38.9    5.64    38.9    5.44
      49     5.6    56.1    5.38    56.1    5.58    59.1    5.63    60.6    5.01
    64.3    3.09    73.4    2.64      74    1.97    74.3    2.12    74.5    2.56
    75.4    2.56    75.7    2.12    76.5    1.97    84.5    1.97    87.3    3.07
    93.3    3.26    98.5    5.74   101.5    5.64   101.5    5.44   108.7    5.74
   122.3    5.44   122.3    5.64   127.4    5.74     132    7.49     162    7.49
#Mann= 3 , 0 , 0
       0     .03       0    59.1     .03       0    98.5     .03       0
Bank Sta=59.1,98.5
Exp/Cntr=0.3,0.1

Type RM Length L Ch R = 1 ,33      ,42,42,42
#Sta/Elev= 30
       0    8.57    34.3    7.05    35.4     5.9    38.5    5.83    38.5    5.63
    48.7    5.73    55.6    5.53    55.6    5.73    58.7    5.85      64    2.88
    73.5    2.28    73.8    1.82    74.2    1.82    74.5    2.25      75    2.25
    75.5    1.82    76.5    1.62    79.5    1.62    80.7    1.82    81.6    2.23
      84    2.82    93.1    3.12      98    5.76     101    5.69     101    5.49
   108.2    5.74   118.6    5.54   118.6    5.74     127    5.94   160.1    7.48
#Mann= 3 , 0 , 0
       0     .03       0    58.7     .03       0      98     .03       0
Bank Sta=58.7,98
Exp/Cntr=0.3,0.1

Type RM Length L Ch R = 1 ,32.08   ,70,70,70
#Sta/Elev= 24
       0    6.87    36.2    6.58    43.3    6.79    50.8    6.67      55    6.75
      55    6.15    55.6    6.15    55.6    4.77      61    1.35    68.5    1.45
      71    1.02    74.5    1.04    75.5    1.48    86.5    1.46    89.4     3.8
    89.4    6.05      90    6.05      90    6.65   103.2    6.45   112.9    6.17
   113.4    6.17   113.4    6.37   117.8     6.5   149.5     6.5
#Mann= 3 , 0 , 0
       0     .03       0      55     .03       0      90     .03       0
Bank Sta=55,90
Exp/Cntr=0.3,0.1

Type RM Length L Ch R = 3 ,31.23   ,,,
BEGIN DESCRIPTION:
È­Á¤±³
END DESCRIPTION:
Bridge Culvert--1,0,-1,-1, 0
Deck Dist Width WeirC Skew NumUp NumDn MinLoCord MaxHiCord MaxSubmerge Is_Ogee
0.1,69,1.44,0, 2, 2, , , 0.95, 0, 0,0,,
      55      90
    6.75    6.65
    6.15    6.05
    39.5    74.5
    6.58    6.58
    5.98    5.98
Pier Skew, UpSta & Num, DnSta & Num=  ,65.5, 2 ,50, 2 , 0 , 0 , 0 ,,
      .6      .6
       0       7
      .6      .6
       0       7
Pier Skew, UpSta & Num, DnSta & Num=  ,79, 2 ,63.5, 2 , 0 , 0 , 0 ,,
      .6      .6
       0       7
      .6      .6
       0       7
BR Coef=-1 , 0 , 0 ,, 0 ,,,0.8,-1,,0,
WSPro=,,,, 1 ,,,, 0 ,,,, 0 ,,,,-1 ,-1 ,-1 , 0 , 0 , 0 , 0 , 0
BC Design=,, 0 ,, 0 ,,,,,,

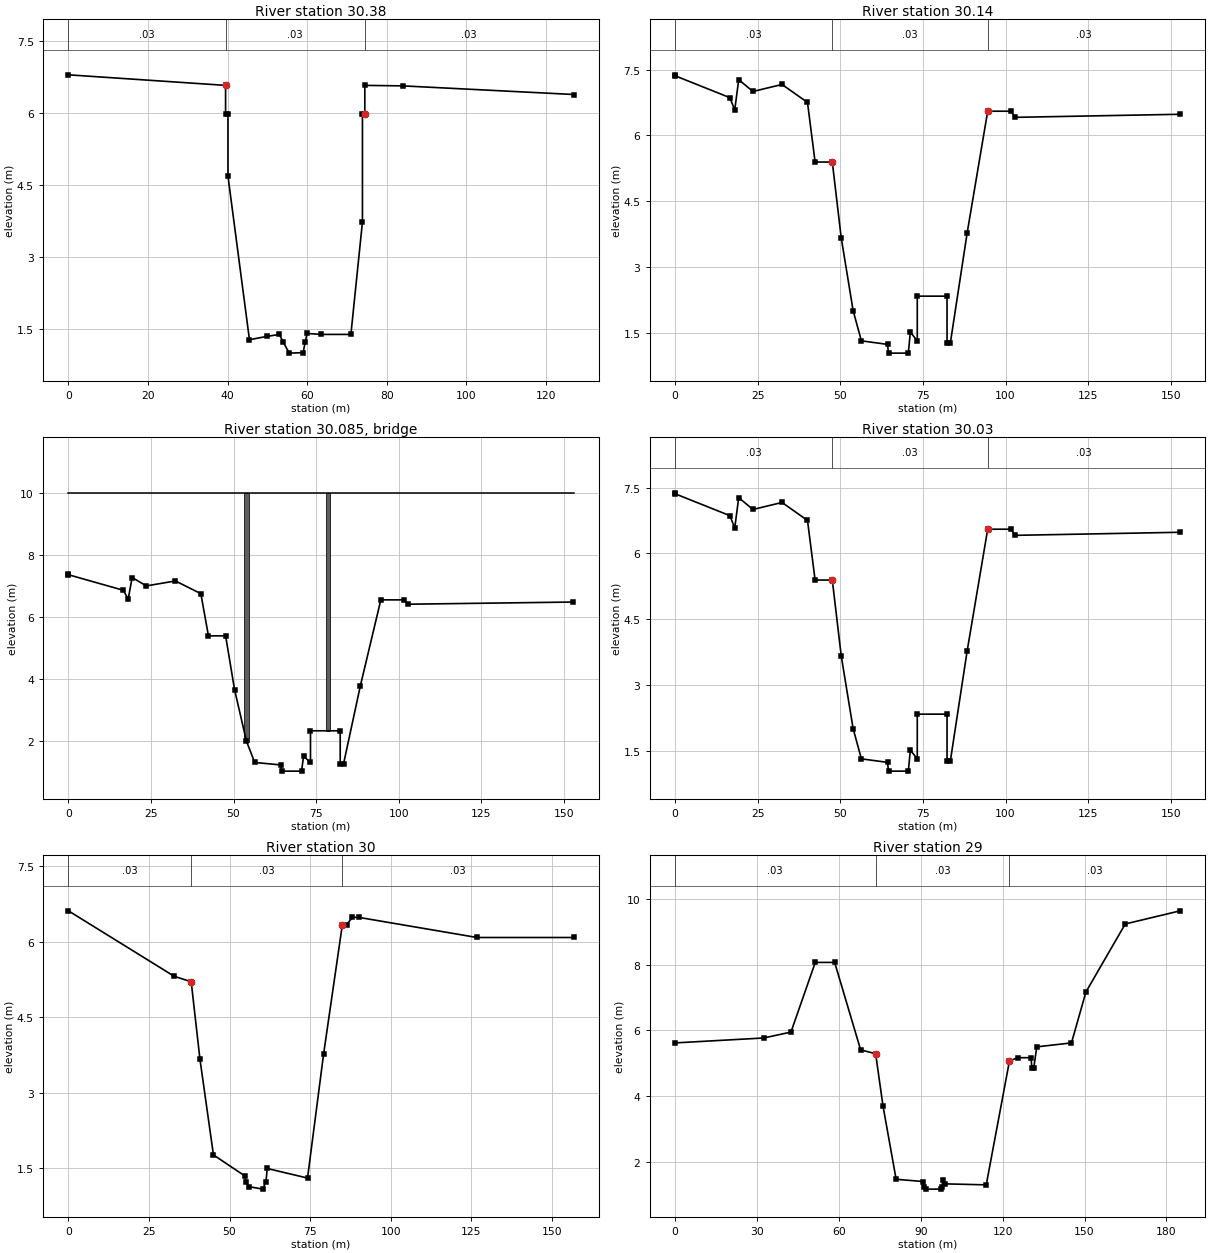
Type RM Length L Ch R = 1 ,30.38   ,24,24,24
#Sta/Elev= 21
       0     6.8    39.5    6.58    39.5    5.98    40.1    5.98    40.1    4.69
    45.5    1.28      50    1.35      53    1.39      54    1.23    55.5       1
      59    1.01    59.5    1.23      60    1.41    63.5    1.39      71    1.39
    73.9    3.73    73.9    5.98    74.5    5.98    74.5    6.58      84    6.57
     127    6.39
#Mann= 3 , 0 , 0
       0     .03       0    39.5     .03       0    74.5     .03       0
Bank Sta=39.5,74.5
Exp/Cntr=0.5,0.3

Type RM Length L Ch R = 1 ,30.14   ,11,11,11
#Sta/Elev= 27
       0    7.38       0    7.36    16.6    6.86    18.1    6.58    19.3    7.27
    23.6       7    32.4    7.16    40.1    6.75    42.4    5.39    47.6    5.39
    50.3    3.66    53.9       2    56.4    1.31    64.3    1.23    64.6    1.03
    70.6    1.03    71.2    1.51    73.3    1.31    73.3    2.33    82.3    2.33
    82.3    1.26    83.3    1.26    88.4    3.78    94.6    6.55   101.6    6.55
   102.9    6.41   152.8    6.48
#Mann= 3 , 0 , 0
       0     .03       0    47.6     .03       0    94.6     .03       0
Bank Sta=47.6,94.6
Exp/Cntr=0.5,0.3

Type RM Length L Ch R = 3 ,30.085  ,,,
BEGIN DESCRIPTION:
ÁöÇÏÃ¶±³·®
END DESCRIPTION:
Bridge Culvert--1,0,-1,-1, 0
Deck Dist Width WeirC Skew NumUp NumDn MinLoCord MaxHiCord MaxSubmerge Is_Ogee
0.1,10,1.44,0, 2, 2, , , 0.95, 0, 0,0,,
       0     153
      10      10
      10      10
       0     153
      10      10
      10      10
Pier Skew, UpSta & Num, DnSta & Num=  ,54, 2 ,54, 2 , 0 , 0 , 0 ,,
     1.5     1.5
       0      10
     1.5     1.5
       0      10
Pier Skew, UpSta & Num, DnSta & Num=  ,78.6, 2 ,78.6, 2 , 0 , 0 , 0 ,,
     1.5     1.5
       0      10
     1.5     1.5
       0      10
BR Coef=-1 , 0 , 0 ,, 0 ,,,0.8,-1,,0,
WSPro=,,,, 1 ,,,, 0 ,,,, 0 ,,,,-1 ,-1 ,-1 , 0 , 0 , 0 , 0 , 0
BC Design=,, 0 ,, 0 ,,,,,,

Type RM Length L Ch R = 1 ,30.03   ,3,3,3
#Sta/Elev= 27
       0    7.38       0    7.36    16.6    6.86    18.1    6.58    19.3    7.27
    23.6       7    32.4    7.16    40.1    6.75    42.4    5.39    47.6    5.39
    50.3    3.66    53.9       2    56.4    1.31    64.3    1.23    64.6    1.03
    70.6    1.03    71.2    1.51    73.3    1.31    73.3    2.33    82.3    2.33
    82.3    1.26    83.3    1.26    88.4    3.78    94.6    6.55   101.6    6.55
   102.9    6.41   152.8    6.48
#Mann= 3 , 0 , 0
       0     .03       0    47.6     .03       0    94.6     .03       0
Bank Sta=47.6,94.6
Exp/Cntr=0.5,0.3

Type RM Length L Ch R = 1 ,30      ,50,50,50
#Sta/Elev= 19
       0    6.61    32.8    5.31    38.1     5.2    40.8    3.67      45    1.76
    54.8    1.34      55    1.23      56    1.13    60.3    1.08    61.3    1.23
    61.7    1.49    74.2     1.3    79.2    3.77      85    6.33    86.3    6.33
    88.1    6.48    90.1    6.48   126.8    6.08   156.8    6.08
#Mann= 3 , 0 , 0
       0     .03       0    38.1     .03       0      85     .03       0
Bank Sta=38.1,85
Exp/Cntr=0.3,0.1

Type RM Length L Ch R = 1 ,29      ,50,50,50
#Sta/Elev= 27
       0    5.62    32.5    5.77    42.5    5.95    51.4    8.07    58.5    8.07
      68    5.41    73.5    5.29    76.2     3.7      81    1.47      91     1.4
    91.3    1.22    91.8    1.17    97.3    1.17    97.8    1.22    98.1    1.45
      99    1.33     114     1.3   122.5    5.07   125.5    5.17   130.4    5.17
   130.7    4.86   131.4    4.86   132.5     5.5   145.2    5.62   150.5    7.17
   164.9    9.24     185    9.64
#Mann= 3 , 0 , 0
       0     .03       0    73.5     .03       0   122.5     .03       0
Bank Sta=73.5,122.5
Exp/Cntr=0.3,0.1

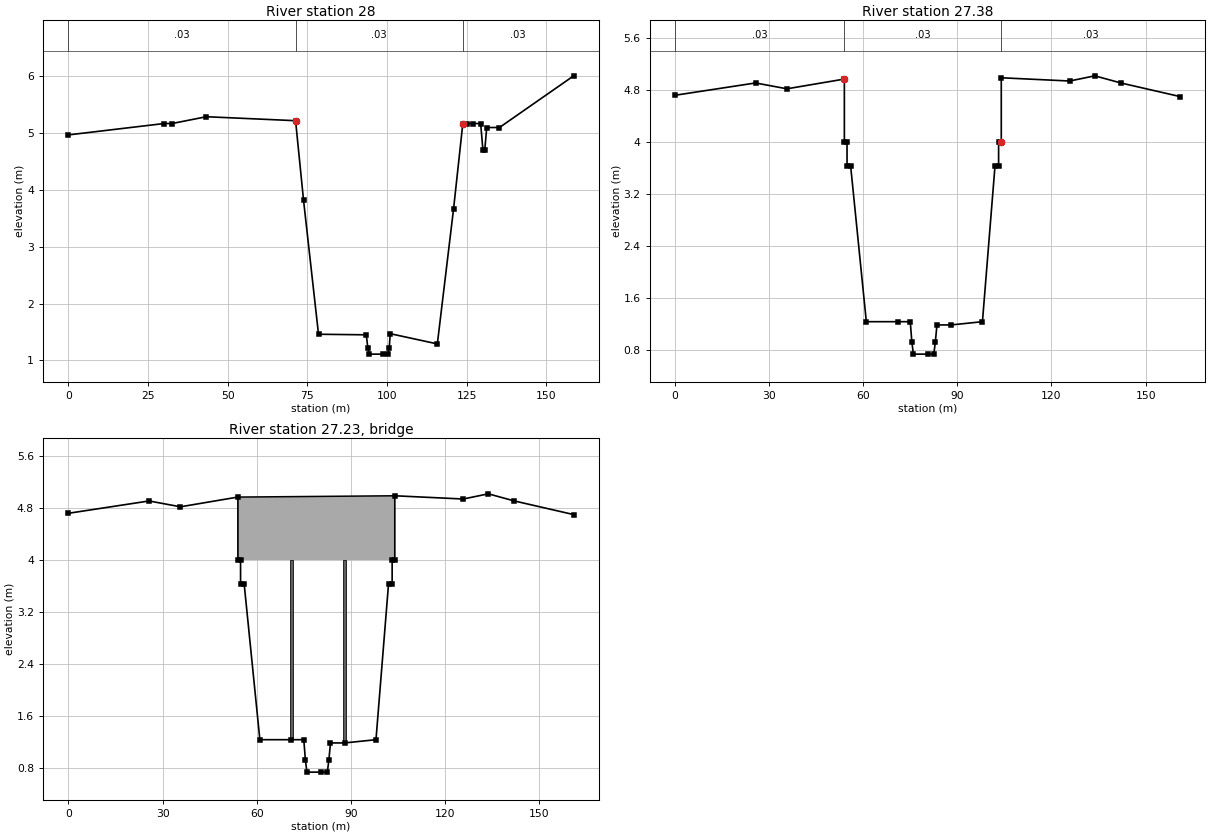
Type RM Length L Ch R = 1 ,28      ,12,12,12
#Sta/Elev= 25
       0    4.97      30    5.17    32.5    5.17    43.3    5.29    71.3    5.22
    73.8    3.82    78.5    1.46    93.5    1.45      94    1.21    94.5    1.11
    98.8    1.11   100.2    1.11   100.7    1.21     101    1.47   115.8    1.29
   120.9    3.67   123.8    5.17     125    5.17     127    5.17   129.4    5.17
   130.1    4.71   130.7    4.71   131.3     5.1   135.3     5.1   158.6    6.01
#Mann= 3 , 0 , 0
       0     .03       0    71.3     .03       0   123.8     .03       0
Bank Sta=71.3,123.8
Exp/Cntr=0.3,0.1

Type RM Length L Ch R = 1 ,27.38   ,30,30,30
#Sta/Elev= 28
       0    4.72    25.7    4.91    35.7    4.82      54    4.97      54       4
   54.85       4   54.85    3.63      56    3.63      61    1.23      71    1.23
      75    1.23    75.5     .92      76     .73    80.5     .73    82.5     .73
      83     .92    83.5    1.18      88    1.18      98    1.23     102    3.63
  103.15    3.63  103.15       4     104       4     104    4.99   125.8    4.94
   133.8    5.02   142.1    4.91     161     4.7
#Mann= 3 , 0 , 0
       0     .03       0      54     .03       0     104     .03       0
Bank Sta=54,104
Exp/Cntr=0.5,0.3

Type RM Length L Ch R = 3 ,27.23   ,,,
BEGIN DESCRIPTION:
È­Á¤11±³
END DESCRIPTION:
Bridge Culvert--1,0,-1,-1, 0
Deck Dist Width WeirC Skew NumUp NumDn MinLoCord MaxHiCord MaxSubmerge Is_Ogee
0.1,29,1.44,0, 2, 2, , , 0.95, 0, 0,0,,
      54     104
    4.97    4.99
       4       4
      54     104
    4.97    4.99
       4       4
Pier Skew, UpSta & Num, DnSta & Num=  ,71, 2 ,71, 2 , 0 , 0 , 0 ,,
       1       1
       0       5
       1       1
       0       5
Pier Skew, UpSta & Num, DnSta & Num=  ,88, 2 ,88, 2 , 0 , 0 , 0 ,,
       1       1
       0       5
       1       1
       0       5
BR Coef=-1 , 0 , 0 ,, 0 ,,,0.8,-1,,0,
WSPro=,,,, 1 ,,,, 0 ,,,, 0 ,,,,-1 ,-1 ,-1 , 0 , 0 , 0 , 0 , 0
BC Design=,, 0 ,, 0 ,,,,,,