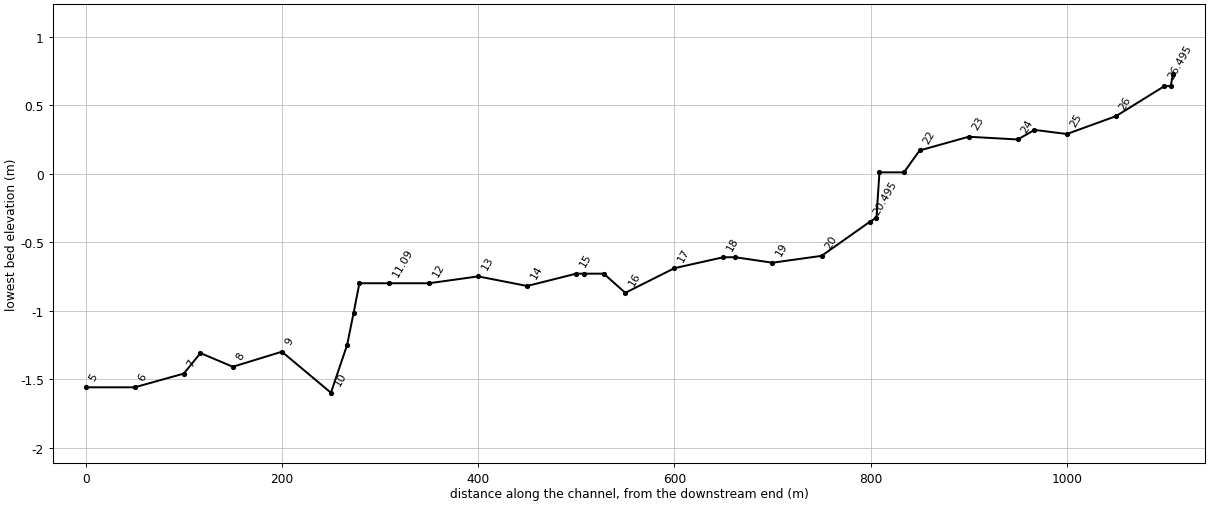
HEC-RAS study Hwajung.prj: Hwajung

--- Hwajung.g01 (geometry) --- (continued)

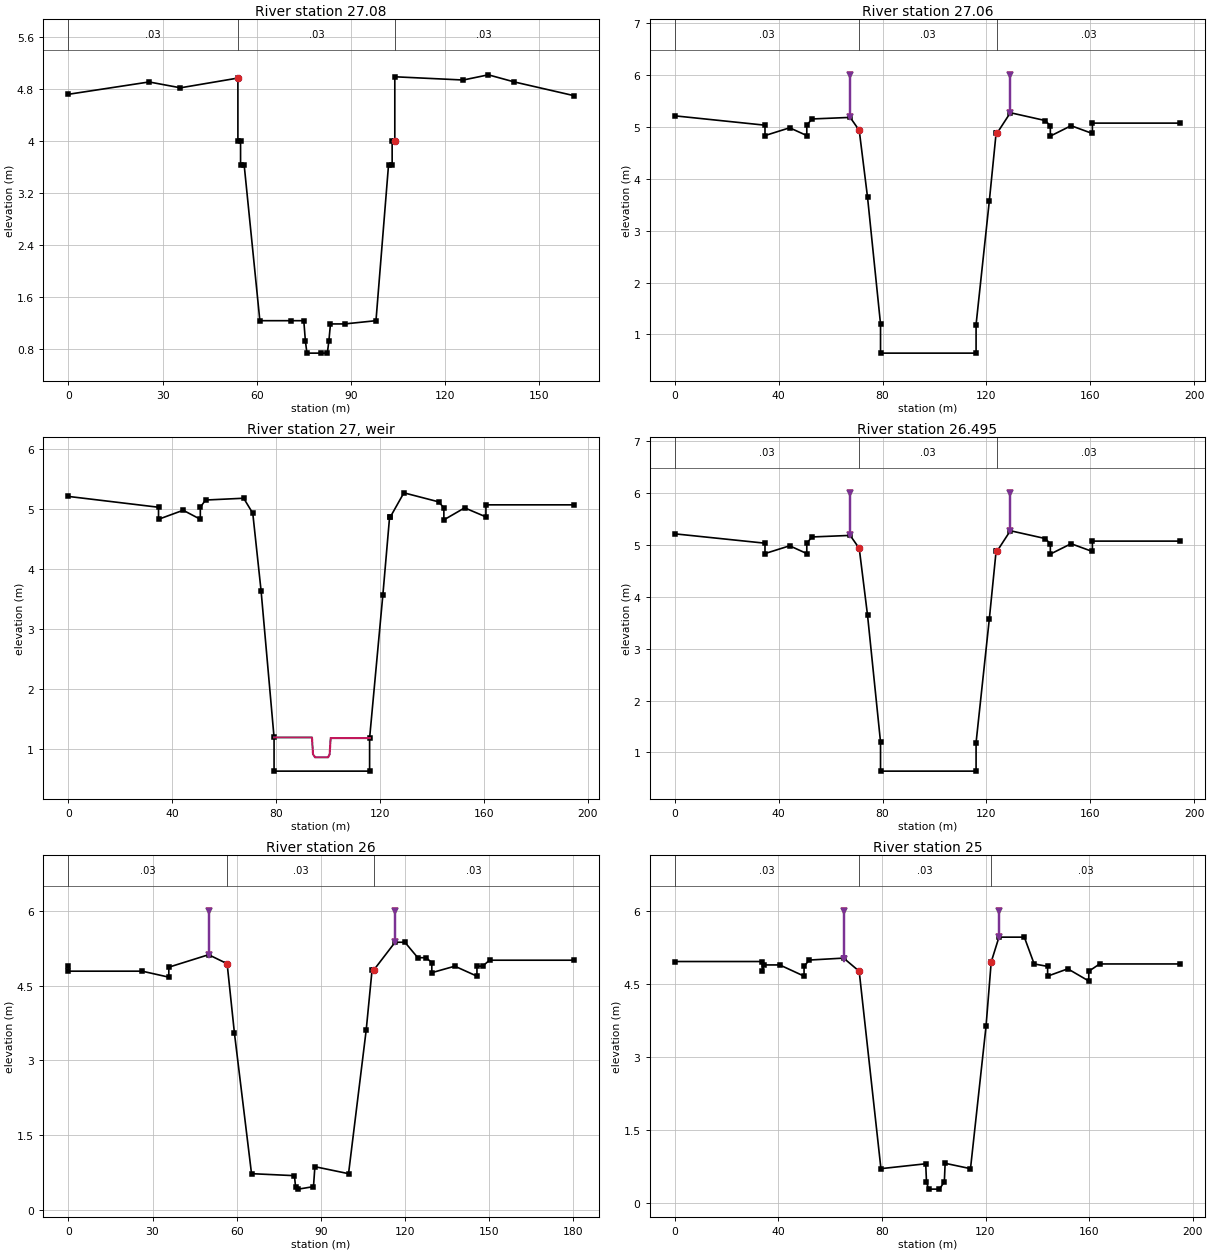
Type RM Length L Ch R = 1 ,27.08   ,2,2,2
BEGIN DESCRIPTION:
´Ü¸é¼öÁ¤
END DESCRIPTION:
#Sta/Elev= 28
       0    4.72    25.7    4.91    35.7    4.82      54    4.97      54       4
   54.85       4   54.85    3.63      56    3.63      61    1.23      71    1.23
      75    1.23    75.5     .92      76     .73    80.5     .73    82.5     .73
      83     .92    83.5    1.18      88    1.18      98    1.23     102    3.63
  103.15    3.63  103.15       4     104       4     104    4.99   125.8    4.94
   133.8    5.02   142.1    4.91     161     4.7
#Mann= 3 , 0 , 0
       0     .03       0      54     .03       0     104     .03       0
Bank Sta=54,104
Exp/Cntr=0.5,0.3

Type RM Length L Ch R = 1 ,27.06   ,6.5,6.5,6.5
#Sta/Elev= 25
       0    5.21    34.7    5.03    34.7    4.83    44.2    4.98    50.8    4.83
    50.8    5.03    52.8    5.15    67.5    5.18      71    4.93    74.2    3.64
    79.2     1.2    79.2     .64     116     .64     116    1.19   121.1    3.57
   123.7    4.87     124    4.87   129.2    5.27   142.6    5.12   144.6    5.02
   144.6    4.82   152.6    5.02   160.8    4.87   160.8    5.07   194.6    5.07
#Mann= 3 , 0 , 0
       0     .03       0      71     .03       0     124     .03       0
Levee=-1,67.5,6,-1,129.2,6,,
Bank Sta=71,124
Exp/Cntr=0.3,0.1

Type RM Length L Ch R = 5 ,27      ,,,
IW Pilot Flow=0
#Inline Weir SE= 9
    79.2     1.2    93.8     1.2    94.2     .92      95     .87      99     .87
     100     .87   100.6     .92     101    1.19     116    1.19
IW Dist,WD,Coef,Skew,MaxSub,Min_El,Is_Ogee,SpillHt,DesHd
6,0.5,1.44,0,0.95,, 0 ,,,0,0,

Type RM Length L Ch R = 1 ,26.495  ,49.5,49.5,49.5
#Sta/Elev= 25
       0    5.21    34.7    5.03    34.7    4.83    44.2    4.98    50.8    4.83
    50.8    5.03    52.8    5.15    67.5    5.18      71    4.93    74.2    3.64
    79.2     1.2    79.2     .64     116     .64     116    1.19   121.1    3.57
   123.7    4.87     124    4.87   129.2    5.27   142.6    5.12   144.6    5.02
   144.6    4.82   152.6    5.02   160.8    4.87   160.8    5.07   194.6    5.07
#Mann= 3 , 0 , 0
       0     .03       0      71     .03       0     124     .03       0
Levee=-1,67.5,6,-1,129.2,6,,
Bank Sta=71,124
Exp/Cntr=0.3,0.1

Type RM Length L Ch R = 1 ,26      ,50,50,50
#Sta/Elev= 30
       0    4.89       0    4.79    26.3    4.79    35.8    4.67    35.8    4.87
      50    5.12    56.6    4.94    59.2    3.55    65.3     .73    80.6     .69
      81     .47      82     .42    87.4     .47    87.9     .87    99.9     .73
   106.2    3.61   108.3    4.82     109    4.82   116.5    5.37     120    5.37
   124.6    5.06   127.6    5.06   129.6    4.96   129.6    4.76   137.8    4.89
   145.7    4.69   145.7    4.89   147.7    4.89   150.2    5.01   180.2    5.01
#Mann= 3 , 0 , 0
       0     .03       0    56.6     .03       0     109     .03       0
Levee=-1,50,6,-1,116.5,6,,
Bank Sta=56.6,109
Exp/Cntr=0.3,0.1

Type RM Length L Ch R = 1 ,25      ,33,33,33
#Sta/Elev= 30
       0    4.96    33.8    4.96    33.8    4.76    34.3    4.89    40.5    4.89
    49.9    4.66    49.9    4.86    51.9    4.99    65.2    5.03    71.2    4.76
    79.6     .71    96.9     .81    97.2     .44      98     .29   102.2     .29
   104.1     .44   104.4     .82   114.2     .71   120.2    3.63   122.2    4.95
   125.2    5.46     135    5.46   138.8    4.91     144    4.86     144    4.66
   151.8    4.81   159.9    4.56   159.9    4.76   164.1    4.91   195.2    4.91
#Mann= 3 , 0 , 0
       0     .03       0    71.2     .03       0   122.2     .03       0
Levee=-1,65.5,6,-1,125.2,6,,
Bank Sta=71.2,122.2
Exp/Cntr=0.3,0.1

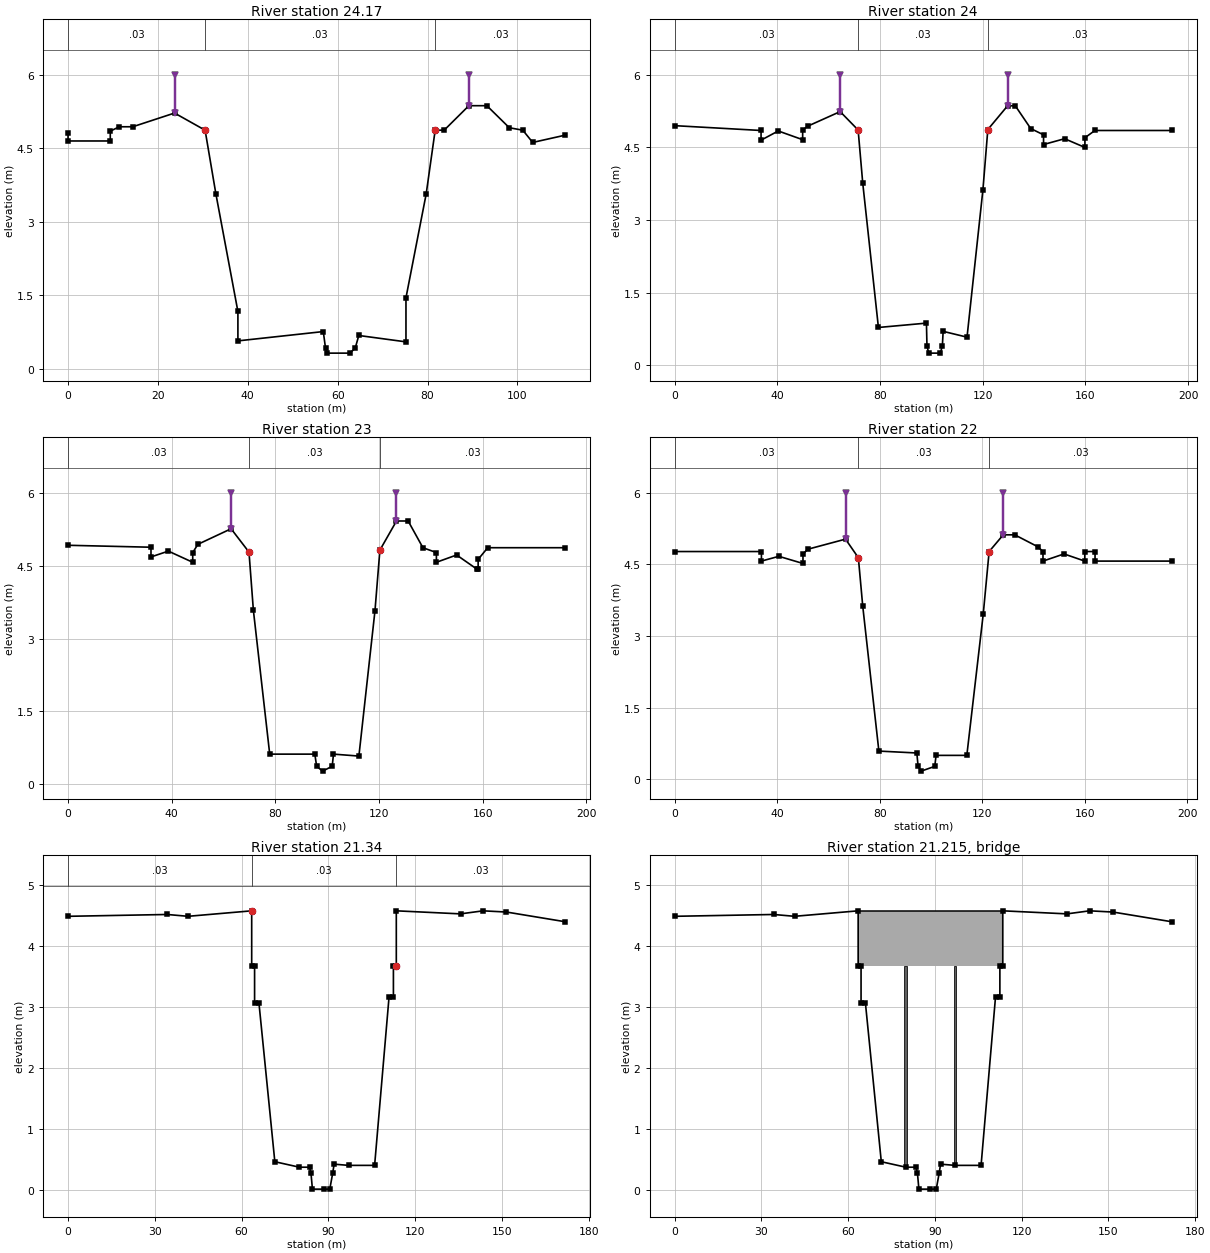
Type RM Length L Ch R = 1 ,24.17   ,17,17,17
#Sta/Elev= 28
       0    4.82       0    4.65     9.4    4.65     9.4    4.85    11.4    4.94
    14.4    4.94    23.7    5.22    30.5    4.87    32.9    3.57    37.8    1.17
    37.8     .57    56.8     .76    57.3     .42    57.7     .32    62.7     .32
    63.9     .42    64.7     .68    75.2     .55    75.2    1.45    79.7    3.57
    81.7    4.87    83.7    4.87    89.2    5.37    93.2    5.37    98.2    4.92
   101.2    4.87   103.4    4.62   110.7    4.77
#Mann= 3 , 0 , 0
       0     .03       0    30.5     .03       0    81.7     .03       0
Levee=-1,23.7,6,-1,89.2,6,,
Bank Sta=30.5,81.7
Exp/Cntr=0.3,0.1

Type RM Length L Ch R = 1 ,24      ,50,50,50
#Sta/Elev= 30
       0    4.95    33.7    4.85    33.7    4.65    40.4    4.84    49.9    4.66
    49.9    4.86    51.9    4.94    64.5    5.24    71.5    4.86    73.3    3.76
    79.4     .78    98.1     .87    98.3      .4      99     .25   103.5     .25
   104.3      .4   104.6      .7   113.9     .58   120.1    3.63     122    4.87
   129.7    5.36   132.7    5.36   138.7    4.89   143.7    4.76   143.7    4.56
   151.9    4.68   159.8     4.5   159.8     4.7   163.7    4.85   193.7    4.85
#Mann= 3 , 0 , 0
       0     .03       0    71.5     .03       0     122     .03       0
Levee=-1,64.5,6,-1,129.7,6,,
Bank Sta=71.5,122
Exp/Cntr=0.3,0.1

Type RM Length L Ch R = 1 ,23      ,50,50,50
#Sta/Elev= 30
       0    4.92      32    4.88      32    4.68    38.7     4.8    48.1    4.57
    48.1    4.77    50.1    4.94    62.9    5.26    69.8    4.78    71.5    3.58
    77.8     .62    95.2     .62    95.9     .37    98.2     .27   101.9     .37
   102.4     .62   112.2     .58   118.4    3.57   120.3    4.82   126.7    5.42
   131.2    5.42   136.9    4.87   142.1    4.77   142.1    4.57   149.9    4.72
   157.7    4.43   158.2    4.43   158.2    4.63   161.9    4.87   191.9    4.87
#Mann= 3 , 0 , 0
       0     .03       0    69.8     .03       0   120.3     .03       0
Levee=-1,62.9,6,-1,126.7,6,,
Bank Sta=69.8,120.3
Exp/Cntr=0.3,0.1

Type RM Length L Ch R = 1 ,22      ,16,16,16
#Sta/Elev= 30
       0    4.77    33.9    4.77    33.9    4.57    40.7    4.67    50.1    4.52
    50.1    4.72    52.1    4.82    66.7    5.03    71.7    4.64    73.4    3.63
    79.7     .59    94.5     .55      95     .27    96.2     .17   101.5     .27
     102      .5     114      .5   120.4    3.46   122.7    4.77   128.2    5.12
   132.7    5.12   141.7    4.87   143.7    4.77   143.7    4.57   151.9    4.72
     160    4.57     160    4.77     164    4.77     164    4.57     194    4.57
#Mann= 3 , 0 , 0
       0     .03       0    71.7     .03       0   122.7     .03       0
Levee=-1,66.7,6,-1,128.2,6,,
Bank Sta=71.7,122.7
Exp/Cntr=0.3,0.1

Type RM Length L Ch R = 1 ,21.34   ,25,25,25
#Sta/Elev= 28
       0    4.49    34.3    4.52    41.5    4.49    63.5    4.58    63.5    3.68
    64.5    3.68    64.5    3.07      66    3.07    71.5     .46      80     .37
    83.5     .37      84     .27    84.5     .01    88.5     .01    90.5     .01
    91.5     .27      92     .42      97      .4     106      .4     111    3.17
   112.5    3.17   112.5    3.68   113.5    3.68   113.5    4.58   135.7    4.53
   143.5    4.58   151.6    4.56     172     4.4
#Mann= 3 , 0 , 0
       0     .03       0    63.5     .03       0   113.5     .03       0
Bank Sta=63.5,113.5
Exp/Cntr=0.5,0.3

Type RM Length L Ch R = 3 ,21.215  ,,,
BEGIN DESCRIPTION:
È­Á¤12±³
END DESCRIPTION:
Bridge Culvert--1,0,-1,-1, 0
Deck Dist Width WeirC Skew NumUp NumDn MinLoCord MaxHiCord MaxSubmerge Is_Ogee
0.1,24,1.44,0, 2, 2, , , 0.95, 0, 0,0,,
    63.5   113.5
    4.58    4.58
    3.68    3.68
    63.5   113.5
    4.58    4.58
    3.68    3.68
Pier Skew, UpSta & Num, DnSta & Num=  ,80, 2 ,80, 2 , 0 , 0 , 0 ,,
       1       1
       0       5
       1       1
       0       5
Pier Skew, UpSta & Num, DnSta & Num=  ,97, 2 ,97, 2 , 0 , 0 , 0 ,,
       1       1
       0       5
       1       1
       0       5
BR Coef=-1 , 0 , 0 ,, 0 ,,,0.8,-1,,0,
WSPro=,,,, 1 ,,,, 0 ,,,, 0 ,,,,-1 ,-1 ,-1 , 0 , 0 , 0 , 0 , 0
BC Design=,, 0 ,, 0 ,,,,,,

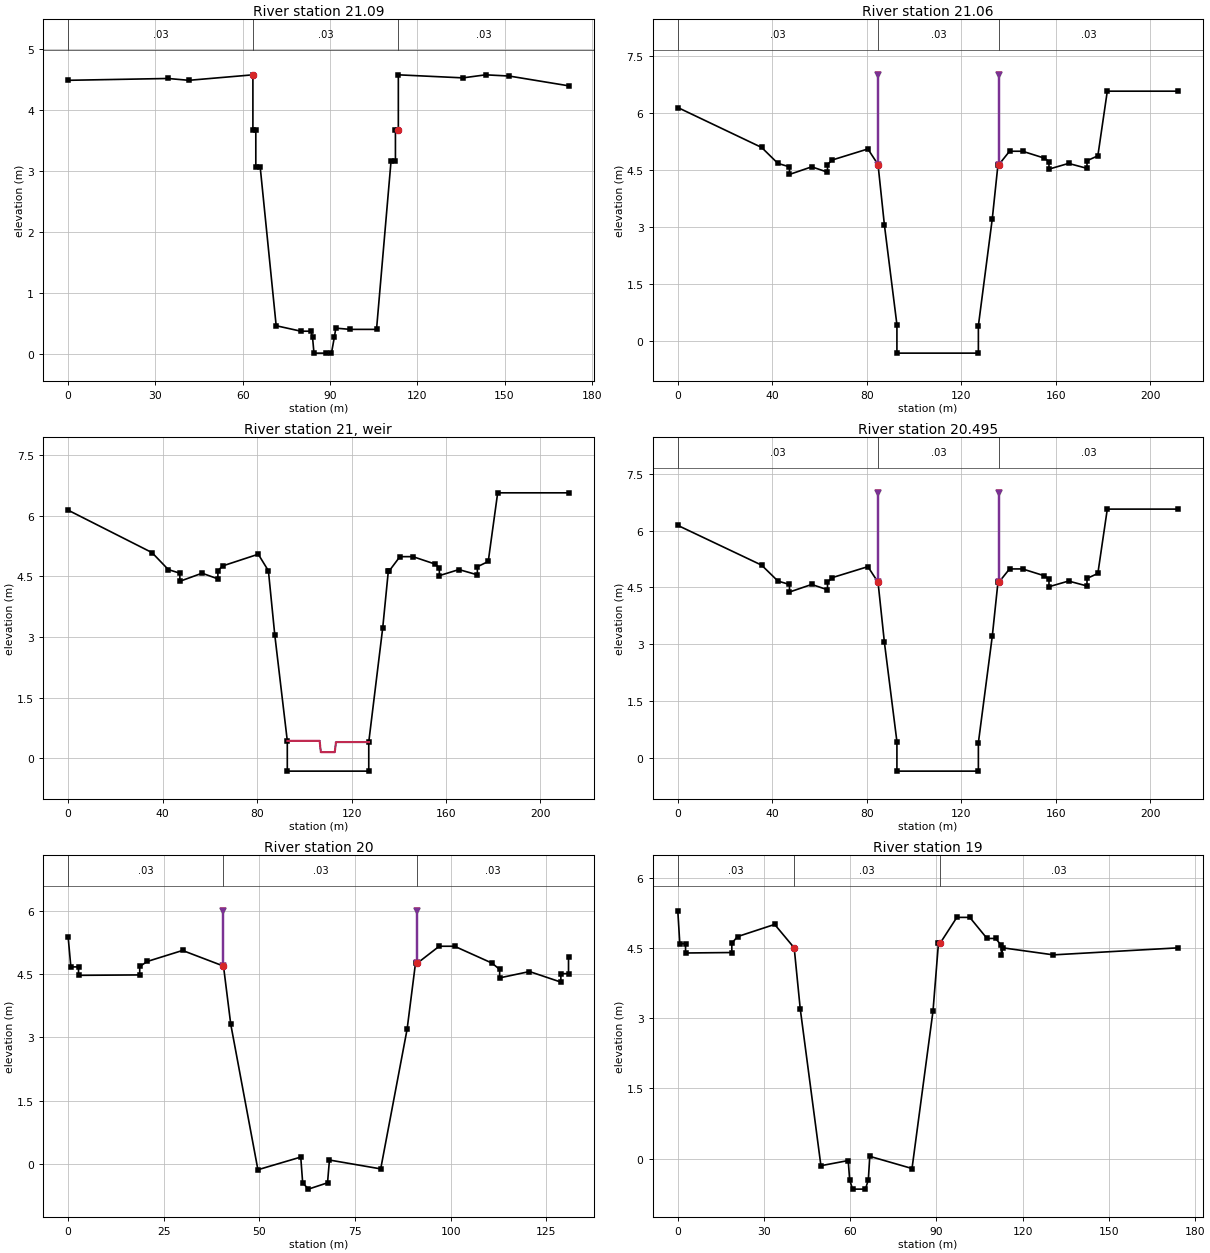
Type RM Length L Ch R = 1 ,21.09   ,3,3,3
#Sta/Elev= 28
       0    4.49    34.3    4.52    41.5    4.49    63.5    4.58    63.5    3.68
    64.5    3.68    64.5    3.07      66    3.07    71.5     .46      80     .37
    83.5     .37      84     .27    84.5     .01    88.5     .01    90.5     .01
    91.5     .27      92     .42      97      .4     106      .4     111    3.17
   112.5    3.17   112.5    3.68   113.5    3.68   113.5    4.58   135.7    4.53
   143.5    4.58   151.6    4.56     172     4.4
#Mann= 3 , 0 , 0
       0     .03       0    63.5     .03       0   113.5     .03       0
Bank Sta=63.5,113.5
Exp/Cntr=0.5,0.3

Type RM Length L Ch R = 1 ,21.06   ,6.5,6.5,6.5
#Sta/Elev= 30
       0    6.14    35.5    5.09    42.4    4.67    47.3    4.58    47.3    4.38
    56.7    4.58    63.4    4.44    63.4    4.64    65.4    4.76    80.5    5.05
    84.8    4.64    87.5    3.05    92.8     .43    92.8    -.32   127.3    -.32
   127.3      .4   133.2    3.22   135.6    4.64     136    4.64   140.5    4.99
     146    4.99   155.2    4.81   157.2    4.72   157.2    4.52   165.5    4.67
   173.3    4.54   173.3    4.74   177.9    4.87   181.9    6.57   211.9    6.57
#Mann= 3 , 0 , 0
       0     .03       0    84.8     .03       0     136     .03       0
Levee=-1,84.8,7,-1,136,7,,
Bank Sta=84.8,136
Exp/Cntr=0.3,0.1

Type RM Length L Ch R = 5 ,21      ,,,
IW Pilot Flow=0
#Inline Weir SE= 6
    92.8     .43   106.5     .43     107     .15   112.9     .15   113.4      .4
   127.3      .4
IW Dist,WD,Coef,Skew,MaxSub,Min_El,Is_Ogee,SpillHt,DesHd
6,0.5,1.44,0,0.95,, 0 ,,,0,0,

Type RM Length L Ch R = 1 ,20.495  ,49.5,49.5,49.5
#Sta/Elev= 30
       0    6.14    35.5    5.09    42.4    4.67    47.3    4.58    47.3    4.38
    56.7    4.58    63.4    4.44    63.4    4.64    65.4    4.76    80.5    5.05
    84.8    4.64    87.5    3.05    92.8     .43    92.8    -.35   127.3    -.35
   127.3      .4   133.2    3.22   135.6    4.64     136    4.64   140.5    4.99
     146    4.99   155.2    4.81   157.2    4.72   157.2    4.52   165.5    4.67
   173.3    4.54   173.3    4.74   177.9    4.87   181.9    6.57   211.9    6.57
#Mann= 3 , 0 , 0
       0     .03       0    84.8     .03       0     136     .03       0
Levee=-1,84.8,7,-1,136,7,,
Bank Sta=84.8,136
Exp/Cntr=0.3,0.1

Type RM Length L Ch R = 1 ,20      ,50,50,50
#Sta/Elev= 30
       0    5.37      .7    4.67     2.7    4.67     2.7    4.47    18.7    4.48
    18.7    4.68    20.7     4.8    29.9    5.06    40.6    4.69    42.5    3.31
    49.6    -.14    60.8     .16    61.3    -.45    62.8     -.6    67.8    -.45
    68.3     .09    81.7    -.12    88.6    3.19    90.8    4.76    91.3    4.76
      97    5.16     101    5.16   110.8    4.76   112.8    4.61   112.8    4.41
   120.6    4.56   128.8    4.31   128.8    4.51   130.8    4.51   130.8    4.91
#Mann= 3 , 0 , 0
       0     .03       0    40.6     .03       0    91.3     .03       0
Levee=-1,40.6,6,-1,91.3,6,,
Bank Sta=40.6,91.3
Exp/Cntr=0.3,0.1

Type RM Length L Ch R = 1 ,19      ,38,38,38
#Sta/Elev= 30
       0    5.29      .7    4.59     2.7    4.59     2.7    4.39    18.8     4.4
    18.8     4.6    20.8    4.74    33.7       5    40.5     4.5    42.6     3.2
    49.8    -.15    59.3    -.04    59.8    -.45    60.8    -.65    65.3    -.65
    66.3    -.45    66.8     .05    81.5    -.21    88.8    3.15    90.7     4.6
    91.3     4.6    97.1    5.15   101.6    5.15   107.6     4.7   110.6     4.7
   112.6    4.55   112.6    4.35   113.1     4.5   130.7    4.35   174.1     4.5
#Mann= 3 , 0 , 0
       0     .03       0    40.5     .03       0    91.3     .03       0
Bank Sta=40.5,91.3
Exp/Cntr=0.3,0.1

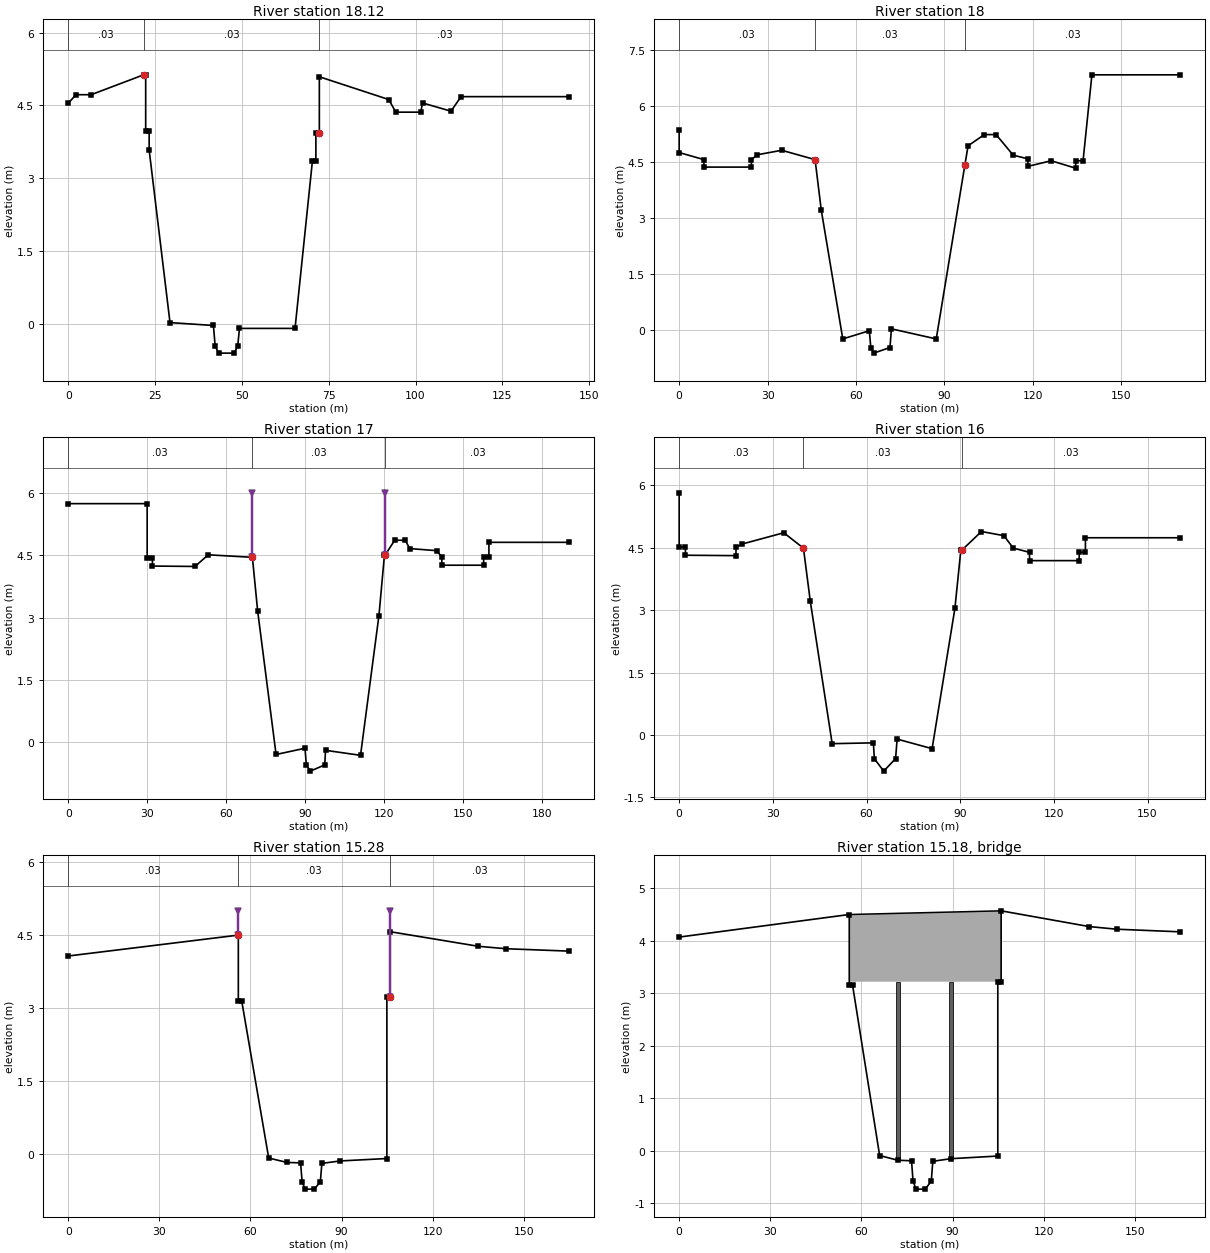
Type RM Length L Ch R = 1 ,18.12   ,12,12,12
#Sta/Elev= 28
       0    4.54     2.2    4.72     6.6    4.72    21.7    5.13    22.3    5.12
    22.3    3.97    23.3    3.97    23.3    3.58    29.3     .02    41.8    -.04
    42.3    -.46    43.3    -.61    47.8    -.61    48.8    -.46    49.3     -.1
    65.3     -.1    70.3    3.35    71.3    3.35    71.3    3.94    72.3    3.94
    72.3    5.09    92.3    4.62    94.3    4.36   101.5    4.36     102    4.55
   110.2    4.38   113.1    4.68   144.3    4.68
#Mann= 3 , 0 , 0
       0     .03       0    21.7     .03       0    72.3     .03       0
Bank Sta=21.7,72.3
Exp/Cntr=0.3,0.1

Type RM Length L Ch R = 1 ,18      ,50,50,50
#Sta/Elev= 30
       0    5.36       0    4.76     8.4    4.57     8.4    4.37    24.5    4.37
    24.5    4.57    26.5     4.7    34.8    4.82    46.1    4.57    48.2    3.22
    55.5    -.23    64.5    -.01      65    -.46      66    -.61    71.5    -.46
      72     .04    87.2    -.23    96.9    4.42      98    4.94   103.5    5.24
   107.5    5.24   113.3    4.69   118.3    4.59   118.3    4.39   126.2    4.54
   134.5    4.34   134.5    4.54     137    4.54     140    6.84     170    6.84
#Mann= 3 , 0 , 0
       0     .03       0    46.1     .03       0    96.9     .03       0
Bank Sta=46.1,96.9
Exp/Cntr=0.3,0.1

Type RM Length L Ch R = 1 ,17      ,50,50,50
#Sta/Elev= 30
       0    5.74      30    5.74      30    4.44      32    4.44      32    4.24
    48.2    4.23    53.2    4.51      70    4.45      72    3.16      79    -.29
      90    -.14    90.5    -.54      92    -.69    97.5    -.54    97.8    -.19
   111.1    -.31   118.1    3.05   120.2    4.51   120.5    4.51   124.1    4.86
   128.1    4.86   129.8    4.66     140    4.61     142    4.46     142    4.26
   157.9    4.26   157.9    4.46   159.9    4.46   159.9    4.81   190.5    4.81
#Mann= 3 , 0 , 0
       0     .03       0      70     .03       0   120.5     .03       0
Levee=-1,70,6,-1,120.5,6,,
Bank Sta=70,120.5
Exp/Cntr=0.3,0.1

Type RM Length L Ch R = 1 ,16      ,22,22,22
#Sta/Elev= 30
       0    5.82       0    4.52       2    4.52       2    4.32    18.2    4.31
    18.2    4.51    20.2    4.59    33.5    4.86    39.8    4.49      42    3.21
      49    -.21    62.2    -.19    62.5    -.57    65.5    -.87    69.3    -.57
    69.8     -.1      81    -.33    88.3    3.04    90.2    4.44    90.5    4.44
    96.8    4.89     104    4.79     107    4.49   112.2    4.39   112.2    4.19
   128.1    4.19   128.1    4.39   130.1    4.39   130.1    4.74   160.5    4.74
#Mann= 3 , 0 , 0
       0     .03       0    39.8     .03       0    90.5     .03       0
Bank Sta=39.8,90.5
Exp/Cntr=0.3,0.1

Type RM Length L Ch R = 1 ,15.28   ,20,20,20
#Sta/Elev= 20
       0    4.07      56     4.5      56    3.15    57.1    3.15      66    -.09
      72    -.18    76.5    -.19      77    -.58      78    -.73      81    -.73
      83    -.58    83.5     -.2    89.5    -.15   104.9     -.1   104.9    3.22
     106    3.22     106    4.57     135    4.27     144    4.22     165    4.17
#Mann= 3 , 0 , 0
       0     .03       0      56     .03       0     106     .03       0
Levee=-1,56,5,-1,106,5,,
Bank Sta=56,106
Exp/Cntr=0.5,0.3

Type RM Length L Ch R = 3 ,15.18   ,,,
BEGIN DESCRIPTION:
È­Á¤14±³
END DESCRIPTION:
Bridge Culvert--1,0,-1,-1, 0
Deck Dist Width WeirC Skew NumUp NumDn MinLoCord MaxHiCord MaxSubmerge Is_Ogee
0.1,19,1.44,0, 2, 2, , , 0.95, 0, 0,0,,
      56     106
     4.5    4.57
    3.22    3.22
      56     106
     4.5    4.57
    3.22    3.22
Pier Skew, UpSta & Num, DnSta & Num=  ,72, 2 ,72, 2 , 0 , 0 , 0 ,,
     1.2     1.2
       0       4
     1.2     1.2
       0       4
Pier Skew, UpSta & Num, DnSta & Num=  ,89.5, 2 ,89.5, 2 , 0 , 0 , 0 ,,
     1.2     1.2
       0       4
     1.2     1.2
       0       4
BR Coef=-1 , 0 , 0 ,, 0 ,,,0.8,-1,,0,
WSPro=,,,, 1 ,,,, 0 ,,,, 0 ,,,,-1 ,-1 ,-1 , 0 , 0 , 0 , 0 , 0
BC Design=,, 0 ,, 0 ,,,,,,

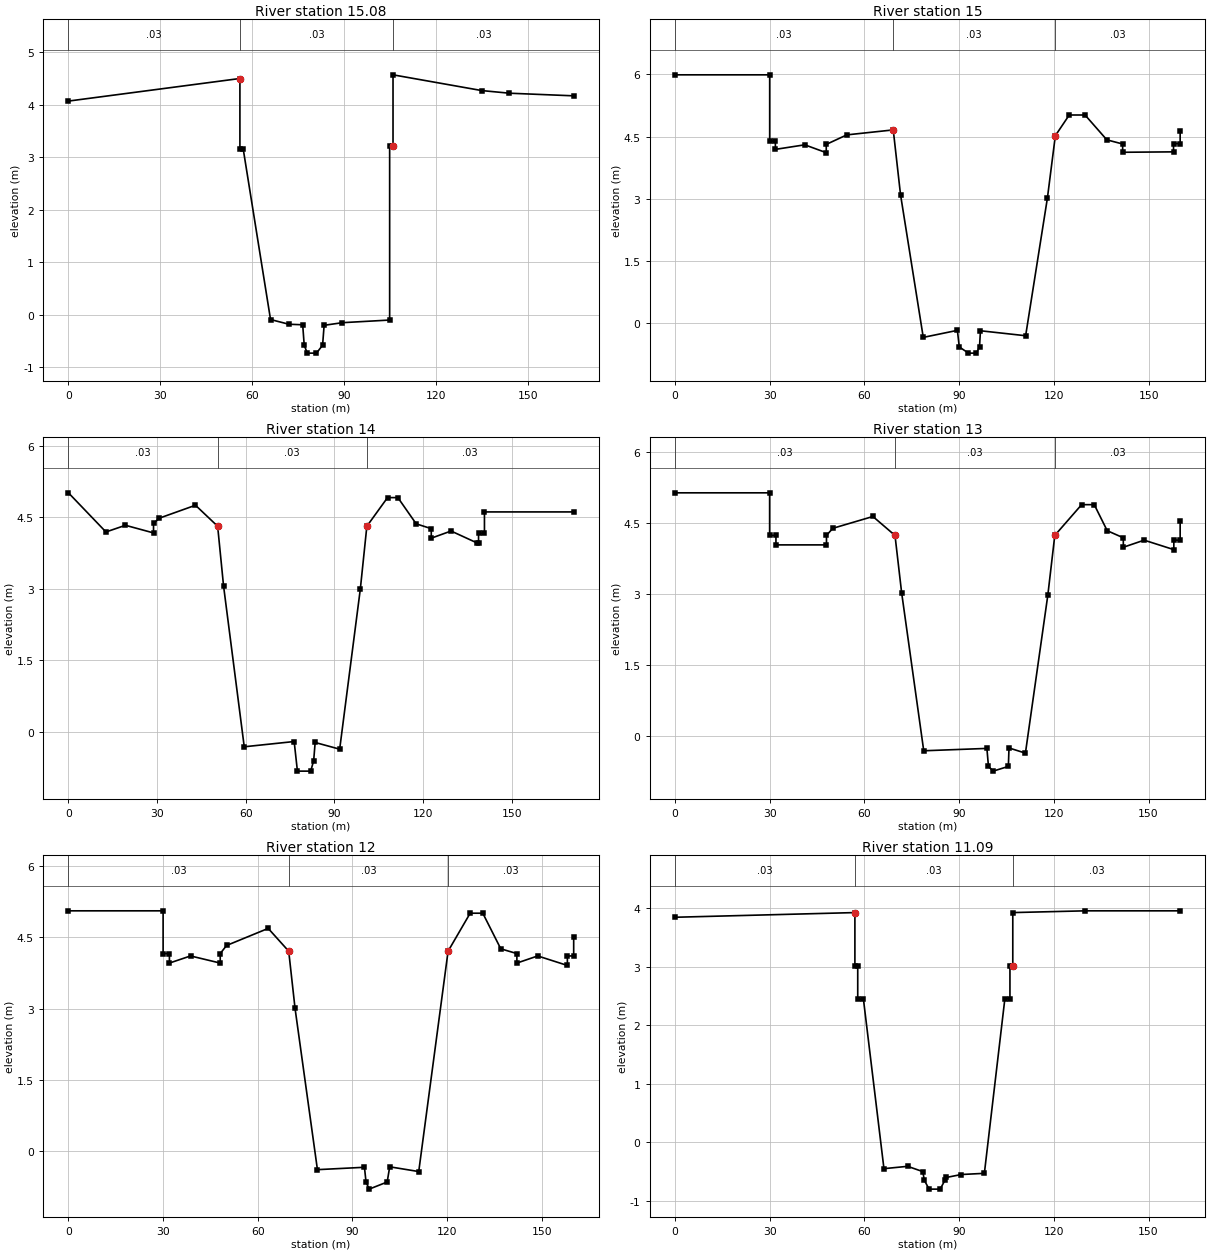
Type RM Length L Ch R = 1 ,15.08   ,8,8,8
#Sta/Elev= 20
       0    4.07      56     4.5      56    3.15    57.1    3.15      66    -.09
      72    -.18    76.5    -.19      77    -.58      78    -.73      81    -.73
      83    -.58    83.5     -.2    89.5    -.15   104.9     -.1   104.9    3.22
     106    3.22     106    4.57     135    4.27     144    4.22     165    4.17
#Mann= 3 , 0 , 0
       0     .03       0      56     .03       0     106     .03       0
Bank Sta=56,106
Exp/Cntr=0.5,0.3

Type RM Length L Ch R = 1 ,15      ,50,50,50
#Sta/Elev= 30
       0    5.99      30    5.99      30    4.39    31.8    4.39    31.8    4.19
    41.1     4.3    47.9    4.11    47.9    4.31    54.4    4.54    69.1    4.66
    71.4     3.1    78.6    -.35    89.4    -.18      90    -.58    92.9    -.73
    95.4    -.73    96.4    -.58    96.7    -.19     111    -.31   117.9    3.02
   120.4    4.52   124.8    5.02   129.8    5.02   136.7    4.42   141.7    4.32
   141.7    4.12   157.8    4.13   157.8    4.33   159.9    4.33   159.9    4.63
#Mann= 3 , 0 , 0
       0     .03       0    69.1     .03       0   120.4     .03       0
Bank Sta=69.1,120.4
Exp/Cntr=0.3,0.1

Type RM Length L Ch R = 1 ,14      ,50,50,50
#Sta/Elev= 30
       0    5.01    12.7    4.19    19.3    4.33    28.8    4.17    28.8    4.37
    30.8    4.48      43    4.75    50.5    4.31    52.5    3.06    59.5    -.31
    76.4     -.2    77.5    -.82      82    -.82      83     -.6    83.5    -.22
    91.8    -.36    98.8       3     101    4.31     108    4.91   111.5    4.91
   117.7    4.36   122.8    4.26   122.8    4.06   129.5    4.21   138.3    3.96
   138.8    3.96   138.8    4.16   140.8    4.16   140.8    4.61     171    4.61
#Mann= 3 , 0 , 0
       0     .03       0    50.5     .03       0     101     .03       0
Bank Sta=50.5,101
Exp/Cntr=0.3,0.1

Type RM Length L Ch R = 1 ,13      ,50,50,50
#Sta/Elev= 30
       0    5.13      30    5.13      30    4.23      32    4.23      32    4.03
      48    4.03      48    4.23      50    4.38    62.7    4.63    69.7    4.23
    71.8    3.02    78.8    -.32    98.8    -.27    99.3    -.65   100.8    -.75
   105.6    -.65   105.8    -.26     111    -.37   118.1    2.97   120.3    4.23
   128.8    4.88   132.8    4.88   136.9    4.33     142    4.18     142    3.98
   148.6    4.13     158    3.93     158    4.13     160    4.13     160    4.53
#Mann= 3 , 0 , 0
       0     .03       0    69.7     .03       0   120.3     .03       0
Bank Sta=69.7,120.3
Exp/Cntr=0.3,0.1

Type RM Length L Ch R = 1 ,12      ,41,41,41
#Sta/Elev= 30
       0    5.06      30    5.06      30    4.16      32    4.16      32    3.96
    38.7    4.11    48.1    3.96    48.1    4.16    50.1    4.33    63.3    4.69
    69.8    4.21    71.8    3.01    78.9    -.39    93.8    -.34    94.3    -.65
    95.3     -.8     101    -.65   101.8    -.33     111    -.43   120.3    4.21
   127.3    5.01   131.3    5.01     137    4.26   142.1    4.16   142.1    3.96
   148.7    4.11   158.1    3.91   158.1    4.11   160.1    4.11   160.1    4.51
#Mann= 3 , 0 , 0
       0     .03       0    69.8     .03       0   120.3     .03       0
Bank Sta=69.8,120.3
Exp/Cntr=0.3,0.1

Type RM Length L Ch R = 1 ,11.09   ,30,30,30
#Sta/Elev= 23
       0    3.85      57    3.93      57    3.02    57.9    3.02    57.9    2.45
    59.7    2.45    66.2    -.45    73.7    -.41    78.5     -.5      79    -.65
    80.5     -.8      84     -.8    85.5    -.65      86     -.6    90.7    -.55
      98    -.53   104.5    2.46   106.1    2.46   106.1    3.02     107    3.02
     107    3.93     130    3.96     160    3.96
#Mann= 3 , 0 , 0
       0     .03       0      57     .03       0     107     .03       0
Bank Sta=57,107
Exp/Cntr=0.5,0.3

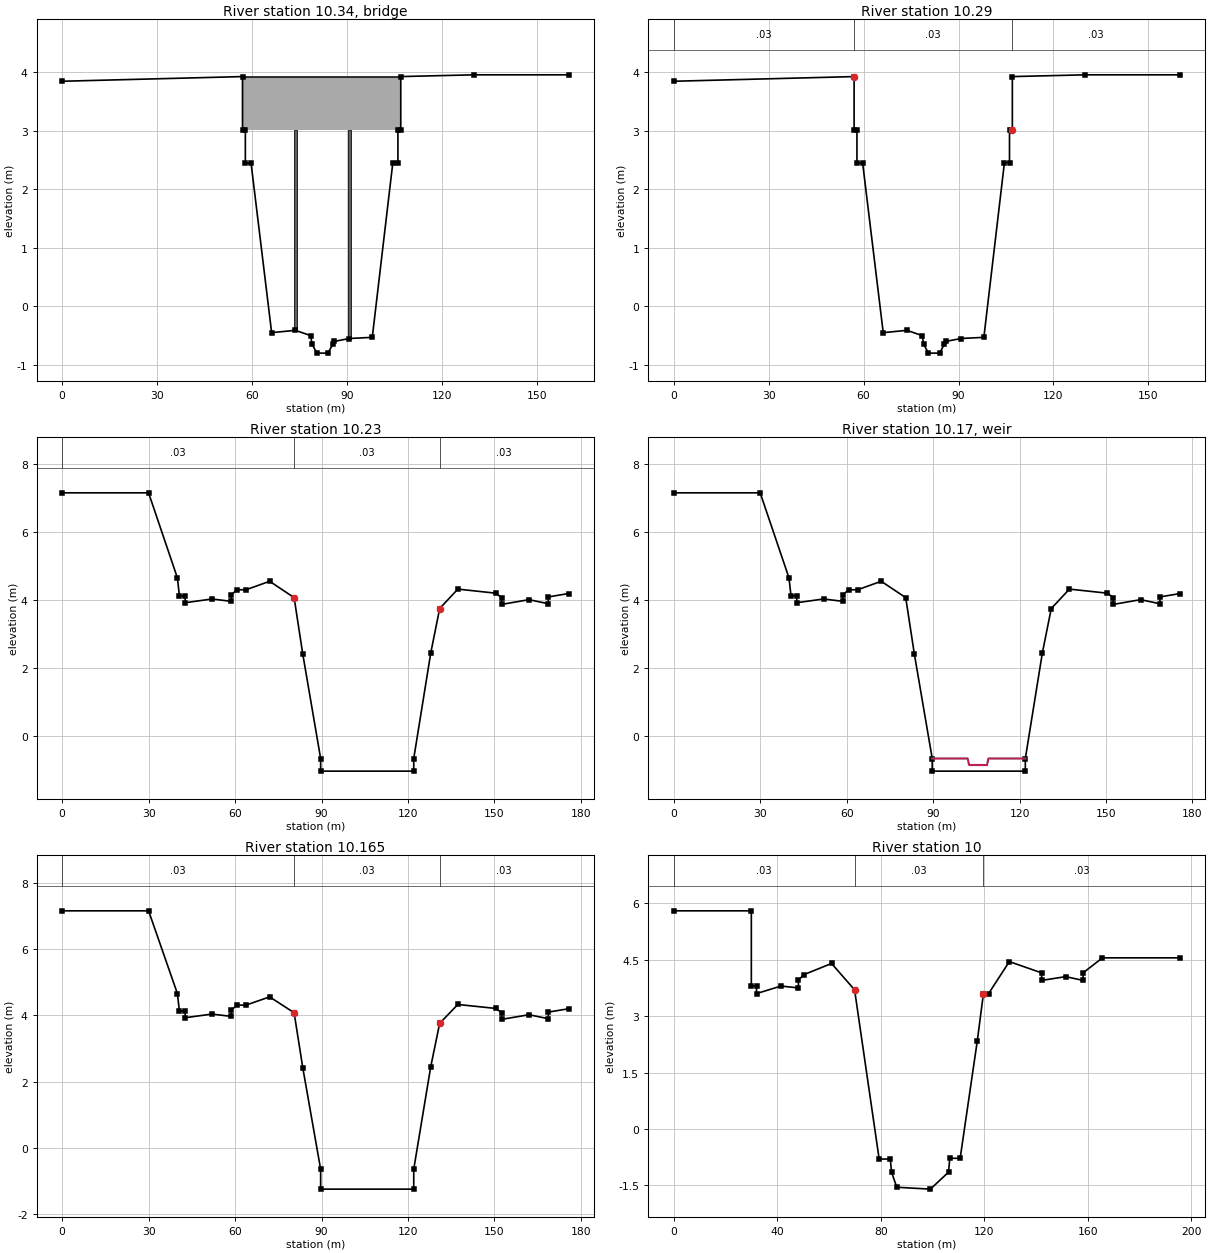
Type RM Length L Ch R = 3 ,10.34   ,,,
BEGIN DESCRIPTION:
È­Á¤15±³
END DESCRIPTION:
Bridge Culvert--1,0,-1,-1, 0
Deck Dist Width WeirC Skew NumUp NumDn MinLoCord MaxHiCord MaxSubmerge Is_Ogee
0.1,29,1.44,0, 2, 2, , , 0.95, 0, 0,0,,
      57     107
    3.93    3.93
    3.02    3.02
      57     107
    3.93    3.93
    3.02    3.02
Pier Skew, UpSta & Num, DnSta & Num=  ,73.7, 2 ,73.7, 2 , 0 , 0 , 0 ,,
       1       1
       0       4
       1       1
       0       4
Pier Skew, UpSta & Num, DnSta & Num=  ,90.7, 2 ,90.7, 2 , 0 , 0 , 0 ,,
       1       1
       0       4
       1       1
       0       4
BR Coef=-1 , 0 , 0 ,, 0 ,,,0.8,-1,,0,
WSPro=,,,, 1 ,,,, 0 ,,,, 0 ,,,,-1 ,-1 ,-1 , 0 , 0 , 0 , 0 , 0
BC Design=,, 0 ,, 0 ,,,,,,

Type RM Length L Ch R = 1 ,10.29   ,6,6,6
#Sta/Elev= 23
       0    3.85      57    3.93      57    3.02    57.9    3.02    57.9    2.45
    59.7    2.45    66.2    -.45    73.7    -.41    78.5     -.5      79    -.65
    80.5     -.8      84     -.8    85.5    -.65      86     -.6    90.7    -.55
      98    -.53   104.5    2.46   106.1    2.46   106.1    3.02     107    3.02
     107    3.93     130    3.96     160    3.96
#Mann= 3 , 0 , 0
       0     .03       0      57     .03       0     107     .03       0
Bank Sta=57,107
Exp/Cntr=0.5,0.3

Type RM Length L Ch R = 1 ,10.23   ,6.5,6.5,6.5
BEGIN DESCRIPTION:
10+17³«Â÷°ø»ó·ù
END DESCRIPTION:
#Sta/Elev= 28
       0    7.16      30    7.16      40    4.66    40.7    4.13    42.7    4.13
    42.7    3.93      52    4.04    58.7    3.97    58.7    4.17    60.8    4.31
    63.8    4.31      72    4.56    80.5    4.08    83.5    2.42    89.7    -.65
    89.7   -1.02     122   -1.02     122    -.65   127.9    2.45     131    3.76
   137.3    4.33   150.5    4.21   152.5    4.08   152.5    3.88     162    4.02
   168.7     3.9   168.7     4.1   175.7     4.2
#Mann= 3 , 0 , 0
       0     .03       0    80.5     .03       0     131     .03       0
Bank Sta=80.5,131
Exp/Cntr=0.3,0.1

Type RM Length L Ch R = 5 ,10.17   ,,,
IW Pilot Flow=0
#Inline Weir SE= 6
    89.7    -.65     102    -.65   102.5    -.84   108.7    -.84   109.2    -.65
     122    -.65
IW Dist,WD,Coef,Skew,MaxSub,Min_El,Is_Ogee,SpillHt,DesHd
6,0.5,1.44,0,0.95,, 0 ,,,0,0,

Type RM Length L Ch R = 1 ,10.165  ,16.5,16.5,16.5
BEGIN DESCRIPTION:
10+17³«Â÷°øÇÏ·ù
END DESCRIPTION:
#Sta/Elev= 28
       0    7.16      30    7.16      40    4.66    40.7    4.13    42.7    4.13
    42.7    3.93      52    4.04    58.7    3.97    58.7    4.17    60.8    4.31
    63.8    4.31      72    4.56    80.5    4.08    83.5    2.42    89.7    -.65
    89.7   -1.25     122   -1.25     122    -.65   127.9    2.45     131    3.76
   137.3    4.33   150.5    4.21   152.5    4.08   152.5    3.88     162    4.02
   168.7     3.9   168.7     4.1   175.7     4.2
#Mann= 3 , 0 , 0
       0     .03       0    80.5     .03       0     131     .03       0
Bank Sta=80.5,131
Exp/Cntr=0.3,0.1

Type RM Length L Ch R = 1 ,10      ,50,50,50
#Sta/Elev= 30
       0     5.8      30     5.8      30     3.8      32     3.8      32     3.6
    41.5     3.8    48.2    3.75    48.2    3.95    50.2     4.1      61     4.4
    69.9     3.7    79.4     -.8    83.7     -.8    84.2   -1.15    86.2   -1.55
    99.2    -1.6   106.2   -1.15   106.7    -.78   110.7    -.78   117.3    2.33
   119.7     3.6   121.7     3.6   129.7    4.45   142.2    4.15   142.2    3.95
   151.5    4.05   158.2    3.95   158.2    4.15   165.7    4.55   195.7    4.55
#Mann= 3 , 0 , 0
       0     .03       0    69.9     .03       0   119.7     .03       0
Bank Sta=69.9,119.7
Exp/Cntr=0.3,0.1

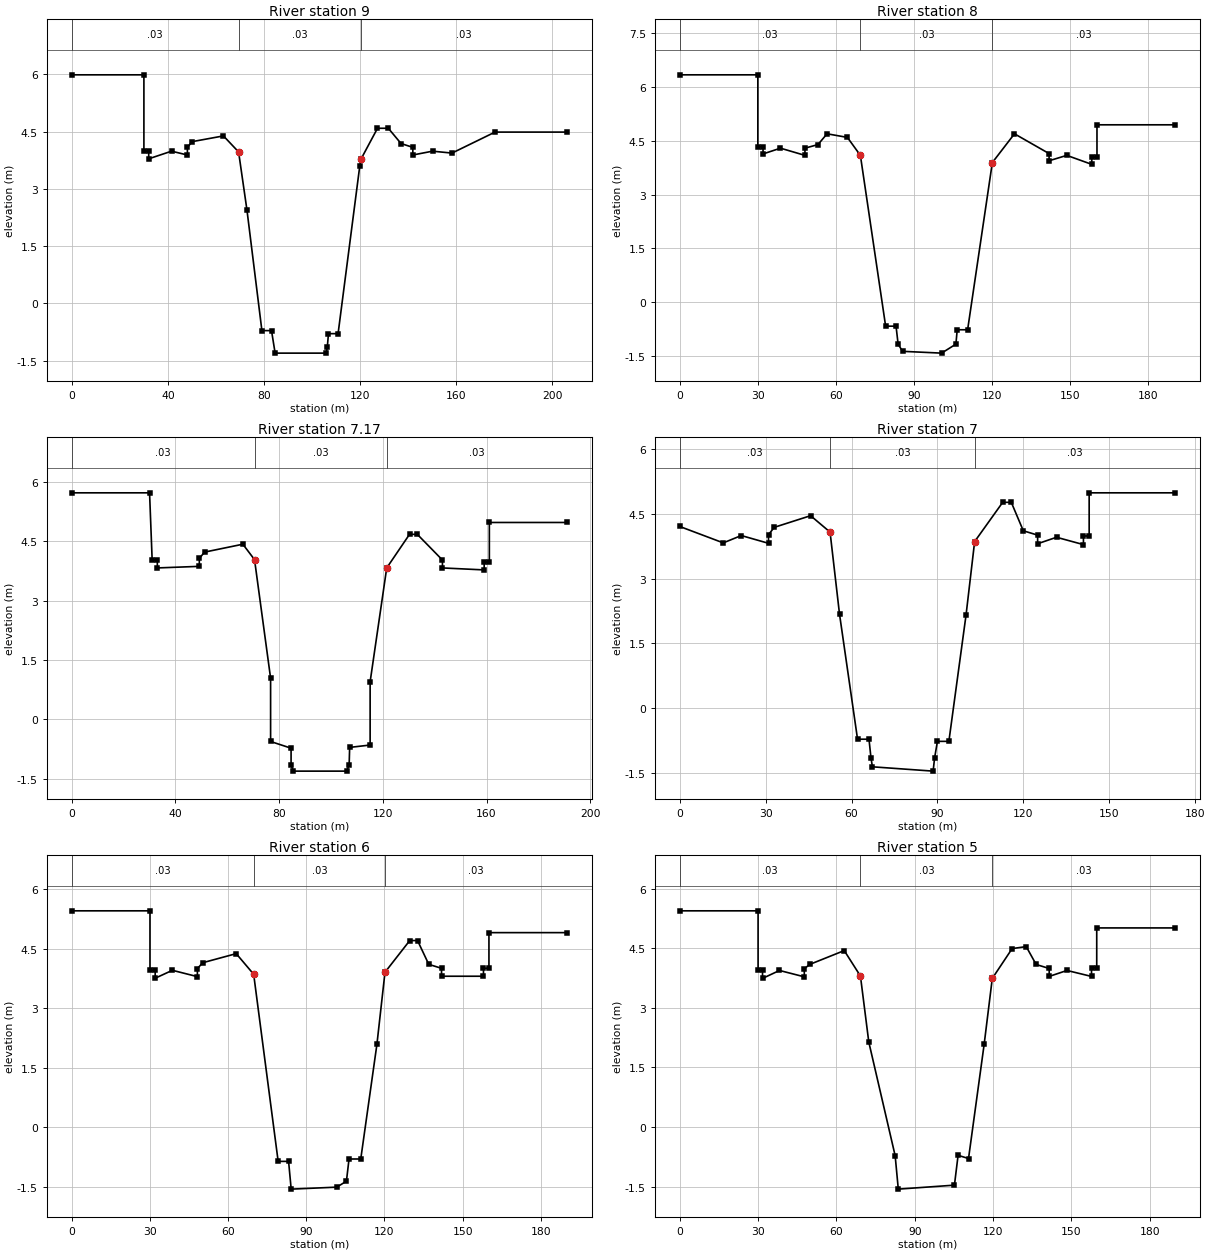
Type RM Length L Ch R = 1 ,9       ,50,50,50
#Sta/Elev= 30
       0    5.99      30    5.99      30    3.99      32    3.99      32    3.79
    41.5    3.99    48.1    3.89    48.1    4.09    50.1    4.24    63.1    4.39
    69.4    3.97    72.9    2.44    79.1    -.71    83.1    -.71    84.6    -1.3
   105.8    -1.3   106.3   -1.15   106.8    -.79   110.8    -.79   119.8    3.59
   120.4    3.79   127.2    4.59   131.7    4.59     137    4.19   141.9    4.09
   141.9    3.89   150.1    3.99   158.2    3.94   176.1    4.49   206.1    4.49
#Mann= 3 , 0 , 0
       0     .03       0    69.4     .03       0   120.4     .03       0
Bank Sta=69.4,120.4
Exp/Cntr=0.3,0.1

Type RM Length L Ch R = 1 ,8       ,33,33,33
#Sta/Elev= 30
       0    6.33      30    6.33      30    4.33      32    4.33      32    4.13
    38.7    4.29    48.1    4.09    48.1    4.29    53.1    4.39    56.6    4.69
    64.4    4.59    69.4    4.09    79.1    -.66    83.1    -.66    83.9   -1.16
    85.6   -1.36   100.6   -1.41   106.1   -1.16   106.6    -.76   110.6    -.76
   120.1    3.89   128.6    4.69   141.9    4.14   141.9    3.94   148.7    4.09
   158.3    3.84   158.3    4.04   160.3    4.04   160.3    4.94   190.3    4.94
#Mann= 3 , 0 , 0
       0     .03       0    69.4     .03       0   120.1     .03       0
Bank Sta=69.4,120.1
Exp/Cntr=0.3,0.1

Type RM Length L Ch R = 1 ,7.17    ,17,17,17
#Sta/Elev= 30
       0    5.73      30    5.73      31    4.03      33    4.03      33    3.83
    49.2    3.87    49.2    4.07    51.2    4.23      66    4.43    70.5    4.04
    76.7    1.04    76.7    -.56    84.6    -.73    84.6   -1.16    85.5   -1.31
     106   -1.31     107   -1.16   107.2    -.71   115.1    -.65   115.1     .95
   121.5    3.83   130.3    4.68   133.3    4.68     143    4.03     143    3.83
   159.1    3.78   159.1    3.98   161.1    3.98   161.1    4.98   191.1    4.98
#Mann= 3 , 0 , 0
       0     .03       0    70.5     .03       0   121.5     .03       0
Bank Sta=70.5,121.5
Exp/Cntr=0.3,0.1

Type RM Length L Ch R = 1 ,7       ,50,50,50
#Sta/Elev= 30
       0    4.21    15.2    3.83    21.5       4      31    3.82      31    4.02
      33    4.19    45.7    4.46    52.5    4.08    55.8    2.18    62.1    -.72
    66.1    -.72    66.8   -1.16    67.3   -1.36    88.5   -1.46      89   -1.16
      90    -.77      94    -.77     100    2.16     103    3.86   112.8    4.77
   115.8    4.77     120    4.11     125    4.01     125    3.81   131.6    3.96
     141    3.79     141    3.99     143    3.99     143    4.99     173    4.99
#Mann= 3 , 0 , 0
       0     .03       0    52.5     .03       0     103     .03       0
Bank Sta=52.5,103
Exp/Cntr=0.3,0.1

Type RM Length L Ch R = 1 ,6       ,50,50,50
#Sta/Elev= 30
       0    5.46      30    5.46      30    3.96      32    3.96      32    3.76
    38.6    3.96    48.2     3.8    48.2       4    50.2    4.15    63.1    4.38
    69.8    3.86    79.2    -.86    83.2    -.86    84.2   -1.56   101.7   -1.51
   105.4   -1.36   106.4     -.8   110.9     -.8   117.1    2.09   120.2    3.91
   129.7    4.71   132.7    4.71     137    4.11   141.9    4.01   141.9    3.81
     158    3.81     158    4.01   160.1    4.01   160.1    4.91   190.1    4.91
#Mann= 3 , 0 , 0
       0     .03       0    69.8     .03       0   120.2     .03       0
Bank Sta=69.8,120.2
Exp/Cntr=0.3,0.1

Type RM Length L Ch R = 1 ,5       ,50,50,50
#Sta/Elev= 30
       0    5.44      30    5.44      30    3.94    31.7    3.94    31.7    3.74
    38.2    3.94    47.7    3.78    47.7    3.98    49.7    4.09      63    4.44
    69.2     3.8    72.4    2.14    82.5    -.72    83.7   -1.56   105.2   -1.46
   106.6    -.71   110.6    -.79   116.6    2.09   119.7    3.74   127.3    4.49
   132.7    4.54   136.5    4.09   141.5    3.99   141.5    3.79   148.3    3.94
   157.7    3.79   157.7    4.01   159.7    4.01   159.7    5.01   189.7    5.01
#Mann= 3 , 0 , 0
       0     .03       0    69.2     .03       0   119.7     .03       0
Bank Sta=69.2,119.7
Exp/Cntr=0.3,0.1