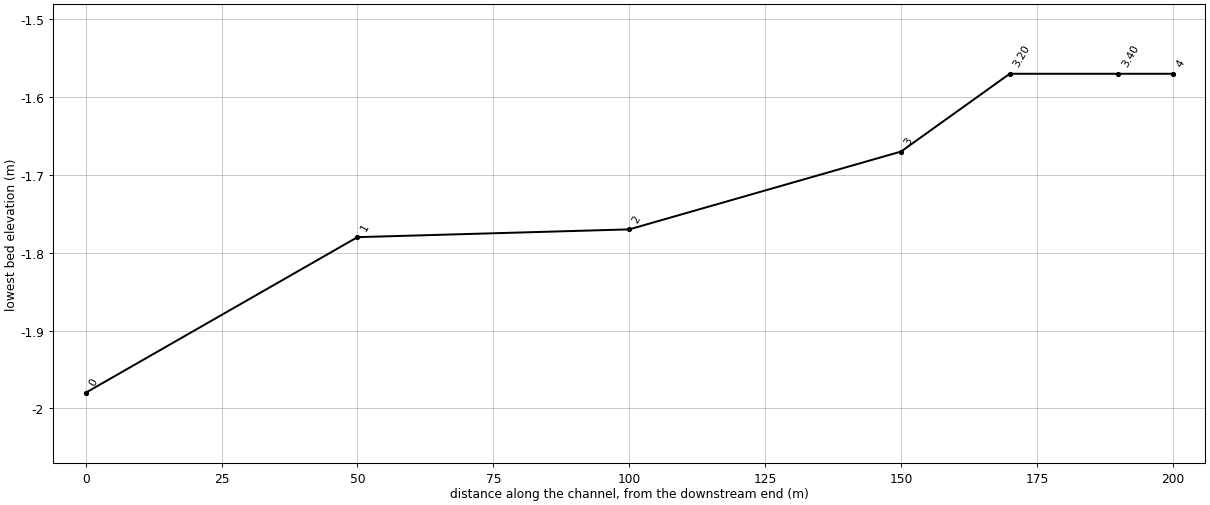
HEC-RAS study Hwajung.prj: Hwajung

--- Hwajung.g01 (geometry) --- (continued)

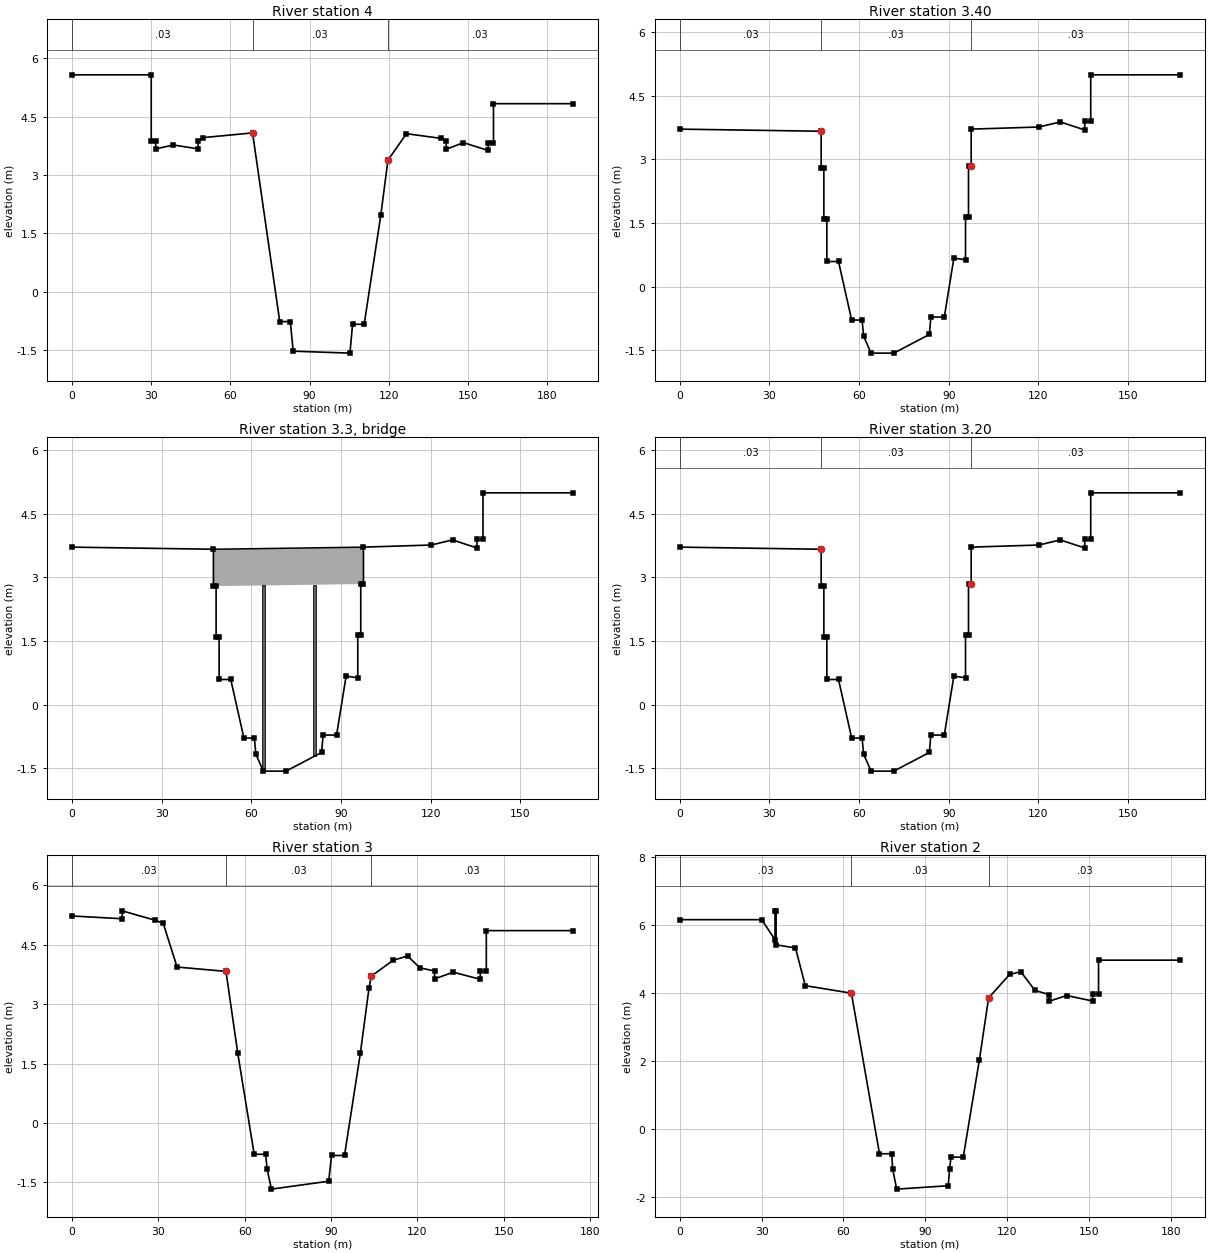
Type RM Length L Ch R = 1 ,4       ,10,10,10
#Sta/Elev= 28
       0    5.57      30    5.57      30    3.87    31.7    3.87    31.7    3.67
    38.4    3.77    47.8    3.67    47.8    3.87    49.8    3.96    68.4    4.08
    78.7    -.76    82.7    -.76    83.8   -1.52   105.3   -1.57   106.3    -.83
   110.7    -.83     117    1.97   119.7    3.38   126.7    4.06   139.8    3.94
   141.8    3.86   141.8    3.66   148.3    3.83   157.7    3.63   157.7    3.83
   159.7    3.83   159.7    4.83   189.7    4.83
#Mann= 3 , 0 , 0
       0     .03       0    68.4     .03       0   119.7     .03       0
Bank Sta=68.4,119.7
Exp/Cntr=0.3,0.1

Type RM Length L Ch R = 1 ,3.40    ,20,20,20
#Sta/Elev= 30
       0    3.71    47.3    3.66    47.3    2.79    48.2    2.79    48.2    1.59
    49.2    1.59    49.2     .59    53.1     .59    57.5    -.79      61    -.79
    61.5   -1.17      64   -1.57    71.6   -1.57    83.5   -1.13      84    -.72
    88.5    -.72    91.7     .67    95.6     .63    95.6    1.64    96.6    1.64
    96.6    2.84    97.5    2.84    97.5    3.71   120.2    3.76   127.3    3.88
   135.5    3.69   135.5    3.89   137.5    3.89   137.5    4.99   167.5    4.99
#Mann= 3 , 0 , 0
       0     .03       0    47.3     .03       0    97.5     .03       0
Bank Sta=47.3,97.5
Exp/Cntr=0.5,0.3

Type RM Length L Ch R = 3 ,3.3     ,,,
BEGIN DESCRIPTION:
È­Á¤16±³
END DESCRIPTION:
Bridge Culvert--1,0,-1,-1, 0
Deck Dist Width WeirC Skew NumUp NumDn MinLoCord MaxHiCord MaxSubmerge Is_Ogee
0.1,19,1.44,0, 2, 2, , , 0.95, 0, 0,0,,
    47.3    97.5
    3.66    3.71
    2.79    2.84
    47.3    97.5
    3.66    3.71
    2.79    2.84
Pier Skew, UpSta & Num, DnSta & Num=  ,64, 2 ,64, 2 , 0 , 0 , 0 ,,
       1       1
       0     4.5
       1       1
       0     4.5
Pier Skew, UpSta & Num, DnSta & Num=  ,81, 2 ,81, 2 , 0 , 0 , 0 ,,
       1       1
       0     4.5
       1       1
       0     4.5
BR Coef=-1 , 0 , 0 ,, 0 ,,,0.8,-1,,0,
WSPro=,,,, 1 ,,,, 0 ,,,, 0 ,,,,-1 ,-1 ,-1 , 0 , 0 , 0 , 0 , 0
BC Design=,, 0 ,, 0 ,,,,,,

Type RM Length L Ch R = 1 ,3.20    ,20,20,20
#Sta/Elev= 30
       0    3.71    47.3    3.66    47.3    2.79    48.2    2.79    48.2    1.59
    49.2    1.59    49.2     .59    53.1     .59    57.5    -.79      61    -.79
    61.5   -1.17      64   -1.57    71.6   -1.57    83.5   -1.13      84    -.72
    88.5    -.72    91.7     .67    95.6     .63    95.6    1.64    96.6    1.64
    96.6    2.84    97.5    2.84    97.5    3.71   120.2    3.76   127.3    3.88
   135.5    3.69   135.5    3.89   137.5    3.89   137.5    4.99   167.5    4.99
#Mann= 3 , 0 , 0
       0     .03       0    47.3     .03       0    97.5     .03       0
Bank Sta=47.3,97.5
Exp/Cntr=0.5,0.3

Type RM Length L Ch R = 1 ,3       ,50,50,50
#Sta/Elev= 29
       0    5.23    17.4    5.16    17.4    5.36      29    5.12    31.7    5.04
    36.5    3.94    53.5    3.83    57.6    1.76    63.3    -.79    67.3    -.79
    67.8   -1.17    69.3   -1.67    89.2   -1.47    90.2    -.82    94.7    -.82
   100.2    1.76   103.2     3.4     104    3.71   111.6    4.11   116.6    4.22
   120.9    3.92     126    3.84     126    3.64   132.5    3.81   141.9    3.63
   141.9    3.83     144    3.83     144    4.86     174    4.86
#Mann= 3 , 0 , 0
       0     .03       0    53.5     .03       0     104     .03       0
Bank Sta=53.5,104
Exp/Cntr=0.3,0.1

Type RM Length L Ch R = 1 ,2       ,50,50,50
#Sta/Elev= 30
       0    6.15      30    6.15    34.9    5.56    34.9    6.41    35.3    6.41
    35.3    5.41    42.4    5.32      46    4.21    62.9    3.99    73.2    -.73
    77.7    -.73      78   -1.17    79.5   -1.77    98.4   -1.67    98.9   -1.17
    99.4    -.83   103.9    -.83   109.8    2.02   113.2    3.85   120.9    4.54
     125    4.62   130.2    4.07   135.3    3.95   135.3    3.75   141.8    3.92
   151.3    3.76   151.3    3.96   153.5    3.96   153.5    4.96   183.5    4.96
#Mann= 3 , 0 , 0
       0     .03       0    62.9     .03       0   113.2     .03       0
Bank Sta=62.9,113.2
Exp/Cntr=0.3,0.1

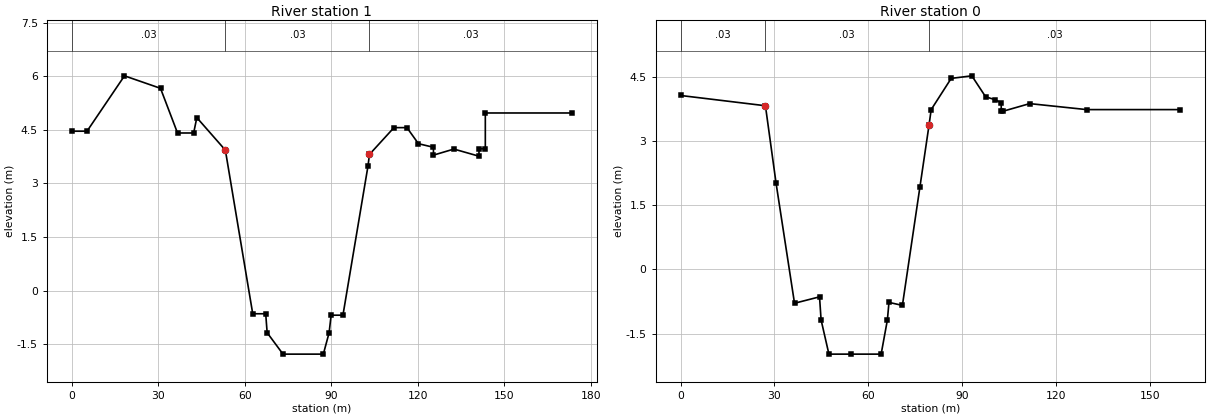
Type RM Length L Ch R = 1 ,1       ,50,50,50
#Sta/Elev= 29
       0    4.46     5.2    4.46    18.2    6.01    30.7    5.66    36.6    4.41
    42.2    4.41    43.3    4.84    53.2    3.93    62.7    -.65    67.2    -.65
    67.7   -1.18    73.2   -1.78    87.2   -1.78    89.2   -1.18    89.9    -.69
      94    -.69   102.7    3.49   103.2    3.81   111.7    4.56   116.2    4.56
   120.2    4.11   125.4    4.01   125.4    3.79   132.5    3.96   141.2    3.76
   141.2    3.97   143.4    3.97   143.4    4.97   173.4    4.97
#Mann= 3 , 0 , 0
       0     .03       0    53.2     .03       0   103.2     .03       0
Bank Sta=53.2,103.2
Exp/Cntr=0.3,0.1

Type RM Length L Ch R = 1 ,0       ,0,0,0
#Sta/Elev= 25
       0    4.07    27.1    3.83    30.5    2.02    36.4    -.79    44.4    -.64
    44.9   -1.18    47.4   -1.98    54.4   -1.98    64.1   -1.98    66.1   -1.18
    66.6    -.77    70.9    -.84    76.5    1.93    79.4    3.37    80.1    3.74
    86.5    4.47    93.1    4.53    97.5    4.04   100.6    3.97   102.5     3.9
   102.5     3.7     103     3.7   111.6    3.88   129.8    3.74   159.8    3.74
#Mann= 3 , 0 , 0
       0     .03       0    27.1     .03       0    79.4     .03       0
Bank Sta=27.1,79.4
Exp/Cntr=0.3,0.1

Chan Stop Cuts=-1
Use User Specified Reach Order=0
User Specified Reach Order=RIVER-1         ,Reach-1